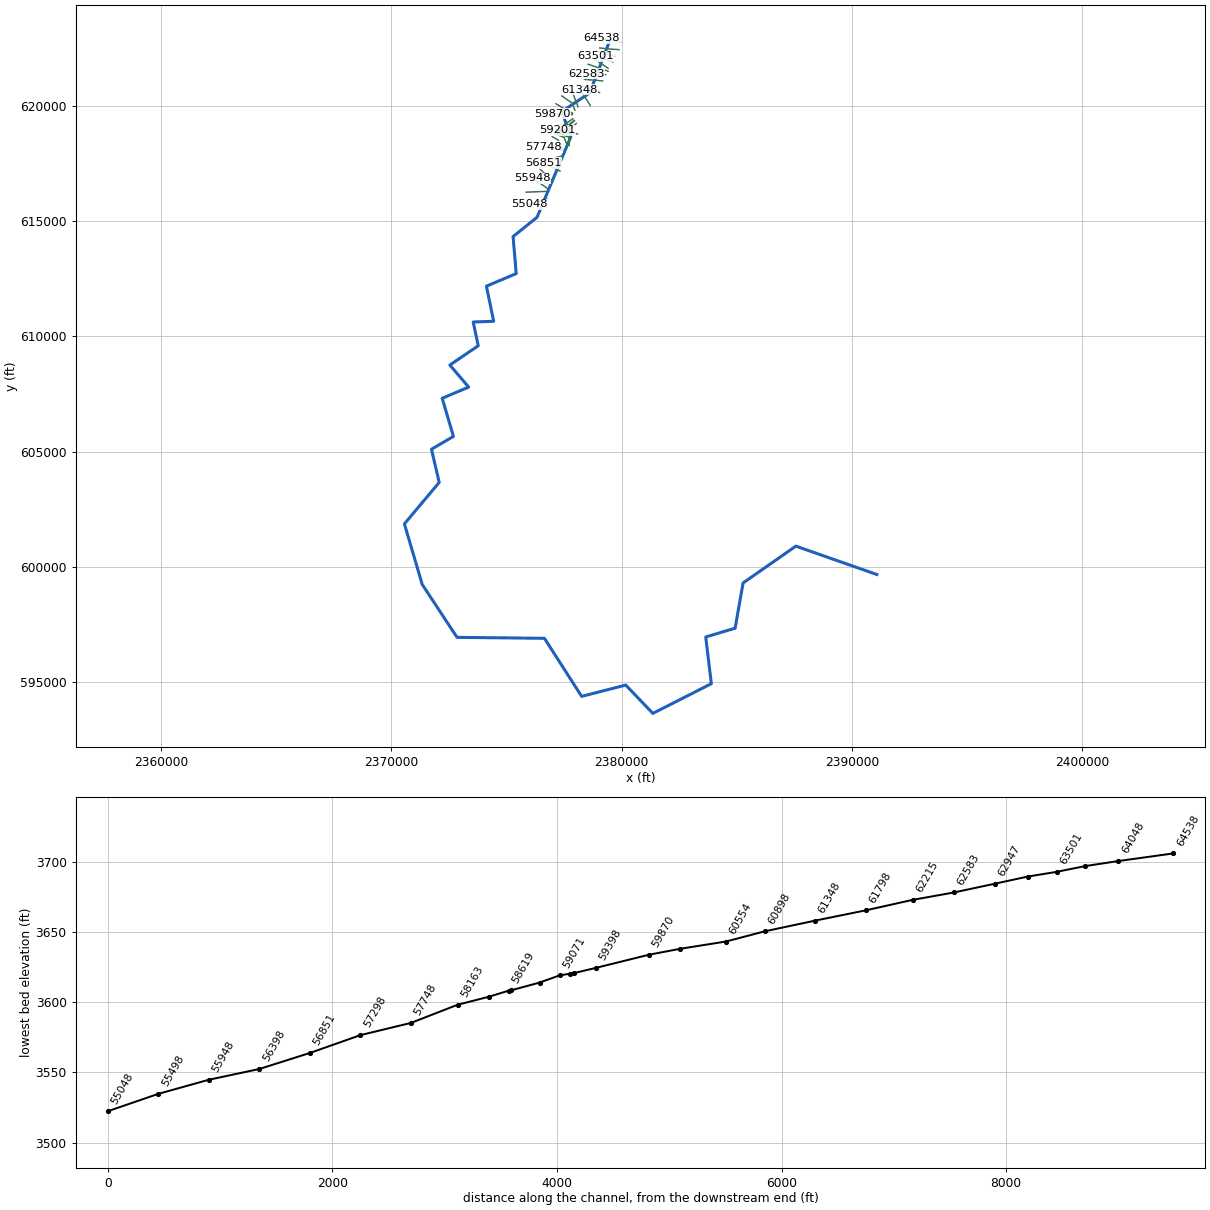
--- BIGRN.prj (project) ---

Proj Title=BIGRN
Current Plan=p01
Default Exp/Contr=0,0
English Units
Geom File=g01
Geom File=g02
Flow File=f01
Plan File=p01
BEGIN DESCRIPTION:
Stream Name: Big Run
Flood Zone: Approximate
Pendleton County, West Virginia
HEC-RAS Version: 5.0.7
Hydrology Method:
Regression equation
END DESCRIPTION:
DSS Export Rating Curves= 0
DSS Export Rating Curve Sorted= 0
DSS Export Volume Flow Curves= 0
DXF OffsetX= 0
DXF OffsetY= 0
DXF ScaleX= 0
DXF ScaleY= 0

--- BIGRN.p01 (plan) ---

Plan Title=Floodplain
Program Version=5.07
Short Identifier=Floodplain
Geom File=g01
Flow File=f01
Subcritical Flow
K Sum by GR= 0
Std Step Tol= 0.01
Critical Tol= 0.01
Num of Std Step Trials= 20
Max Error Tol= 0.3
Flow Tol Ratio= 0.001
Split Flow NTrial= 30
Split Flow Tol= 0.02
Split Flow Ratio= 0.02
Log Output Level= 0
Friction Slope Method= 1
Unsteady Friction Slope Method= 2
Unsteady Bridges Friction Slope Method= 1
Parabolic Critical Depth
Global Vel Dist= 0 , 0 , 0
Global Log Level= 0
CheckData=False
Encroach Param=-1 ,0,0, 0
Mapping Interval=1HOUR
Computation Time Step Use Courant=        0
Computation Time Step Use Time Series=    0
Computation Time Step Count To Double=0
Computation Time Step Max Doubling=0
Computation Time Step Max Halving=0
Computation Time Step Residence Courant=0
Run HTab= 0
Run UNet= 0
Run Sediment= 0
Run PostProcess= 0
Run WQNet= 0
Run RASMapper= 0
UNET Theta= 0
UNET Theta Warmup= 0
UNET ZTol= 0
UNET ZSATol= 0
UNET MxIter= 0
UNET Max Iter WO Improvement= 0
UNET MaxInSteps= 0
UNET DtIC= 0
UNET DtMin= 0
UNET MaxCRTS= 0
UNET WFStab= 0
UNET SFStab= 0
UNET WFX= 1
UNET SFX= 1
UNET 1D Methodology=Finite Difference
UNET DSS MLevel= 1
UNET Pardiso=0
UNET DZMax Abort= 0
UNET Use Existing IB Tables= 0
UNET Froude Reduction=False
UNET Froude Limit= 0
UNET Froude Power= 0
UNET D1 Cores= 0
UNET D2 Coriolis=0
UNET D2 Cores= 0
UNET D2 Theta= 1
UNET D2 Theta Warmup= 1
UNET D2 Z Tol= 0.01
UNET D2 Volume Tol= 0.01
UNET D2 Max Iterations= 20
UNET D2 Equation= 0
UNET D2 RampUpFraction=0.1
UNET D2 TimeSlices= 1
UNET D2 BCVolumeCheck=0
UNET D1D2 MaxIter= 0
UNET D1D2 ZTol=0.01
UNET D1D2 QTol=0.1
UNET D1D2 MinQTol=1
Write IC File= 0
Write IC File at Fixed DateTime=0
Write IC File at Sim End=0
Echo Input=False
Echo Parameters=False
Echo Output=False
Write Detailed= 0
HDF Write Warmup=0
HDF Write Time Slices=0
HDF Flush=0
HDF Face Node Velocities=0
HDF Compression= 1
HDF Chunk Size= 1
HDF Spatial Parts= 1
HDF Use Max Rows=0
HDF Fixed Rows= 1
Calibration Method= 0
Calibration Iterations= 20
Calibration Max Change=0.05
Calibration Tolerance=0.2
Calibration Maximum=1.5
Calibration Minimum=0.5
Calibration Optimization Method= 1
WQ AD Non Conservative
WQ ULTIMATE=-1
WQ Max Comp Step=1HOUR
WQ Output Interval=15MIN
WQ Output Selected Increments= 0
WQ Output face flow=0
WQ Output face velocity=0
WQ Output face area=0
WQ Output face dispersion=0
WQ Output cell volume=0
WQ Output cell surface area=0
WQ Output cell continuity=0
WQ Output cumulative cell continuity=0
WQ Output face conc=0
WQ Output face dconc_dx=0
WQ Output face courant=0
WQ Output face peclet=0
WQ Output face adv mass=0
WQ Output face disp mass=0
WQ Output cell mass=0
WQ Output cell source sink temp=0
WQ Output nsm pathways=0
WQ Output nsm derived pathways=0
WQ Output MaxMinRange=-1
WQ Daily Max Min Mean=-1
WQ Daily Range=0
WQ Daily Time=0
WQ Create Restart=0
WQ Fixed Restart=0
WQ System Summary=0
WQ Write To DSS=0
WQ Use Fixed Temperature=0
Sorting and Armoring Iterations= 10
XS Update Threshold= 0.02
Bed Roughness Predictor= 0
Hydraulics Update Threshold= 0.02
Energy Slope Method= 1
Volume Change Method= 1
Sediment Retention Method= 0
XS Weighting Method= 0
Number of US Weighted Cross Sections= 1
Number of DS Weighted Cross Sections= 1
Upstream XS Weight=0
Main XS Weight=1
Downstream XS Weight=0
Number of DS XS's Weighted with US Boundary= 1
Upstream Boundary Weight= 1
Weight of XSs Associated with US Boundary= 0
Number of US XS's Weighted with DS Boundary= 1
Downstream Boundary Weight= 0.5
Weight of XSs Associated with DS Boundary= 0.5
Percentile Method= 0
Sediment Output Level= 3
Mass or Volume Output= 0
Output Increment Type= 1
Profile and TS Output Increment= 1
XS Output Flag= 0
XS Output Increment= 10
Write Gradation File= 0
Read Gradation Hotstart= 0
Write HDF5 File= 1
Write Binary Output= 1
Write DSS Sediment File= 0
SV Curve= 0
Specific Gage Flag= 0

--- BIGRN.f01 (steady flow) ---

Flow Title=Flows
Program Version=5.07
Number of Profiles= 6
Profile Names=P100yr,P10yr,P25yr,P50yr,P500yr,P101yr
River Rch & RM=BIGRN,Main            ,64538
     550     258     364     454     806     670
River Rch & RM=BIGRN,Main            ,63748
     655     306     432     540     961     797
River Rch & RM=BIGRN,Main            ,60554
     736     343     485     607    1081     895
River Rch & RM=BIGRN,Main            ,59398
     930     432     612     766    1370    1131
River Rch & RM=BIGRN,Main            ,58893
    1033     479     680     851    1524    1258
River Rch & RM=BIGRN,Main            ,57298
    1149     532     755     946    1696    1398
River Rch & RM=BIGRN,Main            ,55048
    1281     592     841    1054    1893    1558
River Rch & RM=BIGRN,Main            ,49648
    1459     673     957    1200    2159    1775
River Rch & RM=BIGRN,Main            ,46497
    1639     755    1075    1349    2430    1995
River Rch & RM=BIGRN,Main            ,43206
    1822     838    1193    1498    2703    2218
River Rch & RM=BIGRN,Main            ,34798
    2029     931    1328    1668    3014    2470
River Rch & RM=BIGRN,Main            ,27259
    2927    1336    1909    2402    4364    3562
River Rch & RM=BIGRN,Main            ,19207
    3963    1800    2579    3249    5927    4823
River Rch & RM=BIGRN,Main            ,17397
    5488    2481    3562    4495    8237    6679
Boundary for River Rch & Prof#=BIGRN,Main            , 1
Up Type= 0
Dn Type= 3
Dn Slope=0.01725
Boundary for River Rch & Prof#=BIGRN,Main            , 2
Up Type= 0
Dn Type= 3
Dn Slope=0.01725
Boundary for River Rch & Prof#=BIGRN,Main            , 3
Up Type= 0
Dn Type= 3
Dn Slope=0.01725
Boundary for River Rch & Prof#=BIGRN,Main            , 4
Up Type= 0
Dn Type= 3
Dn Slope=0.01725
Boundary for River Rch & Prof#=BIGRN,Main            , 5
Up Type= 0
Dn Type= 3
Dn Slope=0.01725
Boundary for River Rch & Prof#=BIGRN,Main            , 6
Up Type= 0
Dn Type= 3
Dn Slope=0.01725
DSS Import GetInterval= 0
DSS Import GetPeak= 0
DSS Import FillOption= 0

--- BIGRN.g01 (geometry) ---

Geom Title=Geometry
Program Version=5.07

River Reach=BIGRN           ,Main
Reach XY= 30
2379496.59970871622878.4198697062378615.19100001620577.744333342
2377406.93400002619769.5123333332377796.47799999 618672.47633335
2376330.16000003615175.9453333472375290.98199999614338.598333329
2375425.97800002612729.912333354     2374134.081612183.369333342
2374448.23300001610660.2113333342373559.53999999610627.133333355
2373778.85300002 609595.525333332372547.60100004608759.580333352
     2373361.498607800.5823333412372215.10600001607315.806333333
2372701.18000001605658.7423333382371748.41500002605100.754333332
2372084.78600001603660.6623333392370573.52700004601860.331333339
2371347.09200001599229.6433333312372857.45000002596931.221333355
2376651.50500003596890.3013333532378265.51300004594368.037333354
2380179.19200003594859.813333347     2381356.236 593629.76333335
2383894.36900002594918.2763333322383652.28100002596948.199333355
2384927.34200001597329.966333345     2385273.116599294.766333342
2387563.19300002600893.4943333272391076.62829554599661.430273041

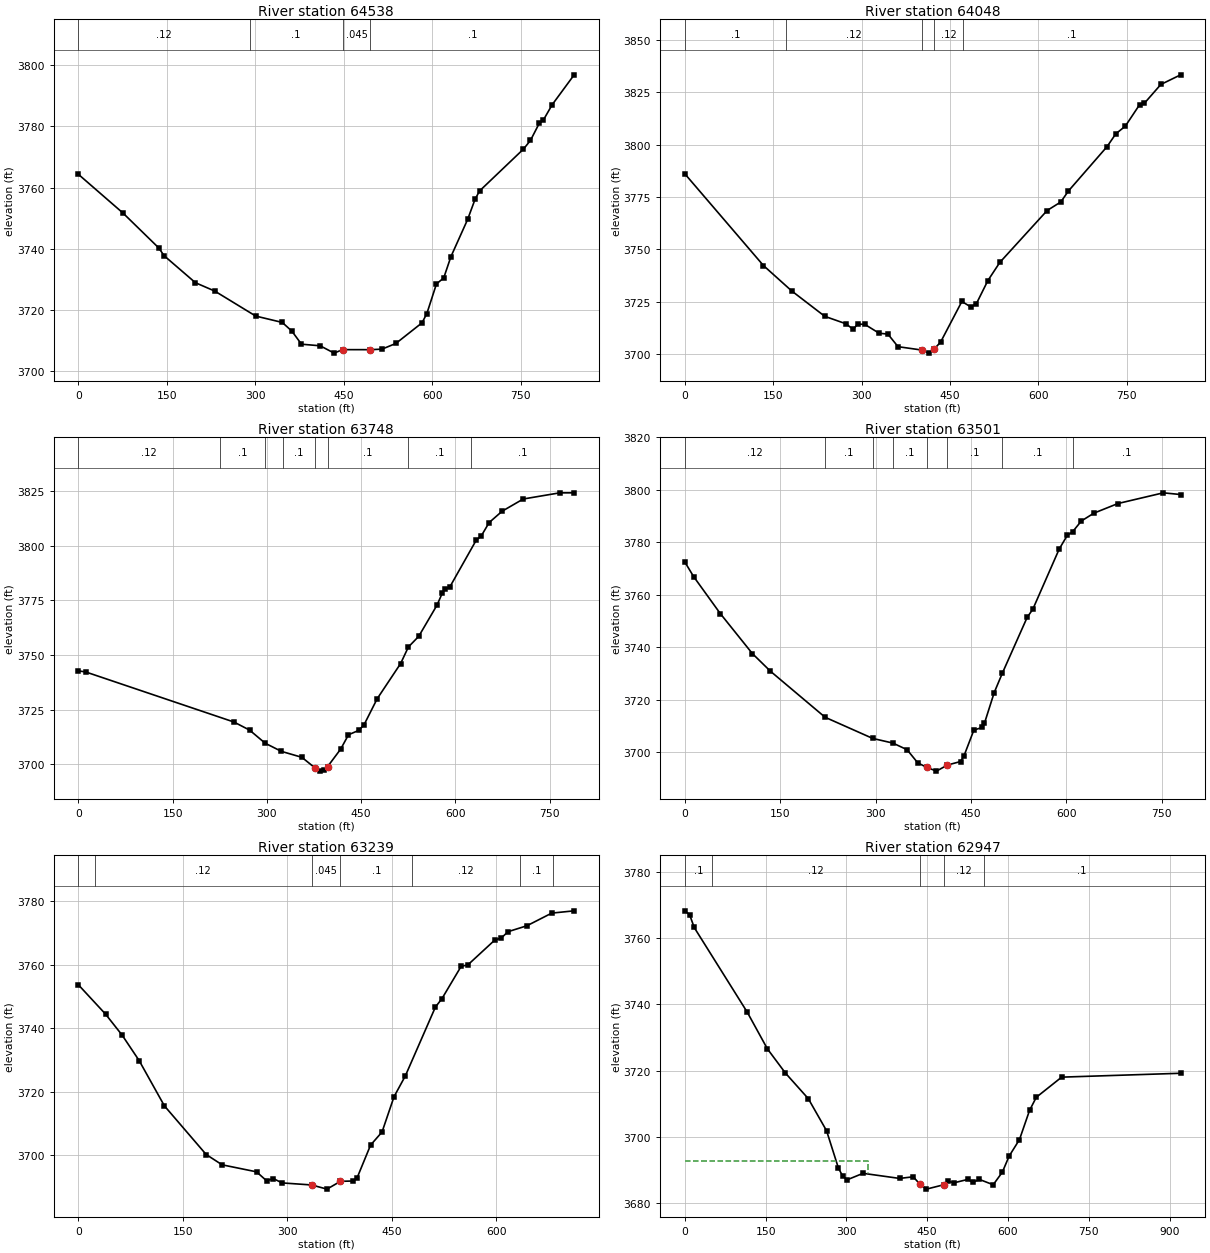
Type RM Length L Ch R = 1 ,64538   ,490.1,490.1,490.1
XS GIS Cut Line= 2
 2379961.1624795622775.866377598     2379138.232      622948.161
#Sta/Elev= 30
       0 3764.34    75.6 3751.68   136.4 3740.25   145.5  3737.7   198.6 3728.87
   231.3 3726.15   300.8 3717.97   345.8 3715.89   362.1 3713.05   378.4 3708.77
   410.1 3708.25   433.8 3705.85     448 3706.99   495.4 3706.98   514.9 3707.15
   538.5 3709.02   582.8 3715.76     591 3718.79   607.3 3728.49   619.6 3730.43
   631.8 3737.39   660.2 3749.59   672.7 3756.14   680.4 3758.89   754.8 3772.57
   766.7 3775.41   781.8 3781.07   788.6 3782.08   803.5 3787.08   840.8 3796.86
#Mann= 4 ,-1 , 0
       0     .12       0  291.05      .1       0     448    .045       0
   495.4      .1       0
Bank Sta=448,495.4
XS Rating Curve= 0 ,0
Exp/Cntr=0.3,0.1

Type RM Length L Ch R = 1 ,64048   ,301.1,300,296.3
XS GIS Cut Line= 3
     2379891.978      622457.902     2379482.792      622484.259
2379053.30643252622528.979803514
#Sta/Elev= 30
       0 3786.05   133.5 3742.25   181.6  3730.1   237.7 3717.99   273.8 3714.42
   285.8 3711.78   293.8 3714.34   305.9 3714.11   329.9 3709.93   344.8 3709.52
     362 3703.51   402.53701.895   414.1 3700.43   423.4  3702.4   434.2 3705.65
   470.4 3725.09   485.3 3722.52   494.5 3723.73   514.6 3735.09   534.8 3743.72
   615.2 3768.52   638.3 3772.58   651.4 3777.86   716.9 3799.02   731.8 3805.14
   747.9 3808.78     772 3818.97   780.1 3819.66   808.2 3828.69   841.8 3833.29
#Mann= 5 ,-1 , 0
       0      .1       0  172.57     .12       0   402.5    .045       0
   423.4     .12       0  471.73      .1       0
Bank Sta=402.5,423.4
XS Rating Curve= 0 ,0
Exp/Cntr=0.3,0.1

Type RM Length L Ch R = 1 ,63748   ,246.1,247.2,245.2
XS GIS Cut Line= 3
2379697.81248776622174.321905213     2379327.754      622273.688
     2378936.253       622379.81
#Sta/Elev= 30
       0 3742.71    11.5 3742.24   247.5 3719.28   272.4 3715.58   297.2 3709.57
   322.9 3705.84   355.6  3703.1   376.23698.324   384.2 3696.77   391.5 3697.34
   396.6 3698.86   417.4 3706.88   429.8 3713.43   446.4 3715.48   454.7  3718.1
   475.4 3729.92   512.7 3746.06   525.1 3753.67   541.5 3758.52   570.7 3772.88
     579 3778.35   583.1 3780.02   591.4 3781.37   632.8  3802.5   641.2 3804.64
   653.6 3810.69   674.3 3815.89   707.8 3821.47   765.5 3824.28   788.8  3824.3
#Mann= 8 ,-1 , 0
       0     .12       0  225.29      .1       0   297.2      .1       0
  325.12      .1       0   376.2    .045       0   396.6      .1       0
  524.83      .1       0  624.68      .1       0
Bank Sta=376.2,396.6
XS Rating Curve= 0 ,0
Exp/Cntr=0.3,0.1

Type RM Length L Ch R = 1 ,63501   ,266,262.3,253
XS GIS Cut Line= 2
2379623.97533879 621925.341129482378880.74968476622160.818564421
#Sta/Elev= 30
       0 3772.48    13.9  3766.9    55.8 3752.81   106.2 3737.58   134.6 3730.85
   220.6 3713.29   295.4 3705.23   327.2 3703.45   349.5 3700.92   366.3 3695.91
   380.73694.176   395.7 3692.76   412.9 3695.08   433.5 3696.41   438.8 3698.47
   454.5  3708.4   467.4  3709.4   471.2 3711.04   486.5 3722.71   499.3  3730.1
   538.4 3751.41   547.1 3754.41   588.7 3777.41   601.3 3782.57   609.7 3783.98
   623.6 3788.11   643.3 3791.09     681 3794.75   752.4 3798.83   779.6 3798.18
#Mann= 8 ,-1 , 0
       0     .12       0   220.6      .1       0   295.4      .1       0
   327.2      .1       0   380.7    .045       0   412.9      .1       0
   499.3      .1       0   609.7      .1       0
Bank Sta=380.7,412.9
XS Rating Curve= 0 ,0
Exp/Cntr(USF)=0,0
Exp/Cntr=0.3,0.1

Type RM Length L Ch R = 1 ,63239   ,280.8,291.5,281.7
XS GIS Cut Line= 2
2379415.21819043621647.7999380152378823.95648704622044.688264336
#Sta/Elev= 30
       0 3753.74    39.1 3744.48      63 3737.83    87.3 3729.86   123.6 3715.58
   183.6 3700.25   206.5    3697   255.9 3694.79   270.4 3691.97     280 3692.67
   292.6  3691.3   335.13690.652   357.1 3689.34   376.43691.796   394.6  3691.9
   400.4 3692.91   419.7 3703.21   436.2 3707.35   453.4 3718.46   469.6    3725
   512.8 3746.69   522.3 3749.39   549.8 3759.55   559.4 3759.99     598  3767.8
   607.6 3768.51   617.2 3770.46   644.3 3772.33   679.9 3776.31   712.1 3777.03
#Mann= 7 ,-1 , 0
       0      .1       0   23.41     .12       0   335.1    .045       0
   376.4      .1       0  479.37     .12       0  634.45      .1       0
  681.01     .12       0
Bank Sta=335.1,376.4
XS Rating Curve= 0 ,0
Exp/Cntr=0.3,0.1

Type RM Length L Ch R = 1 ,62947   ,354.4,364.6,359.3
XS GIS Cut Line= 2
2379415.20795526621519.8711069512378546.20949983621823.736112202
#Sta/Elev= 30
       0 3768.22       9 3767.04    17.4 3763.21   115.8 3737.69   153.4 3726.57
   186.9 3719.27   229.3 3711.56   263.2 3701.89   285.3 3690.58   292.9 3688.29
   301.4 3687.08     331 3689.04   398.8  3687.5   424.2 3687.99     436 3685.85
   448.6 3684.27   481.8 3685.63   487.8 3686.64   500.5  3686.2   525.9 3687.22
   534.4 3686.29   547.1 3687.19   572.6 3685.59   589.5 3689.37   602.2 3694.23
   621.4 3699.22   640.1 3708.02   652.6 3711.97   699.7 3718.05   920.6 3719.22
#Mann= 5 ,-1 , 0
       0      .1       0   50.71     .12       0     436    .045       0
   481.8     .12       0  555.06      .1       0
#XS Ineff= 2 , 0
          339.93 3692.69
Permanent Ineff=
       F       F
Bank Sta=436,481.8
XS Rating Curve= 0 ,0
Exp/Cntr=0.3,0.1

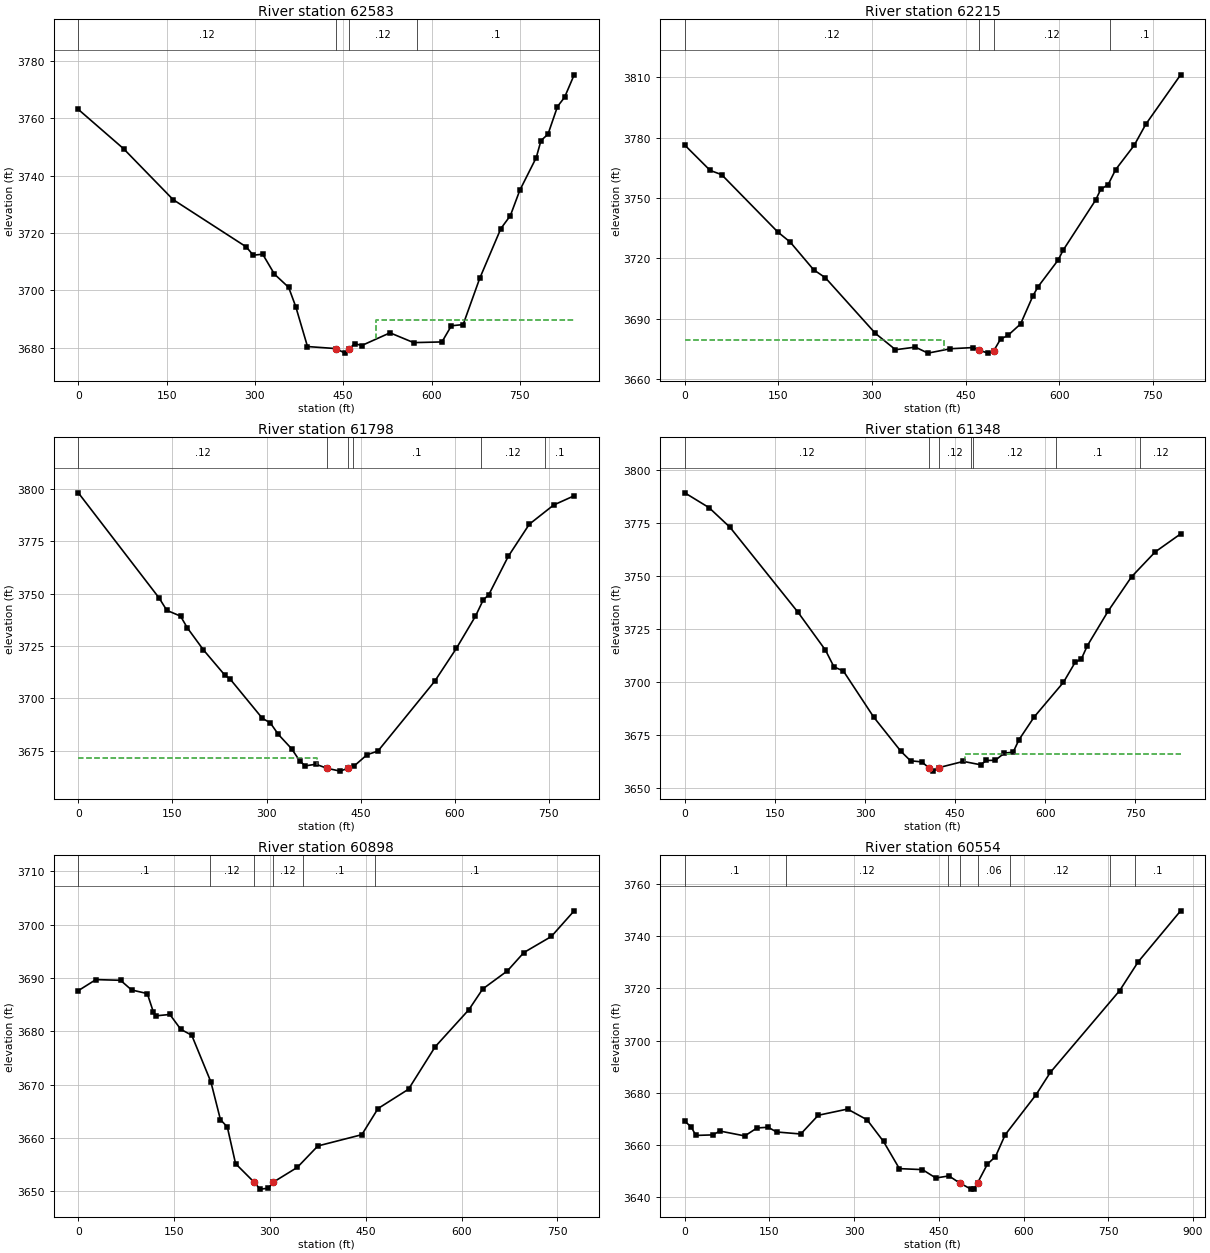
Type RM Length L Ch R = 1 ,62583   ,361.3,367.2,363.9
XS GIS Cut Line= 2
2379315.46727816621370.2826728752378474.43951127621416.839725742
#Sta/Elev= 30
       0 3763.13    76.8 3749.42     161 3731.64   285.2 3715.14   297.2 3712.23
   313.2 3712.58   333.2 3705.61   357.3    3701   369.3 3694.29   389.3 3680.34
   437.4 3679.63     453 3678.04   460.6 3679.59   469.4 3681.36   481.5  3680.7
   529.5 3685.13   569.6 3681.71   617.7 3681.95   633.7 3687.59   653.7 3688.01
   681.8 3704.11   717.8 3721.54   733.9 3726.03   749.9 3734.87   777.9 3746.31
   785.9 3752.23   797.9  3754.5     814 3764.15     826 3767.35   842.3 3775.21
#Mann= 4 ,-1 , 0
       0     .12       0   437.4    .045       0   460.6     .12       0
  574.51      .1       0
#XS Ineff= 2 , 0
                          505.48         3689.61
Permanent Ineff=
       F       F
Bank Sta=437.4,460.6
XS Rating Curve= 0 ,0
Exp/Cntr=0.3,0.1

Type RM Length L Ch R = 1 ,62215   ,417.3,417.2,407.2
XS GIS Cut Line= 2
2379179.17714538621099.7198261172378387.00976317621163.324506441
#Sta/Elev= 30
       0 3776.31    40.6 3763.73    59.1  3761.6   148.9 3733.12     169 3728.03
   206.4  3714.3   225.2 3710.33   305.4 3682.63   337.7 3674.48   369.6 3675.76
   389.7 3672.78   425.8 3674.97   461.9 3675.54   471.4 3674.24     486  3672.8
   495.43674.081   506.1 3679.75   518.1 3681.64   538.2 3687.31   558.2 3701.43
   566.2 3705.83   598.4 3719.11   606.4 3724.02   658.5 3748.97   666.6 3754.27
   678.6  3756.7   690.6 3764.15   720.3 3776.22   738.8 3786.66   794.7  3811.3
#Mann= 4 ,-1 , 0
       0     .12       0   471.4    .045       0   495.4     .12       0
  680.95      .1       0
#XS Ineff= 2 , 0
          415.43 3679.11
Permanent Ineff=
       F       F
Bank Sta=471.4,495.4
XS Rating Curve= 0 ,0
Exp/Cntr(USF)=0,0
Exp/Cntr=0.3,0.1

Type RM Length L Ch R = 1 ,61798   ,454.9,450.4,440.7
XS GIS Cut Line= 3
     2379045.575      620592.156     2378663.985      620734.439
2378308.45531277620877.210599747
#Sta/Elev= 30
       0 3798.11   128.7 3747.96   141.1 3742.03   162.9 3739.29   173.8 3733.66
   199.4 3723.18   233.5 3711.14   242.1 3709.21   293.3 3690.55     306 3688.35
   318.9 3682.82   339.9 3676.04   353.1 3670.15   361.6 3667.83   378.7 3668.62
   396.1 3666.72   417.2 3665.33   430.3 3666.73   438.8 3667.55   460.3 3673.17
   477.6  3674.9   568.1 3708.21   602.6 3723.88   633.1 3739.26   645.4 3746.97
   654.3  3749.5   685.3 3767.76   718.9 3783.13   757.7 3792.29   790.4 3796.69
#Mann= 6 ,-1 , 0
       0     .12       0   396.1    .045       0   430.3     .12       0
  438.03      .1       0  641.62     .12       0  743.42      .1       0
#XS Ineff= 2 , 0
          380.85  3671.6
Permanent Ineff=
       F       F
Bank Sta=396.1,430.3
XS Rating Curve= 0 ,0
Exp/Cntr=0.3,0.1

Type RM Length L Ch R = 1 ,61348   ,450.4,450.2,447.2
XS GIS Cut Line= 3
     2378639.925      620032.367     2378421.017      620382.689
     2378180.502      620717.215
#Sta/Elev= 30
       0 3789.41    40.4  3782.4    75.3 3773.11   188.5 3732.99   234.1 3715.14
   248.2 3707.25   263.9 3705.29   314.3 3683.56   359.7 3667.36   375.6 3662.92
   394.5 3662.38   405.63659.719   413.1 3658.03   423.2 3659.71   463.6 3662.62
   492.2 3661.03     502 3663.05   516.8 3663.16   531.6 3666.51   546.4    3667
   556.2 3672.89   581.4 3683.61   630.1 3699.95   649.8 3709.49   659.7 3710.86
   669.9 3717.25   704.3 3733.49   743.4 3749.76   782.8 3761.52   825.1 3770.02
#Mann= 7 ,-1 , 0
       0     .12       0   405.6    .045       0   423.2     .12       0
  476.99      .1       0  480.36     .12       0  617.64      .1       0
  758.28     .12       0
#XS Ineff= 2 , 0
                          465.69         3666.22
Permanent Ineff=
       F       F
Bank Sta=405.6,423.2
XS Rating Curve= 0 ,0
Exp/Cntr=0.3,0.1

Type RM Length L Ch R = 1 ,60898   ,326.2,344,345.6
XS GIS Cut Line= 3
2378112.62683839619973.186157707     2378009.757      620240.182
 2377829.4003197620696.081101321
#Sta/Elev= 30
       0 3687.61    27.5 3689.68    66.1 3689.55    83.3 3687.74     108 3687.06
   117.6 3683.56   121.9 3682.89   143.3 3683.14   160.4 3680.36   177.6 3679.24
   207.6 3670.48   222.5 3663.42   233.3 3662.03   246.2 3655.16   275.1  3651.7
   284.7 3650.38   297.6 3650.55   305.2 3651.68   342.9 3654.46   375.1 3658.48
   443.9 3660.59   469.3  3665.5     517 3669.12   558.7 3677.07   611.7 3684.06
   633.2 3687.92   671.9 3691.32   697.7 3694.76   740.7 3697.77   776.4 3702.58
#Mann= 6 ,-1 , 0
       0      .1       0  206.66     .12       0   275.1    .045       0
   305.2     .12       0  352.06      .1       0  465.16      .1       0
Bank Sta=275.1,305.2
XS Rating Curve= 0 ,0
Exp/Cntr=0.3,0.1

Type RM Length L Ch R = 1 ,60554   ,402.1,405.4,405.4
XS GIS Cut Line= 3
     2377977.519      619824.7682377846.76171598620139.675633672
2377406.17783839620446.843142985
#Sta/Elev= 30
       0 3669.07      11 3667.05    19.6 3663.69    49.9  3663.9    61.9 3665.38
   106.2  3663.5   127.9 3666.55   147.6 3666.81   162.5 3665.01   205.4 3664.24
   236.3  3671.4   288.2 3673.77   322.8 3669.67   351.9 3661.38     380 3650.99
   420.9 3650.61   444.5 3647.41   467.8  3648.2   486.5 3645.54   506.8 3643.15
   511.7  3643.2   518.6 3645.57     536 3652.75   550.2 3655.57   567.4 3663.95
     622 3679.24   647.3 3687.78   770.1 3719.07     803 3730.11   878.1  3749.6
#Mann= 8 ,-1 , 0
       0      .1       0  178.42     .12       0  466.44     .06       0
   486.5    .045       0   518.6     .06       0  576.64     .12       0
  753.65      .1       0  797.03      .1       0
Bank Sta=486.5,518.6
XS Rating Curve= 0 ,0
Exp/Cntr=0.3,0.1

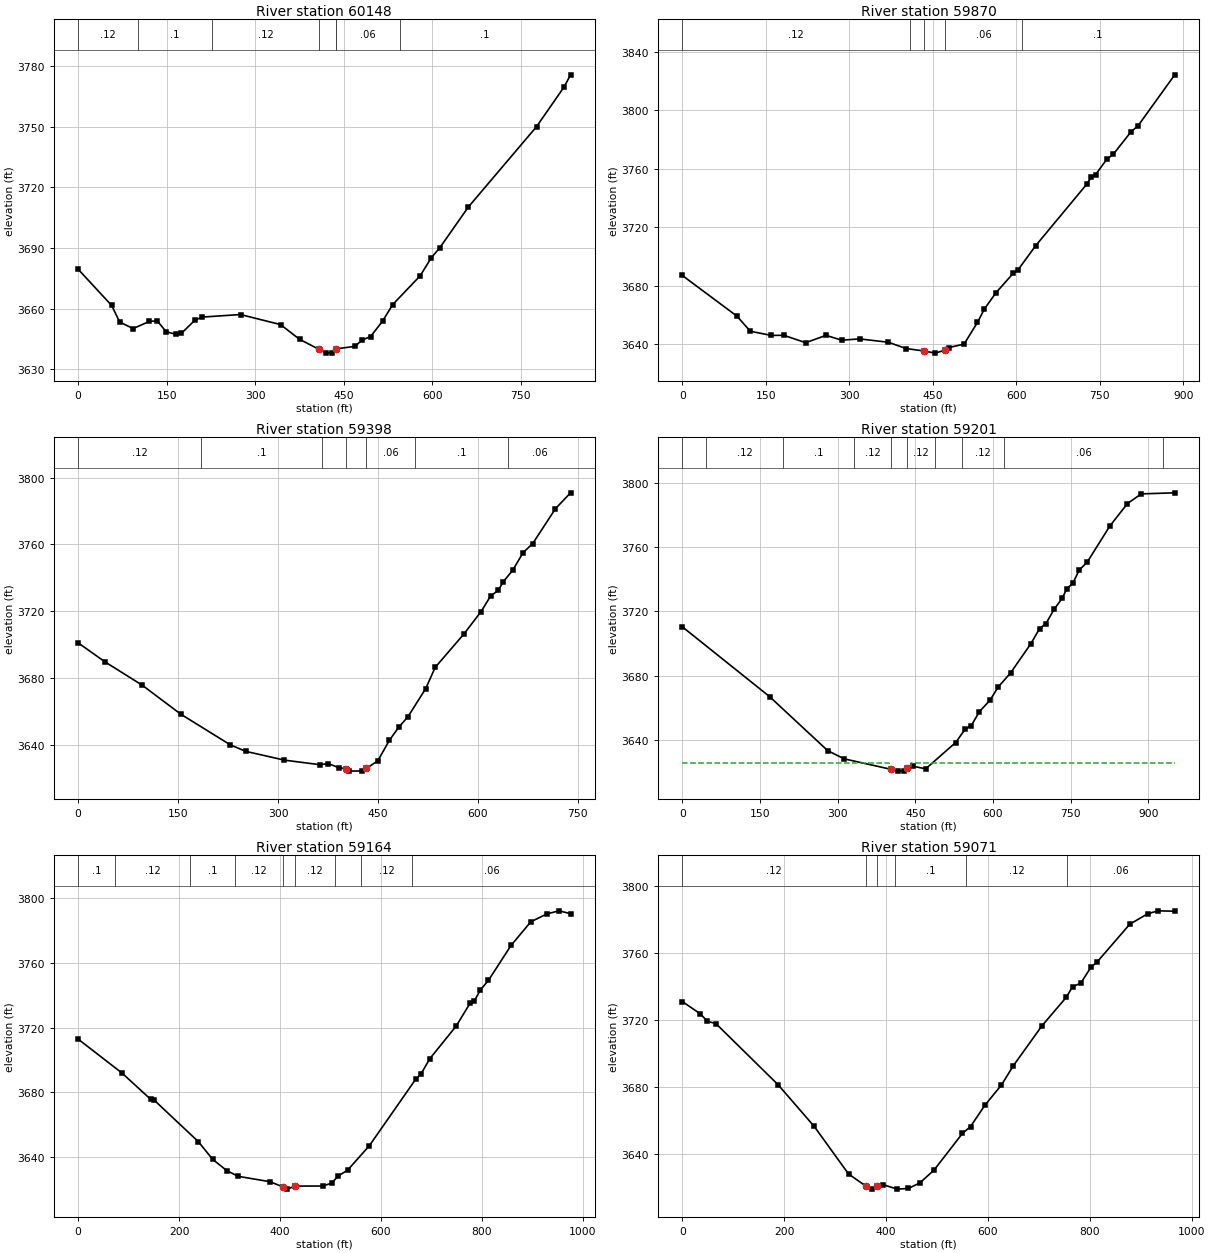
Type RM Length L Ch R = 1 ,60148   ,268.5,278.4,285.4
XS GIS Cut Line= 3
     2377876.704      619692.066     2377503.841      619893.632
2377153.59997942620107.897026433
#Sta/Elev= 30
       0 3679.48    56.8 3661.57    70.4 3653.36    93.2 3650.16   120.5 3653.67
   134.1 3654.02   148.9 3648.61   165.9 3647.29     175  3647.8   197.8  3654.3
   210.1 3655.84   275.1 3657.09     343 3652.12   375.1 3644.86   407.9 3639.91
   420.6 3638.01   429.8 3638.28   437.2 3640.13   469.2 3641.36   480.8 3644.42
   495.5 3646.21   515.8 3653.82     533 3662.01   579.6 3676.26   598.6 3685.25
   612.7 3690.05   661.2 3710.26   776.8 3750.01   823.7 3769.75   834.4 3775.63
#Mann= 7 ,-1 , 0
       0     .12       0  100.71      .1       0  226.88     .12       0
   407.9    .045       0   437.2     .12       0  437.47     .06       0
  544.77      .1       0
Bank Sta=407.9,437.2
XS Rating Curve= 0 ,0
Exp/Cntr=0.3,0.1

Type RM Length L Ch R = 1 ,59870   ,456.6,471.7,479
XS GIS Cut Line= 3
2377860.80923474619635.1902781622377414.29223474619651.760278162
2376976.53320013619667.855713027
#Sta/Elev= 30
       0 3686.88    98.1  3659.1   122.1 3648.77   159.9  3645.9   182.2 3645.99
   221.7 3640.93   258.2 3645.95   286.3 3642.65   318.4 3643.52   370.3 3641.22
   402.3 3636.91   434.8 3635.23   454.4 3633.79   472.2 3635.84   478.4 3637.56
   506.4 3639.98   530.4 3654.81   542.8 3663.96   563.6 3675.05   594.5 3688.33
   602.5 3690.31   634.7 3707.12   726.6 3749.24   734.6 3753.95   742.6 3755.81
   762.6  3766.3   774.6 3769.83   806.6 3785.29   818.6 3789.08   884.9 3824.12
#Mann= 5 ,-1 , 0
       0     .12       0  409.46     .06       0   434.8    .045       0
   472.2     .06       0  609.64      .1       0
Bank Sta=434.8,472.2
XS Rating Curve= 0 ,0
Exp/Cntr=0.3,0.1

Type RM Length L Ch R = 1 ,59398   ,184.4,196.8,203.2
XS GIS Cut Line= 3
     2377889.802      619457.541     2377542.235      619218.572
2377284.38480194619033.770356893
#Sta/Elev= 30
       0 3701.18      40 3689.86    96.2 3675.83   154.2 3658.46   228.5 3640.14
   251.5 3636.28   309.5 3631.03   362.9 3628.29   375.2 3628.99     392 3626.41
   401.8 3625.99   407.1 3624.45   426.1 3624.58   432.7 3626.03   449.9  3630.7
   467.1 3642.92   481.4  3650.8     495 3656.99   521.5 3673.74   535.9 3686.53
   578.9 3706.43   604.7 3719.87     619 3729.15   630.5 3732.58   637.7 3737.54
   652.5 3744.75   667.7  3755.1   682.1 3760.47   716.4 3781.43     739 3790.89
#Mann= 7 ,-1 , 0
       0     .12       0  184.55      .1       0  366.33     .06       0
   401.8    .045       0   432.7     .06       0  505.33      .1       0
  645.39     .06       0
Bank Sta=401.8,432.7
XS Rating Curve= 0 ,0
Exp/Cntr=0.5,0.3

Type RM Length L Ch R = 1 ,59201   ,39,37.5,37.3
XS GIS Cut Line= 4
2377942.87159607619382.0866732192377720.52236004619206.111655017
2377636.57337682618976.5211560742377214.23984152618950.644614837
#Sta/Elev= 30
       0 3710.39   168.5 3667.02   280.7 3633.45   312.5 3628.35   402.8 3621.84
   416.9  3620.7   427.8 3620.93   433.7 3622.43   444.6 3623.82   470.1 3622.13
     528 3638.49   546.4 3646.81   557.9 3648.88   573.9 3657.72     594 3664.66
     610 3672.92     634 3681.74   673.4 3699.97   690.1 3709.33   702.2 3712.34
   718.2 3721.33   734.2 3728.33   742.2 3733.86   754.3 3737.45   766.3 3745.53
   782.3 3750.73   825.8 3773.05   859.8 3787.01   886.5 3793.03   951.1 3793.68
#Mann= 10 ,-1 , 0
       0      .1       0   46.33     .12       0  193.54      .1       0
  331.78     .12       0   402.8    .045       0   433.7     .12       0
  488.05      .1       0  540.14     .12       0  622.11     .06       0
  927.56     .12       0
#XS Ineff= 2 , 0
             400    3626     442            3626
Permanent Ineff=
       F       F
Bank Sta=402.8,433.7
XS Rating Curve= 0 ,0
Exp/Cntr=0.5,0.3

Type RM Length L Ch R = 1 ,59164   ,97.4,92.6,85.5
XS GIS Cut Line= 4
2377958.34006662619365.7623006962377750.87850456619198.384822519
2377665.84304834 618945.16237363 2377224.0783027618932.399345987
#Sta/Elev= 30
       0 3712.96    86.9    3692   143.4 3675.83   151.1 3675.11   237.9 3649.66
   266.6 3638.63   294.7 3631.65   317.2 3628.15     380 3624.84   405.2  3621.7
   413.7 3620.25   430.3 3622.14   485.4 3622.16   502.3 3624.04   515.8 3628.51
   533.7 3631.92   576.8 3647.02   668.8 3688.17   678.8 3691.18   696.8 3700.88
   748.9 3721.02   776.9 3735.33   784.9 3736.51   796.9 3743.34   812.9 3749.28
   857.8 3770.93   896.9 3785.49   928.9  3790.4     953 3792.27   975.6 3790.47
#Mann= 9 ,-1 , 0
       0      .1       0   73.59     .12       0  222.33      .1       0
  311.52     .12       0   405.2    .045       0   430.3     .12       0
  509.43      .1       0  560.54     .12       0  661.67     .06       0
Bank Sta=405.2,430.3
XS Rating Curve= 0 ,0
Exp/Cntr=0.5,0.3

Type RM Length L Ch R = 1 ,59071   ,187.3,178,168.1
XS GIS Cut Line= 3
2378034.03375024619249.649533207 2377648.6215273618877.216432517
 2377218.5125951618902.468861895
#Sta/Elev= 30
       0 3731.15    35.4 3723.79    49.1 3719.34    65.8 3718.01   188.2 3681.37
   258.9 3656.52   326.3 3628.11   360.6 3620.78   371.7 3619.08   382.8 3620.74
   393.9 3621.73   421.8 3619.02     444 3619.42   466.3 3622.74   494.1 3630.36
   549.9 3652.29   565.9 3656.44   593.9 3669.11   626.4 3681.19     650 3692.83
   706.1 3716.65   754.2 3733.83   766.2 3740.05   782.3 3742.11   802.3 3751.69
   814.3 3754.77   878.4 3777.36     914 3783.69   934.5 3785.39   966.8 3785.16
#Mann= 6 ,-1 , 0
       0     .12       0   360.6    .045       0   382.8     .12       0
  418.42      .1       0  556.31     .12       0  755.99     .06       0
Bank Sta=360.6,382.8
XS Rating Curve= 0 ,0
Exp/Cntr=0.3,0.1

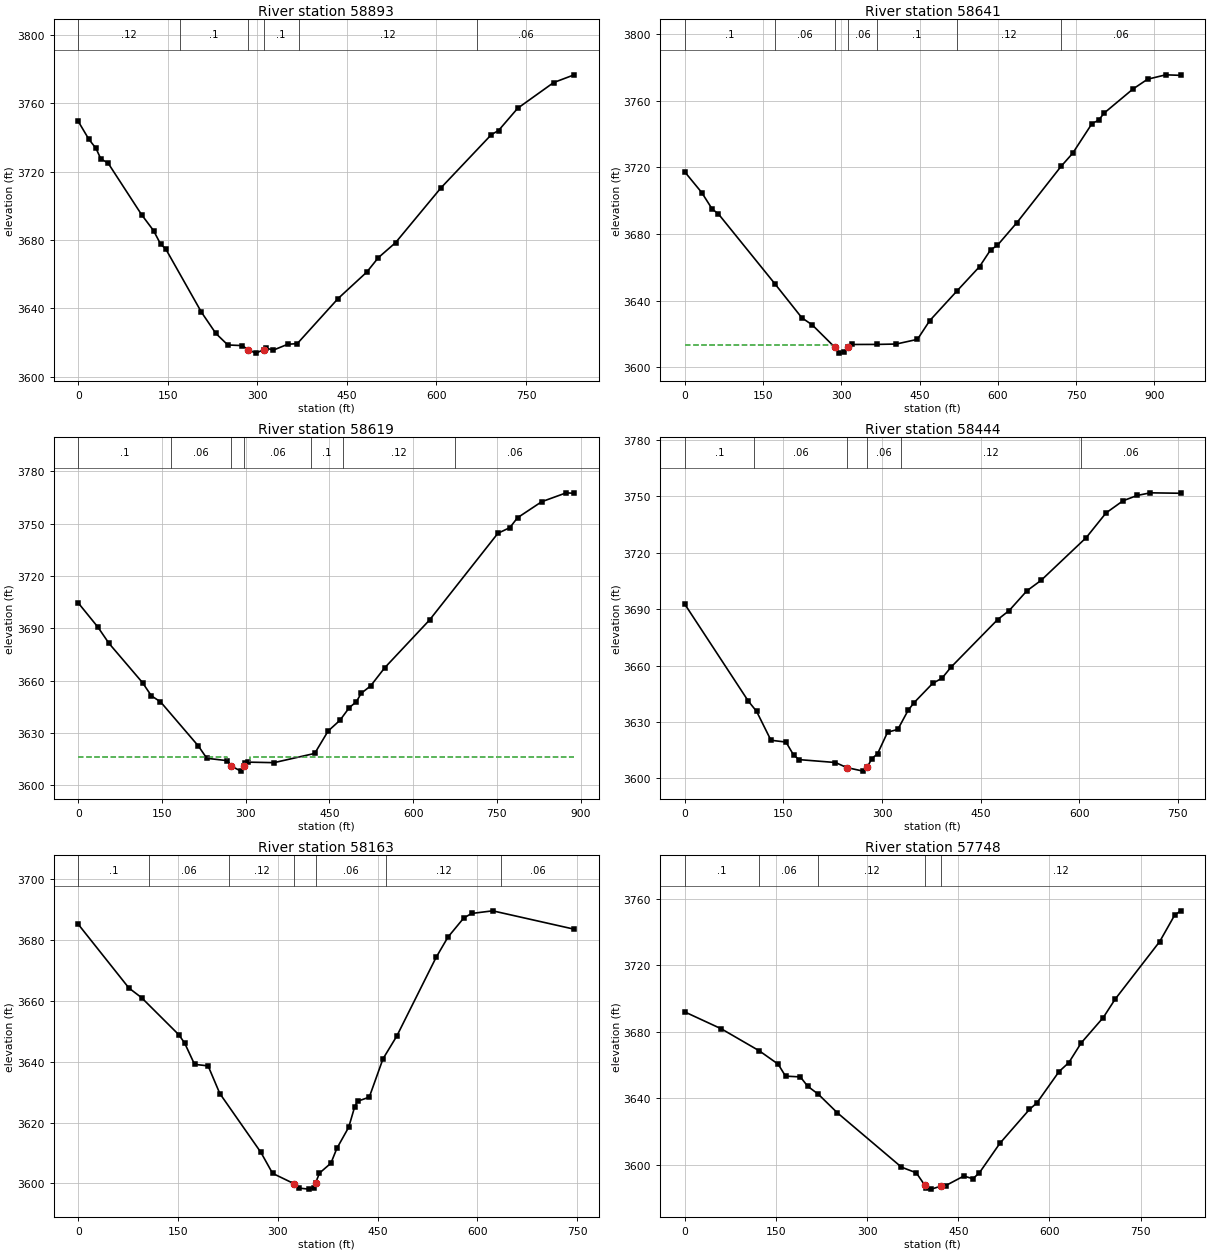
Type RM Length L Ch R = 1 ,58893   ,273.3,251.9,239
XS GIS Cut Line= 2
2378088.36502993618797.3093444132377260.40354185618864.857945466
#Sta/Elev= 30
       0 3749.24    17.5 3738.93    29.7 3733.47    37.7 3727.39    49.8 3724.97
     106 3694.79     126 3685.51   138.1 3677.43   146.1 3674.99   206.3 3637.81
   230.4 3625.44   250.4 3618.71   274.5 3618.32     285 3615.85   297.2 3613.93
   310.3 3615.86   314.7 3616.84   326.7 3615.69   350.8  3619.1   366.8 3619.48
   435.1 3645.79   483.2 3661.25   502.6 3669.69   531.4 3678.44   607.6  3710.5
   691.9 3741.54     704 3743.97   736.1 3756.97   796.3 3771.98   830.7  3776.5
#Mann= 6 ,-1 , 0
       0     .12       0   169.7      .1       0     285    .045       0
   310.3      .1       0  368.97     .12       0  667.86     .06       0
Bank Sta=285,310.3
XS Rating Curve= 0 ,0
Exp/Cntr(USF)=0,0
Exp/Cntr=0.5,0.3

Type RM Length L Ch R = 1 ,58641   ,22.6,22.6,22.7
XS GIS Cut Line= 3
2377729.93853701618294.4943046382377735.13252864618671.846541136
     2377195.925      618865.154
#Sta/Elev= 30
       0 3717.32    32.4 3704.95    52.4 3695.04    64.4 3692.08   172.4  3650.2
   224.4 3629.66   244.4 3625.36     2873612.108   296.4 3608.45   304.4 3608.85
   312.4 3612.23   320.4 3613.65   368.2 3613.69   405.1 3613.91   445.8 3616.72
   469.4 3627.97   520.8 3645.54   564.8  3660.4     586 3670.49     599 3673.19
   636.6 3686.91     721 3720.64   743.2 3728.48   780.4 3746.39     793 3748.37
   803.5 3752.65   858.6 3767.07   886.8 3773.02   921.7 3775.66   950.2 3775.35
#Mann= 7 ,-1 , 0
       0      .1       0   172.4     .06       0     287    .045       0
   312.4     .06       0   368.2      .1       0   520.8     .12       0
     721     .06       0
#XS Ineff= 2 , 0
          284.33 3613.43
Permanent Ineff=
       F       F
Bank Sta=287,312.4
XS Rating Curve= 0 ,0
Exp/Cntr=0.5,0.3

Type RM Length L Ch R = 1 ,58619   ,168.7,175.1,177.8
XS GIS Cut Line= 3
 2377700.4763499618303.9596217452377714.65910471618654.129591179
2377205.43405158618827.651415789
#Sta/Elev= 30
       0 3704.54      35 3690.75      55 3681.39     115  3658.9     131  3651.3
   147.1 3647.96   215.1 3622.57   230.2 3615.54   267.2 3614.17   274.3 3611.05
   291.2 3608.18   296.9 3610.95   299.2 3612.85   303.2 3613.34   350.5 3613.03
   423.5 3618.32   447.6 3631.18   468.7  3637.3   485.6 3644.62   498.3 3647.98
   506.7 3652.77   523.6 3656.99     549 3667.44   629.3 3694.81   751.8 3744.53
     773 3747.72   786.9 3753.42   830.1 3762.59   874.2 3767.71   888.4 3767.43
#Mann= 7 ,-1 , 0
       0      .1       0  165.59     .06       0   274.3    .045       0
   296.9     .06       0  416.17      .1       0  473.33     .12       0
  674.79     .06       0
#XS Ineff= 2 , 0
          266.78 3616.37  308.47         3616.14
Permanent Ineff=
       F       F
Bank Sta=274.3,296.9
XS Rating Curve= 0 ,0
Exp/Cntr=0.5,0.3

Type RM Length L Ch R = 1 ,58444   ,277.6,280.5,280.9
XS GIS Cut Line= 3
2377640.10339649618287.9879824582377507.79363158618645.891438598
2377161.19047018618782.523677193
#Sta/Elev= 30
       0  3692.6    96.7 3641.06   109.2 3635.65     131 3620.31   153.9 3619.34
   165.4 3612.49   173.7 3610.02   229.1 3608.48   246.2 3605.81   271.1  3603.9
   277.3 3605.92   284.6  3610.6   293.1 3613.09   308.4 3624.58     324 3626.08
   339.6 3636.18   348.5 3640.21   376.9  3650.5   391.3 3653.32   404.7 3659.08
   475.7  3684.4   493.4 3689.24   520.3 3699.73   541.8 3705.25   610.6 3728.02
   640.7 3741.12   666.5 3747.56     688 3750.39   708.1 3751.79   754.1 3751.56
#Mann= 6 ,-1 , 0
       0      .1       0  105.37     .06       0   246.2    .045       0
   277.3     .06       0  328.66     .12       0  602.88     .06       0
Bank Sta=246.2,277.3
XS Rating Curve= 0 ,0
Exp/Cntr=0.3,0.1

Type RM Length L Ch R = 1 ,58163   ,400.5,414.8,428.3
XS GIS Cut Line= 3
2377433.42210253618125.7700458232377242.65971758618539.219101159
2376986.56945568618675.383177263
#Sta/Elev= 30
       0  3685.1    76.1 3664.18      95 3661.04     151 3648.86   159.8 3646.13
   174.7 3639.13   195.1 3638.62   212.7 3629.54   274.4 3610.23     292 3603.33
     324 3599.95   331.6 3598.48   346.5 3598.14   353.7 3598.56   356.7 3600.19
   362.5  3603.4   379.7 3606.66   388.7 3611.54   406.5 3618.48   415.3 3625.08
   419.7    3627   437.4 3628.35     458 3640.94   478.7 3648.39   537.8 3674.23
   555.6 3680.89   579.3 3687.16   591.1 3688.68   622.9 3689.55   745.4 3683.52
#Mann= 7 ,-1 , 0
       0      .1       0  106.88     .06       0  226.78     .12       0
     324    .045       0   356.7     .06       0  462.58     .12       0
  635.14     .06       0
Bank Sta=324,356.7
XS Rating Curve= 0 ,0
Exp/Cntr=0.3,0.1

Type RM Length L Ch R = 1 ,57748   ,440,450,453.2
XS GIS Cut Line= 3
2377422.06546316 618096.48711579     2377022.211       618165.47
     2376616.987      618227.877
#Sta/Elev= 30
       0  3691.9    60.2 3681.72   122.7 3668.46   153.6 3660.47   165.7 3653.26
   190.1 3652.79   202.2 3647.17   219.6  3642.4     251 3631.18   356.5 3598.46
   380.9 3595.04   394.93587.541   397.1 3586.12   405.8 3585.23   421.4 3587.04
   429.5 3587.39   459.1 3593.12     474 3591.49   484.7 3595.06   518.5 3612.85
   567.1 3633.23   579.2 3637.09   615.7 3655.98   631.9 3661.42   652.1  3673.2
   688.5 3688.53   708.1  3699.6   781.4 3734.29   805.9 3750.14   815.8 3752.78
#Mann= 5 ,-1 , 0
       0      .1       0   122.7     .06       0   219.6     .12       0
   394.9    .045       0   421.4     .12       0
Bank Sta=394.9,421.4
XS Rating Curve= 0 ,0
Exp/Cntr=0.3,0.1

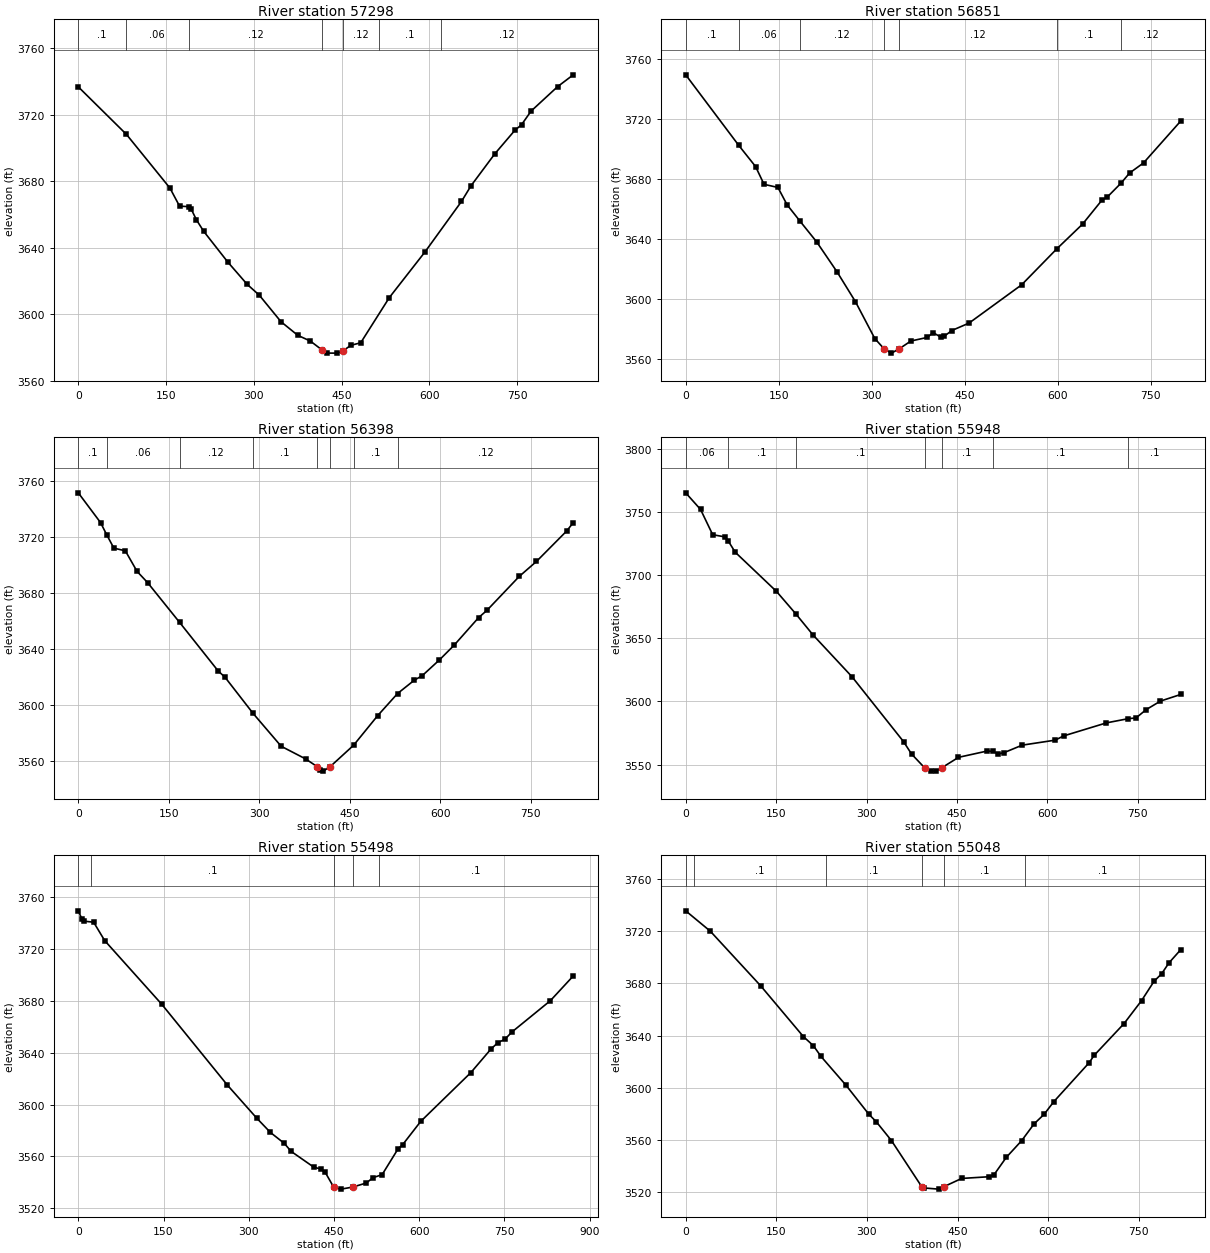
Type RM Length L Ch R = 1 ,57298   ,454.8,447.3,436.2
XS GIS Cut Line= 3
2377434.50330464 617841.26810054     2377009.846      617733.218
     2376612.566      617641.032
#Sta/Elev= 30
       0  3736.8    82.3 3708.18   156.6  3675.9   173.1    3665   189.6 3664.68
   192.6  3663.5     202 3656.72   214.4 3649.82   255.7 3631.28   288.7 3617.92
   309.3 3611.44   346.5 3595.43   375.3 3587.22   396.6 3583.81   417.1 3578.32
   424.9 3576.56   441.4 3576.54   452.7 3578.01   466.2 3581.28   482.7 3582.76
   531.7 3610.01   592.7 3637.51   654.9  3667.8   671.3 3677.29   711.9 3696.48
     746 3710.56   757.6 3714.03     774 3722.23   819.1 3736.88     846 3744.03
#Mann= 7 ,-1 , 0
       0      .1       0   80.72     .06       0  189.01     .12       0
   417.1    .045       0   452.7     .12       0  513.21      .1       0
  620.54     .12       0
Bank Sta=417.1,452.7
XS Rating Curve= 0 ,0
Exp/Cntr=0.3,0.1

Type RM Length L Ch R = 1 ,56851   ,453.3,453,446.2
XS GIS Cut Line= 2
2377327.91385185617181.0439610142376613.07715774617535.670578568
#Sta/Elev= 30
       0 3749.72    85.2 3702.79   112.7 3688.46   126.3 3676.62   148.7 3674.53
   163.4    3663   184.2 3652.08   211.2 3638.16     244 3618.19   273.7 3598.25
   304.9 3573.64   320.13566.684   331.7 3563.92   344.1 3566.75     363    3572
   389.8 3574.44   398.7 3577.65   411.1 3574.65   416.6 3575.11     429 3579.01
   456.8 3583.97   541.6 3609.53   598.2  3633.5   639.8 3650.04   671.1 3666.06
     680 3668.25   702.3  3677.6   715.7 3684.18   738.1  3690.9     798 3718.82
#Mann= 7 ,-1 , 0
       0      .1       0    85.2     .06       0   184.2     .12       0
   320.1    .045       0   344.1     .12       0   598.2      .1       0
   702.3     .12       0
Bank Sta=320.1,344.1
XS Rating Curve= 0 ,0
Exp/Cntr=0.3,0.1

Type RM Length L Ch R = 1 ,56398   ,447.7,449.9,452
XS GIS Cut Line= 3
     2377017.528        616735.4     2376720.492      617016.991
     2376426.858      617305.376
#Sta/Elev= 30
       0 3751.72    36.9 3730.42    46.9 3721.87      59 3712.11      78 3710.21
    97.5 3695.45   114.8  3687.5   167.9 3659.01   231.8 3624.26   243.5 3619.59
     290 3593.72   336.5 3570.24   377.2 3561.14   396.3  3555.6   400.7 3553.38
   406.2 3552.44   417.5 3555.55   456.6 3570.98   496.7 3592.26   529.5    3608
   557.5 3617.63   570.3 3620.74   598.6 3631.94   623.2 3642.55     664  3662.4
   677.8 3667.59   731.3 3691.86   759.8 3702.56   809.8 3724.31   820.9 3730.36
#Mann= 8 ,-1 , 0
       0      .1       0    46.9     .06       0   167.9     .12       0
     290      .1       0   396.3    .045       0   417.5     .12       0
   456.6      .1       0   529.5     .12       0
Bank Sta=396.3,417.5
XS Rating Curve= 0 ,0
Exp/Cntr=0.3,0.1

Type RM Length L Ch R = 1 ,55948   ,440.8,449.8,460.6
XS GIS Cut Line= 3
      2376789.63      616423.369     2376456.019      616659.701
     2376106.304      616878.125
#Sta/Elev= 30
       0 3765.34    24.7 3752.13    44.8 3732.14    64.9 3730.44    70.6 3727.15
    82.2 3718.26   150.6 3687.22   182.2 3669.69   211.2 3652.73     276 3619.54
   361.4 3568.17   374.7 3558.36   397.23547.004   406.3 3544.78     415 3544.85
   424.5 3547.32   452.6 3555.71   499.9 3560.68   509.4 3560.42   518.8 3558.46
   528.2 3559.44   558.3 3565.37   613.1 3569.34   626.9 3572.67     698 3583.02
   734.3 3586.36   747.1 3586.94     764 3593.52   787.6 3600.27   821.2 3605.53
#Mann= 7 ,-1 , 0
       0     .06       0    70.6      .1       0   182.2      .1       0
   397.2    .045       0   424.5      .1       0   509.4      .1       0
   734.3      .1       0
Bank Sta=397.2,424.5
XS Rating Curve= 0 ,0
Exp/Cntr=0.3,0.1

Type RM Length L Ch R = 1 ,55498   ,446.5,450,453.9
XS GIS Cut Line= 3
2376729.06247719616300.708866667     2376266.934      616281.313
     2375858.527      616267.157
#Sta/Elev= 30
       0  3749.4     6.3 3743.15    10.3 3741.42      27 3740.63    46.5 3726.43
   146.8 3677.38   262.5 3614.95   313.9 3589.57   338.2 3578.45   362.6 3570.03
   374.6 3563.86   414.7 3551.62   426.7 3550.31   434.7 3547.62   449.7 3536.14
   462.5 3534.74   482.7  3536.3   506.8 3539.44   518.8 3543.57   534.8 3545.93
   562.8 3565.79   570.8 3568.97   602.8 3587.02   690.9  3624.6   726.9 3643.07
   738.9 3647.81   750.9 3650.31   762.9 3655.82   830.9 3680.09   871.2 3699.17
#Mann= 5 ,-1 , 0
       0     .06       0      22      .1       0   449.7    .045       0
   482.7      .1       0  528.88      .1       0
Bank Sta=449.7,482.7
XS Rating Curve= 0 ,0
Exp/Cntr=0.3,0.1

Type RM Length L Ch R = 1 ,55048   ,426.7,422,417.5
XS GIS Cut Line= 3
     2376765.853      615966.514     2376372.378      615853.168
     2375976.155      615749.181
#Sta/Elev= 30
       0 3735.63    40.7 3720.04     124 3678.21   194.7  3639.3   211.4 3632.23
   223.9 3624.06   265.5 3601.86   302.9 3579.87   315.7 3573.83   340.4 3559.63
   390.4 3524.39   394.5 3523.28   418.4 3522.38   427.7 3524.35   456.7 3530.57
   502.1 3531.88   510.4 3533.53   530.6 3546.75   555.9 3559.48   576.6 3572.42
   593.1 3579.69   609.2 3589.42   667.6 3619.22   675.8 3624.82   725.5 3649.29
   754.4 3666.84   775.1 3681.67   787.5 3687.34   799.9 3695.85   819.1  3705.8
#Mann= 6 ,-1 , 0
       0     .06       0   13.32      .1       0  232.99      .1       0
   390.4    .045       0   427.7      .1       0  560.85      .1       0
Bank Sta=390.4,427.7
XS Rating Curve= 0 ,0
Exp/Cntr=0.3,0.1