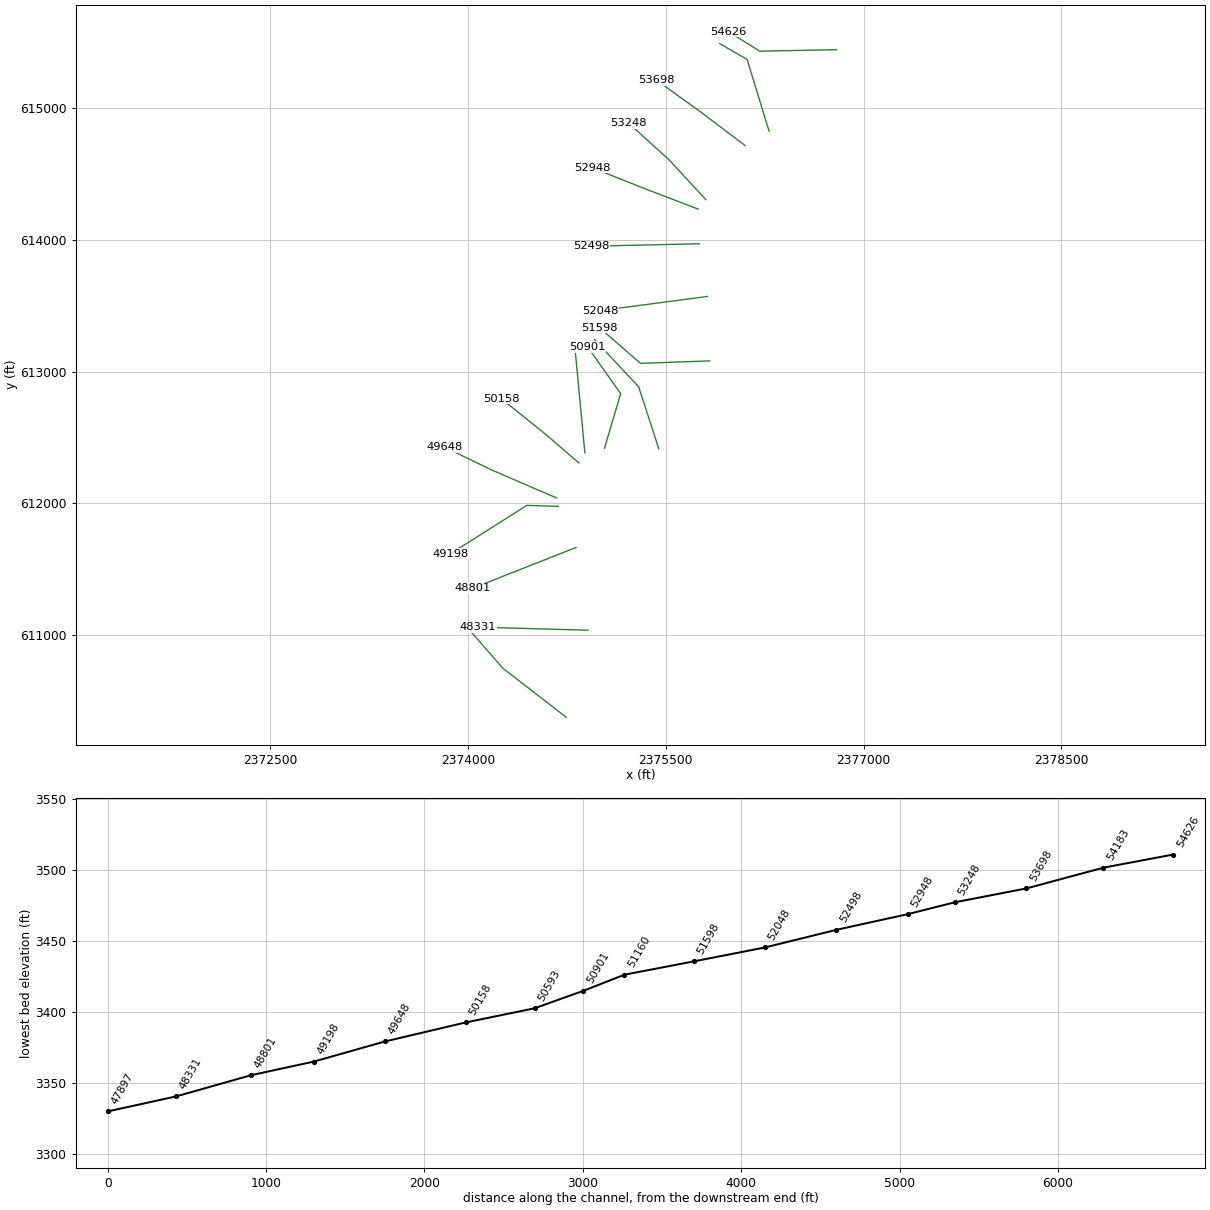
HEC-RAS study BIGRN.prj: BIGRN

--- BIGRN.g01 (geometry) --- (continued)

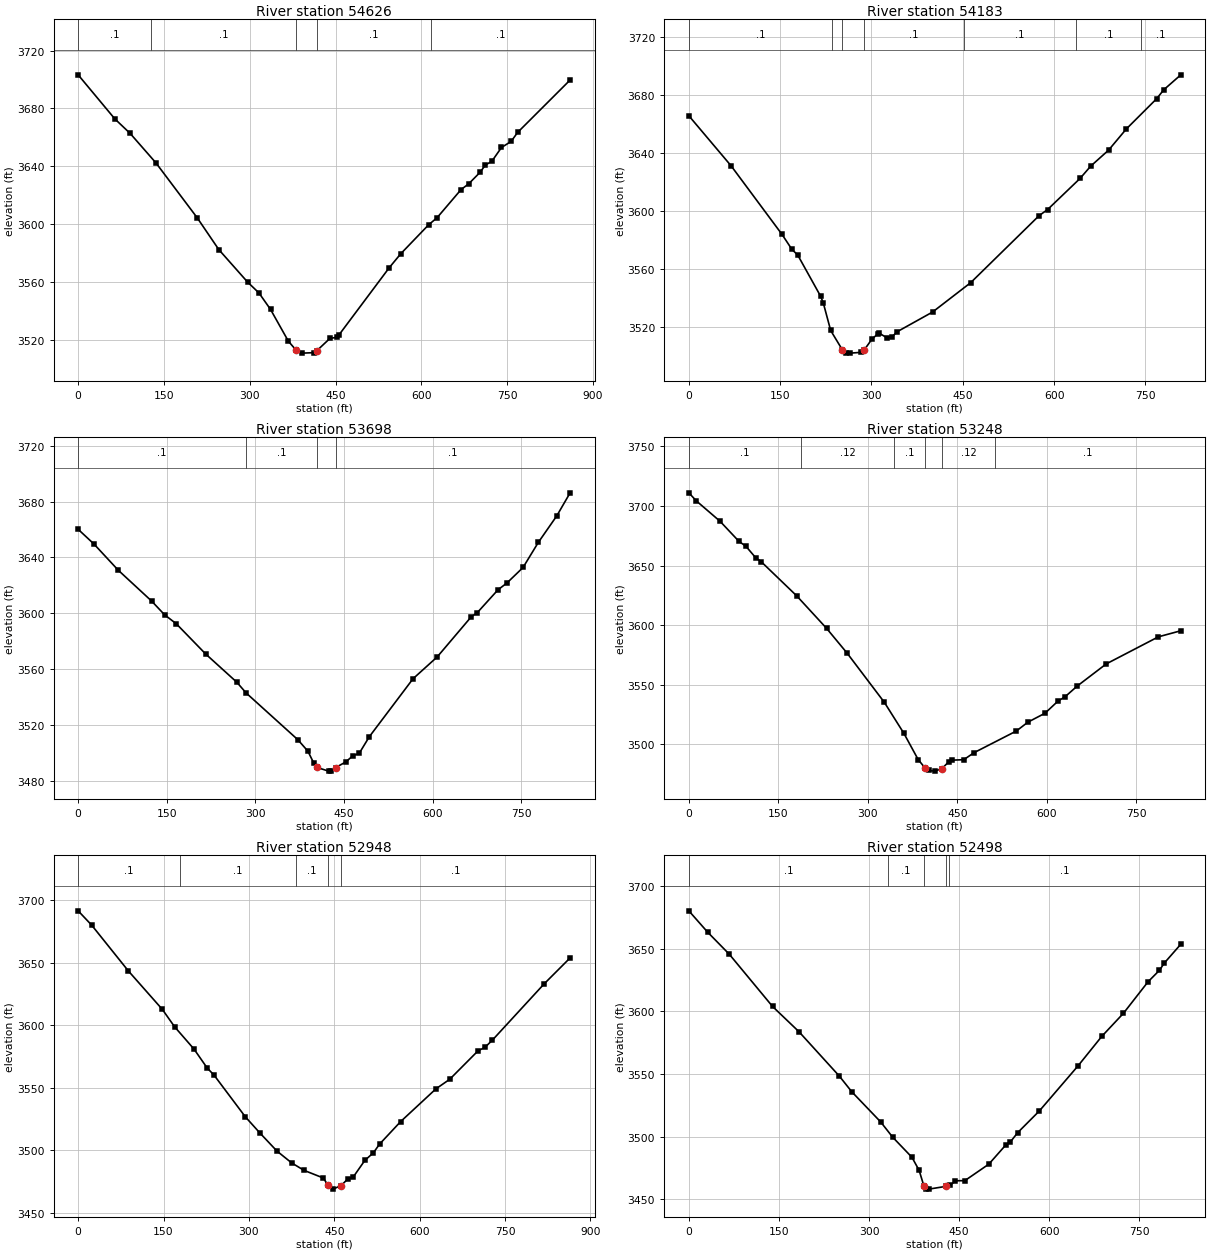
Type RM Length L Ch R = 1 ,54626   ,464.1,442.8,418.9
XS GIS Cut Line= 3
     2376794.766      615441.8072376213.52962807615430.129470176
     2375976.869      615577.332
#Sta/Elev= 30
       0 3703.23      64 3672.86      91 3662.73     136 3642.42   208.1 3604.52
     246 3582.49   296.1 3560.16   316.1 3552.59   336.3 3541.24   367.6 3519.22
   380.8  3513.2   392.1 3511.02   412.1 3511.34   417.6 3512.81   440.1 3521.16
   452.1 3521.96   456.1 3523.64   544.1 3570.13   564.1 3579.68   612.9 3599.71
   627.5 3604.54   669.4 3623.96   682.7 3627.92     703 3636.02   711.8 3640.91
   723.3 3643.53   740.1 3653.05     757 3657.23   768.3 3663.44   860.1 3699.65
#Mann= 5 ,-1 , 0
       0      .1       0  126.64      .1       0   380.8    .045       0
   417.6      .1       0  617.46      .1       0
Bank Sta=380.8,417.6
XS Rating Curve= 0 ,0
Exp/Cntr=0.3,0.1

Type RM Length L Ch R = 1 ,54183   ,469.7,485.4,489.9
XS GIS Cut Line= 3
2376283.07065965614824.0405122822376116.72863168 615367.77020256
     2375909.292      615487.627
#Sta/Elev= 30
       0 3665.53    69.5 3630.94   153.1 3583.63   169.1 3573.46   178.9 3569.39
   216.3 3541.12   220.8 3536.47     233 3517.36   252.4 3503.85   258.1 3501.88
   265.2 3501.73   283.2 3502.27   287.6 3503.62   300.4 3511.17     310 3514.92
   313.2 3515.42   325.1 3512.34   333.4  3512.7   341.8  3516.4   400.4 3530.09
   463.1 3550.38   575.5 3596.64   589.4 3600.83   642.6 3622.25   660.2 3630.78
   689.5 3641.79   718.7 3656.43   768.5 3677.29   780.2 3683.47   808.2 3693.78
#Mann= 7 ,-1 , 0
       0      .1       0  235.82      .1       0   252.4    .045       0
   287.6      .1       0  452.56      .1       0  636.05      .1       0
   742.3      .1       0
Bank Sta=252.4,287.6
XS Rating Curve= 0 ,0
Exp/Cntr=0.3,0.1

Type RM Length L Ch R = 1 ,53698   ,449.4,450.1,446.6
XS GIS Cut Line= 3
2376100.98379158614714.700336843     2375761.504      614971.229
2375431.06042143615209.464526789
#Sta/Elev= 30
       0 3660.15    26.9 3649.57      68 3630.85   124.5 3608.78   146.3 3599.01
   166.2 3592.56   215.9 3570.95   268.5 3550.81   284.4 3543.08   371.9 3509.64
   388.9 3501.47   398.9 3492.91   404.4 3489.81   423.9 3487.15   428.9 3487.39
     436 3489.73     453 3493.67   464.5 3497.95   475.9 3499.92   493.1 3511.85
     567 3553.26   607.8 3568.82   665.6  3597.6   675.5 3600.42   710.9 3616.92
   725.9 3621.73   753.2 3632.83     779 3650.74   810.3 3669.75   832.9 3686.25
#Mann= 4 ,-1 , 0
       0      .1       0  284.32      .1       0   404.4    .045       0
     436      .1       0
Bank Sta=404.4,436
XS Rating Curve= 0 ,0
Exp/Cntr=0.3,0.1

Type RM Length L Ch R = 1 ,53248   ,294.8,299.7,303.6
XS GIS Cut Line= 3
     2375803.359      614304.474     2375524.974      614605.843
     2375218.146      614884.179
#Sta/Elev= 30
       0 3710.99    12.7 3704.17    52.3 3687.12    84.2 3670.16    95.6 3666.18
   112.2  3656.4     121 3653.32   180.5 3624.66   230.8 3597.28   265.4 3576.36
   327.7 3535.13   360.5 3509.06   384.3 3487.17   395.9 3480.06   401.8 3477.97
   411.8 3477.44   424.1 3479.51   435.6 3485.31   441.6 3486.65   460.7 3487.03
   478.1 3492.96   548.8 3511.08   568.3 3518.56   596.9 3526.02   618.5 3536.14
   630.6 3539.88   650.9 3548.84   699.5 3567.41   786.9 3590.15   824.5 3595.24
#Mann= 6 ,-1 , 0
       0      .1       0  187.58     .12       0  344.47      .1       0
   395.9    .045       0   424.1     .12       0  513.21      .1       0
Bank Sta=395.9,424.1
XS Rating Curve= 0 ,0
Exp/Cntr=0.3,0.1

Type RM Length L Ch R = 1 ,52948   ,447.1,449.9,454.1
XS GIS Cut Line= 3
     2375744.984      614232.506     2375326.322      614392.829
2374939.69901853   614546.754668
#Sta/Elev= 30
       0 3691.48    23.8 3680.03    88.1 3643.51     148 3612.66   169.4 3598.84
   203.7  3580.9   226.6 3565.93     239 3560.04   293.7 3526.87   319.5 3513.83
   349.3 3499.46   375.2 3489.98   396.9 3484.03   430.7 3477.94   439.3 3471.96
   447.9 3469.03   461.9 3471.87   473.7 3477.06   483.4 3478.75   503.8 3492.03
   518.8 3498.09   529.6    3505   566.6    3523   628.7  3549.2   652.8  3556.8
   702.6 3579.56   714.8 3582.38   727.7 3588.06   819.1 3633.25   864.4 3653.86
#Mann= 5 ,-1 , 0
       0      .1       0  179.52      .1       0   382.4      .1       0
   439.3    .045       0   461.9      .1       0
Bank Sta=439.3,461.9
XS Rating Curve= 0 ,0
Exp/Cntr=0.3,0.1

Type RM Length L Ch R = 1 ,52498   ,447.9,450,451.9
XS GIS Cut Line= 3
     2375754.006      613969.508     2375344.616      613960.047
     2374935.225      613950.585
#Sta/Elev= 30
       0 3680.39    31.3 3663.34    67.3 3645.72   139.3    3604   183.3 3583.81
   250.5 3548.34   271.3 3535.79   319.3 3511.74   339.4 3499.48   371.4 3483.47
   383.4 3472.97   391.4 3460.37   395.4 3458.21   399.4 3458.02   427.4 3460.17
   435.4 3461.16   443.7  3464.7   459.4 3464.78   499.4 3477.98   527.4 3493.19
   535.4 3495.83   547.4 3503.14   583.4 3520.44   647.4 3556.22   687.4 3580.06
   723.5 3598.53   764.4 3623.67   783.5  3632.9   791.5 3638.65     819 3653.71
#Mann= 5 ,-1 , 0
       0      .1       0  331.68      .1       0   391.4    .045       0
   427.4      .1       0   432.7      .1       0
Bank Sta=391.4,427.4
XS Rating Curve= 0 ,0
Exp/Cntr=0.3,0.1

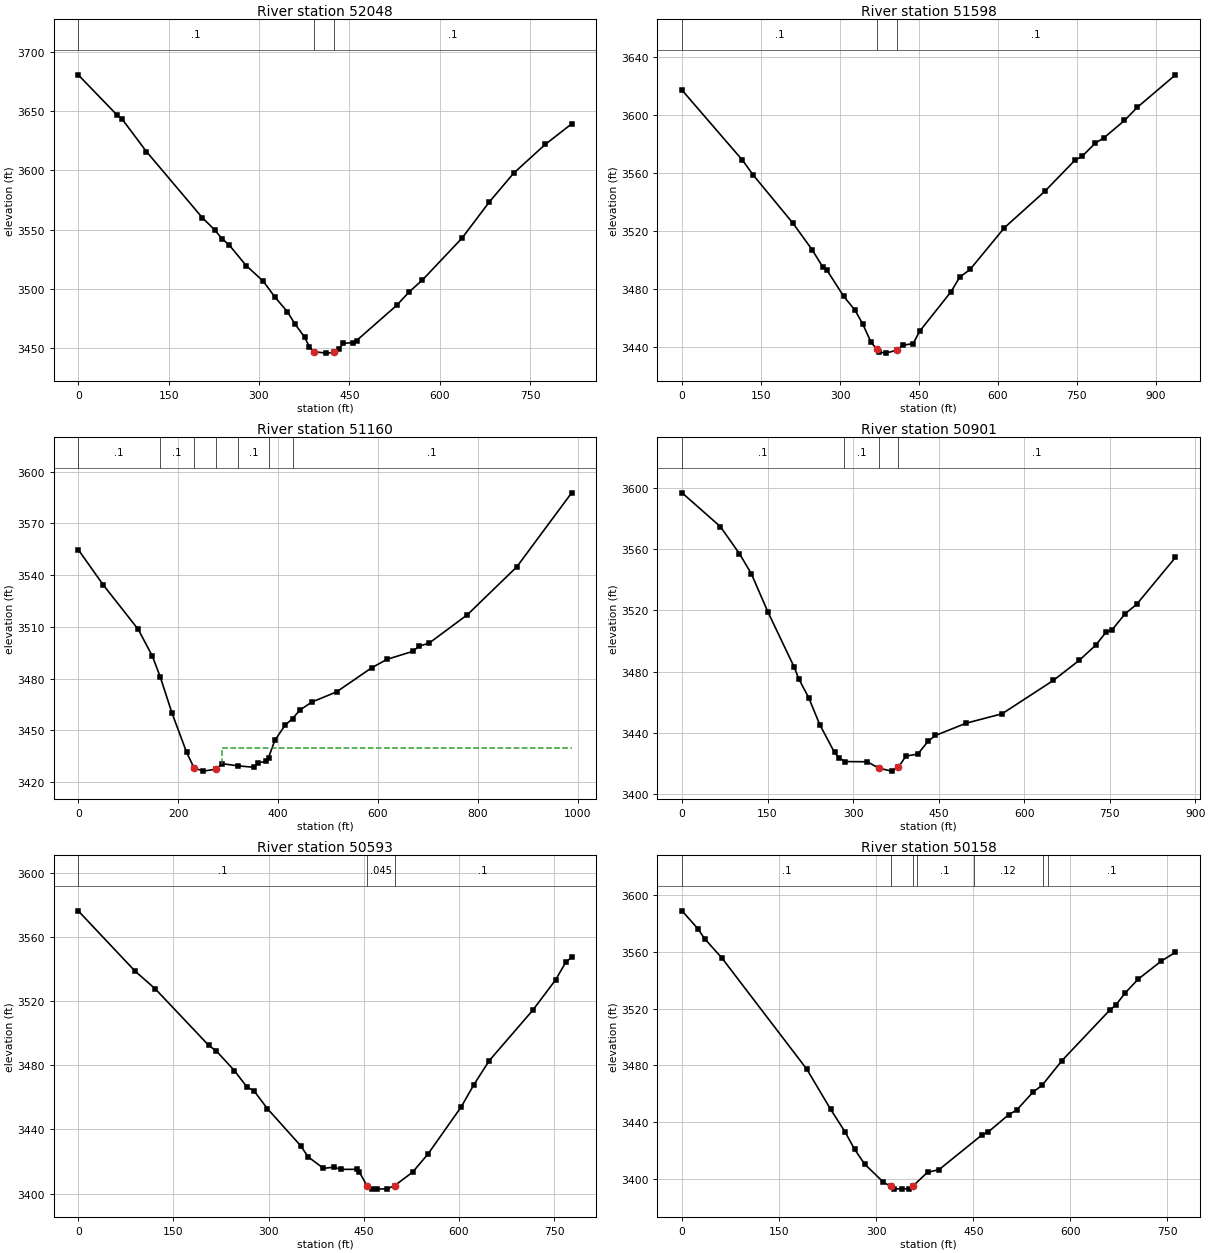
Type RM Length L Ch R = 1 ,52048   ,452.5,450.7,449.2
XS GIS Cut Line= 3
     2375815.098      613569.527     2375409.111         613516.
     2375003.124      613462.474
#Sta/Elev= 30
       0 3680.58    64.9 3646.41      73 3643.11   113.3 3615.75   205.8 3560.05
   226.3 3549.79   238.4 3542.37   250.5 3536.95   278.7 3519.59     307 3506.39
     327 3492.63   347.3 3480.52   359.4 3470.49   375.6 3459.23   383.6 3451.15
   391.2 3446.82   411.9 3445.63     424 3446.17   432.1  3449.1   440.1 3453.84
   456.3 3454.55   462.1 3456.27   528.9 3486.11   549.1 3497.22     571 3507.19
   637.2 3542.81   682.2 3573.16   722.7 3597.51     775 3621.77     819 3639.16
#Mann= 3 ,-1 , 0
       0      .1       0   391.2    .045       0     424      .1       0
Bank Sta=391.2,424
XS Rating Curve= 0 ,0
Exp/Cntr=0.3,0.1

Type RM Length L Ch R = 1 ,51598   ,473,437.8,418.4
XS GIS Cut Line= 3
     2375833.515      613080.8732375307.97131967613062.072842263
     2374997.626      613332.227
#Sta/Elev= 30
       0 3617.42   114.8 3569.05   134.9 3558.95   210.9 3525.43   246.9 3507.29
   266.9 3495.57   275.1 3493.15     307 3475.09   328.8 3465.33     343 3456.06
     359 3443.33   370.3 3438.39     375 3436.54     387 3435.81   407.6 3437.81
     419  3441.2   439.1 3442.43   451.1 3450.82   511.1 3478.29   527.3 3488.21
   547.2 3493.64   612.4 3522.45   688.9 3547.49   746.4 3569.09   759.8 3571.72
   785.3 3580.96   801.3 3584.48   840.4 3596.49   864.7 3605.57   937.3 3628.03
#Mann= 3 ,-1 , 0
       0      .1       0   370.3    .045       0   407.6      .1       0
Bank Sta=370.3,407.6
XS Rating Curve= 0 ,0
Exp/Cntr=0.3,0.1

Type RM Length L Ch R = 1 ,51160   ,280.5,258.6,252
XS GIS Cut Line= 3
2375447.47623849612412.6487749932375294.03626489612884.298467213
     2374958.099      613243.032
#Sta/Elev= 30
       0 3554.86      50 3534.41   120.1 3508.62   148.4 3493.11   164.2 3481.01
   187.4 3460.32   216.9 3437.33   231.9 3428.26   250.5 3426.43   275.8 3427.59
   288.4 3430.73   319.7  3429.5   351.5 3428.66   359.9 3431.25   376.7 3432.15
   380.9 3434.32   393.5 3444.24   413.8 3452.98     429 3456.93     444 3461.91
   467.8  3466.5   517.1 3472.37   587.2 3486.32   617.8 3491.21   669.4 3495.85
   682.2 3498.86   702.3 3500.63     779 3517.14   877.7 3544.84   987.5 3587.76
#Mann= 7 ,-1 , 0
       0      .1       0   164.2      .1       0   231.9    .045       0
   275.8      .1       0   319.7      .1       0   380.9      .1       0
     429      .1       0
#XS Ineff= 2 , 0
                          287.02          3439.7
Permanent Ineff=
       F       F
Bank Sta=231.9,275.8
XS Rating Curve= 0 ,0
Exp/Cntr=0.3,0.1

Type RM Length L Ch R = 1 ,50901   ,304.4,308.7,320.5
XS GIS Cut Line= 3
2375034.98096686612418.4770214432375157.58979532612832.447483431
2374907.07051072613186.528126705
#Sta/Elev= 30
       0 3596.79    67.2 3574.73   100.6  3557.1   121.4  3544.1   150.6 3519.01
   196.5 3483.17   204.8 3475.32   222.2 3463.02   241.5 3445.54   267.4  3427.3
   275.8 3423.52   286.6 3421.36   325.2 3421.24   344.7 3417.11   367.5 3415.13
   379.5 3417.71   392.8 3424.99   413.4 3426.21   431.7 3434.68   444.5 3438.41
   498.4 3446.43   561.3 3452.56   651.4 3474.38   696.7 3487.46   725.4 3497.29
   743.4  3505.7   754.1 3507.26     777  3517.8   797.3 3523.99   865.5 3554.66
#Mann= 4 ,-1 , 0
       0      .1       0  284.44      .1       0   344.7    .045       0
   379.5      .1       0
Bank Sta=344.7,379.5
XS Rating Curve= 0 ,0
Exp/Cntr=0.3,0.1

Type RM Length L Ch R = 1 ,50593   ,424.9,434.7,458.3
XS GIS Cut Line= 2
2374886.07191813612382.1879337242374812.85766862613156.144906433
#Sta/Elev= 30
       0 3576.23    89.1 3538.84   121.2 3527.67   205.6  3492.4   217.7 3488.85
     246 3476.69   265.9 3466.39   276.7 3464.16     298 3452.99   350.3 3429.92
   362.3 3422.88   386.4 3415.76   402.5 3416.45   414.5 3415.12   438.7 3415.14
   442.7 3413.59   455.2 3404.77   462.5 3402.87   470.8  3402.8   486.9 3403.03
   498.5 3404.94     527 3413.44   551.2 3424.75   603.4 3454.04   622.8 3467.52
   647.6 3482.88   715.9 3514.17     752 3533.14   768.1 3544.13   777.4 3547.33
#Mann= 3 ,-1 , 0
       0      .1       0   455.2    .045       0   498.5      .1       0
Bank Sta=455.2,498.5
XS Rating Curve= 0 ,0
Exp/Cntr=0.3,0.1

Type RM Length L Ch R = 1 ,50158   ,503.9,509.6,511.8
XS GIS Cut Line= 3
2374841.08177316612306.5129278952374580.24470105612530.338542316
      2374254.11      612792.909
#Sta/Elev= 30
       0 3588.81    24.2 3576.32    34.7 3569.26    61.5 3555.64   192.8 3477.26
   229.7 3448.93   251.6 3433.34   266.6 3420.88   282.4 3410.32   311.1 3397.74
   322.5 3394.72   328.1 3393.21   339.5 3392.84   350.9 3393.25   356.5 3394.91
   379.3 3404.73     397 3406.53   463.7 3431.14   473.2 3433.13   504.8 3445.32
   516.8  3448.4   542.3  3461.2   556.2 3465.89     587 3483.35   660.9 3518.92
   669.9 3522.32   684.6 3530.95   705.1 3540.83     740 3553.27   762.4 3559.65
#Mann= 7 ,-1 , 0
       0      .1       0   322.5    .045       0   356.5      .1       0
  362.55      .1       0  450.76     .12       0  557.61      .1       0
  565.01      .1       0
Bank Sta=322.5,356.5
XS Rating Curve= 0 ,0
Exp/Cntr=0.3,0.1

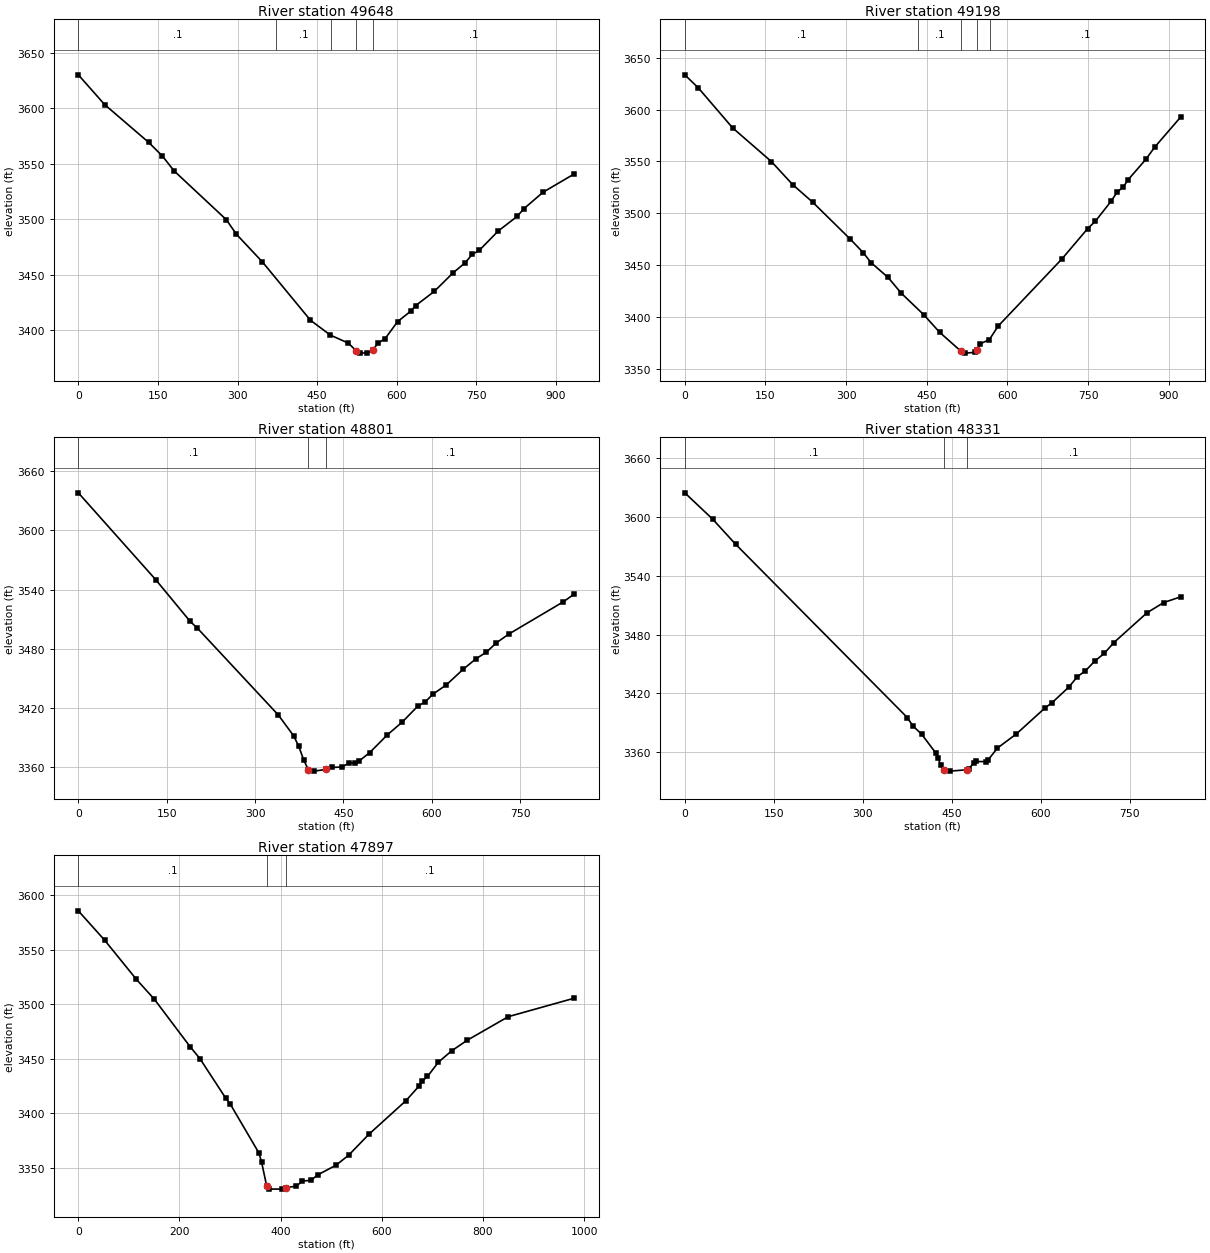
Type RM Length L Ch R = 1 ,49648   ,436.5,450.7,466.3
XS GIS Cut Line= 3
     2374672.298      612040.596     2374177.003      612254.159
2373821.85941557612426.301346322
#Sta/Elev= 30
       0 3630.22    49.6 3603.39   132.4 3569.39   158.2 3557.15   180.3  3543.7
   278.6 3499.78   297.9 3486.51   346.9 3461.55   437.3 3409.07   474.7 3395.71
   508.2 3388.57   523.4 3381.64   531.1 3379.69   544.6 3379.46   555.2 3382.25
   564.1 3388.43   577.7  3392.4   601.5 3407.88   626.3 3417.32   635.2  3422.2
   670.4 3435.04   706.3 3451.98   728.6 3460.84   741.9 3468.41   755.3 3472.07
   790.8 3489.42   826.4  3502.6   839.7 3509.72   875.3 3524.41     934 3540.88
#Mann= 5 ,-1 , 0
       0      .1       0  372.89      .1       0   475.3      .1       0
   523.4    .045       0   555.2      .1       0
Bank Sta=523.4,555.2
XS Rating Curve= 0 ,0
Exp/Cntr=0.3,0.1

Type RM Length L Ch R = 1 ,49198   ,401.4,396.2,395.5
XS GIS Cut Line= 3
 2374683.7420891611976.908356417 2374445.6612878611984.772132467
     2373868.184      611618.613
#Sta/Elev= 30
       0 3633.48      25 3620.95      89 3582.32   161.1 3549.86   200.5 3527.71
   238.2 3510.54     308 3474.97   331.7 3462.15   346.3 3452.49   377.9 3438.27
   402.7 3422.93   444.6 3402.14   473.7 3385.43   513.4 3367.16   521.1 3365.26
   540.1 3365.99   543.1  3367.9   549.5 3374.27   566.3 3378.26   582.7  3391.3
   701.1 3455.95   748.9 3485.12   763.4 3492.36   792.4 3511.43     804 3520.48
   815.6 3525.47   824.2 3532.28   857.4 3552.05   873.6 3563.67     922 3592.75
#Mann= 5 ,-1 , 0
       0      .1       0  434.55      .1       0   513.4    .045       0
   543.1      .1       0  567.34      .1       0
Bank Sta=513.4,543.1
XS Rating Curve= 0 ,0
Exp/Cntr=0.3,0.1

Type RM Length L Ch R = 1 ,48801   ,477.9,469.8,465.7
XS GIS Cut Line= 2
2374818.59783158611665.289335791     2374035.812      611356.233
#Sta/Elev= 30
       0 3638.17   131.2  3550.1   189.8 3507.67     202 3500.84   339.6 3412.55
   365.6 3391.37     374 3381.06   382.6 3366.95   390.2 3357.26   399.8 3355.68
     421 3357.41   429.9 3359.37   447.1 3359.88     460 3363.93   470.4 3364.02
   477.2 3366.25   494.4 3374.39   524.5  3392.5   549.8 3405.47   576.1 3421.59
     589 3426.09   601.9 3433.84   624.5 3443.18   653.5 3459.19     675 3469.78
   692.4 3476.28   709.4 3485.82   730.9 3494.89   823.5 3527.65   841.6 3535.38
#Mann= 3 ,-1 , 0
       0      .1       0   390.2    .045       0     421      .1       0
Bank Sta=390.2,421
XS Rating Curve= 0 ,0
Exp/Cntr=0.3,0.1

Type RM Length L Ch R = 1 ,48331   ,453.3,434.6,429.6
XS GIS Cut Line= 2
   2374909.64948611037.5850263152374074.22393894611060.970246316
#Sta/Elev= 30
       0 3624.54    46.9 3597.75    85.8 3572.04   375.1 3395.43   384.5 3386.92
   399.1  3378.6   423.1 3359.33   427.1 3354.67   431.1 3346.86   436.2 3342.33
   447.1 3340.86   475.5 3342.25   479.1 3343.28   487.1 3349.44   491.1 3350.68
   507.1 3350.53   511.1 3352.16   527.1 3364.41   559.1 3378.85   607.1 3405.21
   619.2  3410.7   647.2 3426.42   661.9 3437.24   675.2 3443.01   691.2 3453.11
   707.2 3460.93   723.2 3471.85   779.2  3502.3   807.2 3512.66   835.8 3518.52
#Mann= 3 ,-1 , 0
       0      .1       0   436.2    .045       0   475.5      .1       0
Bank Sta=436.2,475.5
XS Rating Curve= 0 ,0
Exp/Cntr=0.3,0.1

Type RM Length L Ch R = 1 ,47897   ,306.1,290.1,285
XS GIS Cut Line= 3
2374745.66647719610376.7860807022374264.46210526610748.398982458
2374019.68677895 611029.14191228
#Sta/Elev= 30
       0 3585.65    52.1 3558.65   114.7 3522.82   150.3 3504.52     221 3460.97
   240.3  3450.1   291.6 3413.61   300.2 3408.47   357.2 3363.32   362.5 3354.81
   372.6 3332.73   377.2 3330.32     403 3330.22   411.33331.709   431.3 3332.94
   442.7 3337.59   459.9  3338.3   473.7 3343.38   509.1 3352.04   534.4 3361.28
   574.8 3380.65   647.8 3411.38   673.3 3424.57   680.3 3429.53   690.4 3433.62
   712.1 3446.75   738.4  3457.2   768.9 3466.83   850.1 3488.49   980.5 3505.44
#Mann= 3 ,-1 , 0
       0      .1       0   372.6    .045       0   411.3      .1       0
Bank Sta=372.6,411.3
XS Rating Curve= 0 ,0
Exp/Cntr=0.3,0.1