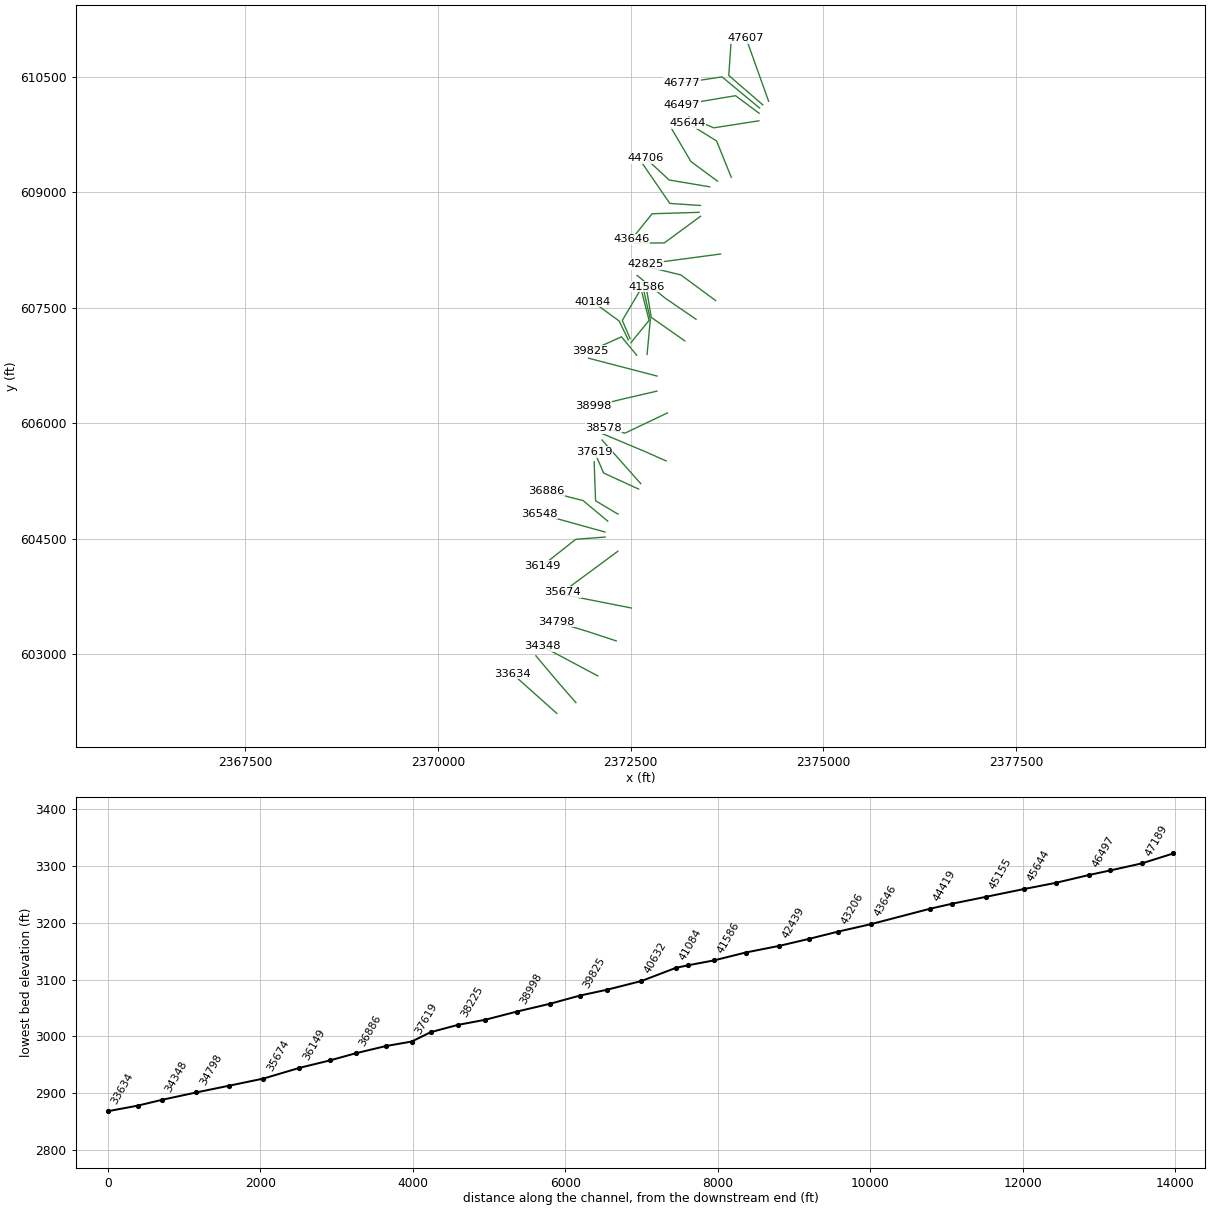
HEC-RAS study BIGRN.prj: BIGRN

--- BIGRN.g01 (geometry) --- (continued)

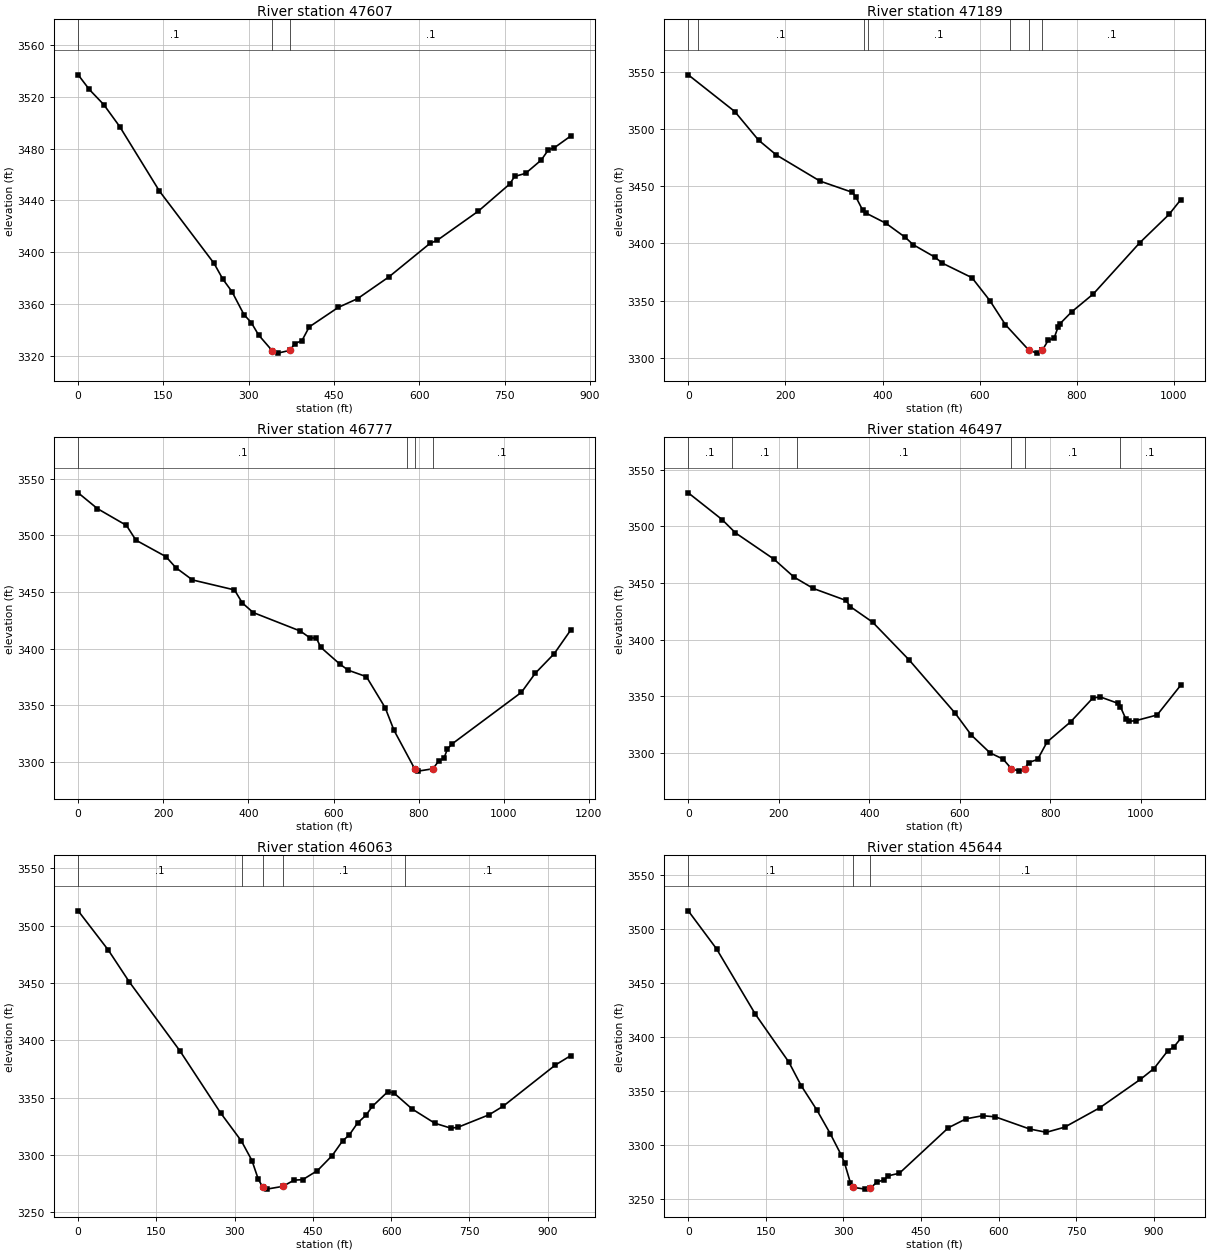
Type RM Length L Ch R = 1 ,47607   ,426.8,418,413.1
XS GIS Cut Line= 2
2374289.61470642610180.4020316582373997.91701404610995.671059649
#Sta/Elev= 30
       0 3536.98    19.6 3525.65    45.1  3513.9      73    3497   142.8 3447.16
   238.9 3391.23   254.5 3378.93   270.3 3369.44   291.5 3351.63   304.3 3345.49
   317.2 3335.89     341 3323.78     351 3321.86   372.2    3324   380.7 3329.09
   393.5 3331.57   406.2 3342.11   457.2 3357.19   491.2 3363.96   546.4 3380.82
   618.7 3406.74   631.4 3409.11   703.6 3431.64   758.8 3452.62   767.3 3458.44
   786.6 3460.81   814.1  3471.1   826.8 3479.08   836.5 3480.42   865.9 3489.68
#Mann= 3 ,-1 , 0
       0      .1       0     341    .045       0   372.2      .1       0
Bank Sta=341,372.2
XS Rating Curve= 0 ,0
Exp/Cntr=0.3,0.1

Type RM Length L Ch R = 1 ,47189   ,381,411.9,447.1
XS GIS Cut Line= 3
     2374214.681      610132.2792373772.63433684610514.201642104
2373802.62425614610943.168824561
#Sta/Elev= 30
       0 3547.16    95.8 3515.11   144.7 3490.16   181.4  3477.2   271.2 3454.41
   338.2 3444.55     345 3440.65   358.9 3429.24     365 3426.67     407 3417.58
   447.1 3405.21   462.9 3398.93   507.4 3388.13   523.2 3382.75   584.2 3370.05
     621 3350.08     653 3329.07   700.83307.025   717.2  3304.2   729.2 3306.73
   729.2 3306.75   741.3 3315.49   753.3 3317.27   761.3 3326.72   765.3 3329.79
   789.2 3340.11   834.2 3355.92   929.7 3400.57   989.9 3425.24  1014.2 3438.18
#Mann= 7 ,-1 , 0
       0      .1       0   19.65      .1       0  362.38      .1       0
  369.54      .1       0  662.02      .1       0   700.8    .045       0
   729.2      .1       0
Bank Sta=700.8,729.2
XS Rating Curve= 0 ,0
Exp/Cntr=0.3,0.1

Type RM Length L Ch R = 1 ,46777   ,280.2,279.3,278
XS GIS Cut Line= 3
     2374173.523      610090.5292373684.98837193610495.573617544
     2373168.334      610416.159
#Sta/Elev= 30
       0 3537.51    45.2 3523.58   113.4 3508.77   135.7 3495.74   206.3 3481.18
   229.5 3471.46   268.6 3460.62   367.3 3451.82   385.7 3440.31   411.3 3431.85
   522.1  3415.5   544.8 3409.45   559.6 3409.33     570 3401.18   614.7 3386.39
   634.6 3380.96   677.3 3375.23   721.4 3347.84   742.1 3327.92   791.5 3293.39
   798.8 3291.89   833.6 3293.97   847.3 3300.91   859.5 3303.29   867.6 3311.35
   879.2 3316.08  1041.6 3361.46    1074 3378.25  1118.5 3395.52  1157.3 3416.38
#Mann= 4 ,-1 , 0
       0      .1       0  772.26      .1       0   791.5    .045       0
   833.6      .1       0
Bank Sta=791.5,833.6
XS Rating Curve= 0 ,0
Exp/Cntr=0.3,0.1

Type RM Length L Ch R = 1 ,46497   ,438.9,434.9,433.2
XS GIS Cut Line= 3
     2374166.613      610023.9272373860.32458246610251.220712281
     2373162.928      610134.405
#Sta/Elev= 30
       0 3529.45    74.6  3505.9   104.4 3494.09   189.1 3470.99   233.9 3455.03
   276.5 3445.02   348.5  3434.5   358.5  3428.9   407.4 3415.31   488.5  3381.8
   589.9 3334.94   625.5 3315.69   666.9 3299.94   695.7 3294.47   714.2 3285.96
   731.8 3283.83     744 3285.97   752.1 3291.36   772.1 3294.16     793 3309.54
   845.4 3327.47     894  3348.3   910.3 3349.36   949.3 3343.73   954.9 3340.78
     967 3329.97   975.1 3327.86   988.7 3328.32  1036.2 3333.39  1088.5 3359.72
#Mann= 6 ,-1 , 0
       0      .1       0   96.78      .1       0  239.24      .1       0
   714.2    .045       0     744      .1       0  953.45      .1       0
Bank Sta=714.2,744
XS Rating Curve= 0 ,0
Exp/Cntr=0.3,0.1

Type RM Length L Ch R = 1 ,46063   ,445.1,418.1,398.4
XS GIS Cut Line= 3
     2374164.034      609925.2892373577.39816433  609834.2390006
2373255.86004998609974.202001199
#Sta/Elev= 30
       0 3513.01      58  3478.6    97.8 3451.11   195.6 3390.42     273 3336.65
     313 3312.02   333.2 3295.03   345.4  3278.6   353.6 3272.09   361.6 3270.07
   392.2 3272.47   414.2 3277.95   430.4  3278.3   458.8 3286.25   487.1 3299.41
   507.3 3312.41   519.4 3317.09   535.6 3327.75   551.8  3334.6   563.9 3342.27
   593.7 3355.13   605.3 3354.03   640.2 3340.05   683.8 3327.58   714.3 3323.34
   727.4 3323.95   787.7 3334.96   814.7 3342.41     915 3378.44   944.3 3386.58
#Mann= 5 ,-1 , 0
       0      .1       0  313.22      .1       0   353.6    .045       0
   392.2      .1       0  625.95      .1       0
Bank Sta=353.6,392.2
XS Rating Curve= 0 ,0
Exp/Cntr=0.3,0.1

Type RM Length L Ch R = 1 ,45644   ,491.5,489.4,495.5
XS GIS Cut Line= 3
 2373805.2329958609192.1798404642373615.22389524609663.910363655
2373237.42257557609896.793316673
#Sta/Elev= 30
       0 3516.81    54.7  3481.6     130 3420.91   194.6 3376.68   218.5 3354.83
   248.7 3332.37   274.6 3310.48   296.2 3290.33   302.2 3283.41   313.4 3265.24
   317.7 3260.88   342.1 3259.14   352.2 3260.05   365.2 3265.78   378.1 3267.57
   386.7 3271.47   408.3 3273.88   503.1 3316.01   537.2 3324.23   569.2 3327.12
   593.7 3326.06   660.1 3314.82   692.4 3311.76   727.7 3316.48   795.8 3334.47
   874.4  3360.8   900.6  3370.8   927.3 3387.23   938.4 3390.46   952.4  3398.7
#Mann= 3 ,-1 , 0
       0      .1       0   317.7    .045       0   352.2      .1       0
Bank Sta=317.7,352.2
XS Rating Curve= 0 ,0
Exp/Cntr=0.3,0.1

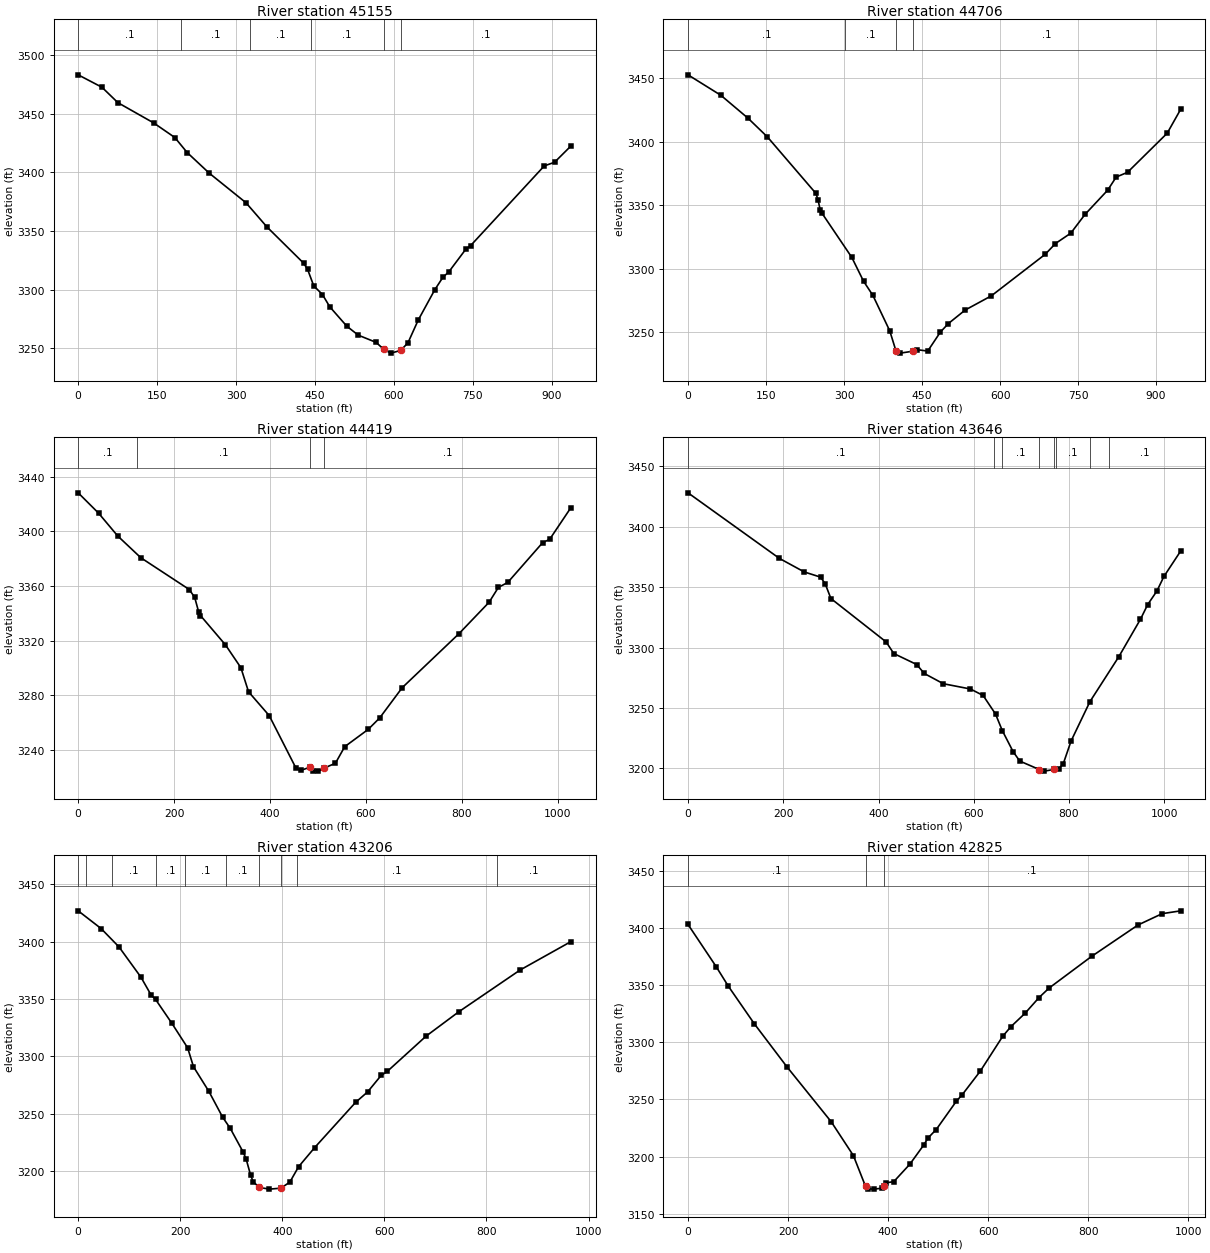
Type RM Length L Ch R = 1 ,45155   ,435.2,448.7,460.5
XS GIS Cut Line= 3
2373627.11934853 609141.62785779 2373281.3735939609397.399003998
2373024.18775463609833.828632947
#Sta/Elev= 30
       0 3483.43    45.2 3472.81    75.5 3459.64   143.4 3442.37   183.7 3429.88
   207.1 3417.07   249.2 3399.39   318.9 3374.17   358.7 3353.53   428.4 3322.58
     436  3317.3   447.7 3303.18   464.3 3295.74   478.2 3285.25   510.7 3268.64
   532.4 3261.02   566.4 3254.85   580.4 3249.04   594.3 3245.68   612.9 3247.96
   626.8 3254.48   646.3 3273.91   677.9  3299.9   693.1 3310.37   704.8  3315.3
   736.9 3334.55   745.7 3337.43   885.9 3405.63   905.4 3408.72   936.6 3422.65
#Mann= 6 ,-1 , 0
       0      .1       0  195.56      .1       0  326.92      .1       0
  442.03      .1       0   580.4    .045       0   612.9      .1       0
Bank Sta=580.4,612.9
XS Rating Curve= 0 ,0
Exp/Cntr=0.3,0.1

Type RM Length L Ch R = 1 ,44706   ,294.8,287.5,269.5
XS GIS Cut Line= 3
2373525.31409053609068.6763757912372999.64345579609157.023817895
     2372695.577      609438.539
#Sta/Elev= 30
       0 3452.51    63.2 3436.39   115.3 3418.39   152.7  3403.6     246 3359.12
     250 3353.99   254.1 3346.26   257.6 3343.55   314.9  3308.8   337.5 3290.03
   355.5 3278.84   387.9 3250.95   400.1  3234.8   408.2 3233.43   432.6 3234.95
   440.7 3236.13   460.9 3235.05   485.3 3250.05   500.7 3256.75     533 3267.38
   583.3 3278.55   686.9 3311.27   706.5 3319.72     736 3327.88   763.2 3342.59
   806.8 3361.68   823.2 3372.03     845 3375.75   921.3 3406.56   947.4 3425.51
#Mann= 4 ,-1 , 0
       0      .1       0  301.06      .1       0   400.1    .045       0
   432.6      .1       0
Bank Sta=400.1,432.6
XS Rating Curve= 0 ,0
Exp/Cntr=0.3,0.1

Type RM Length L Ch R = 1 ,44419   ,739.3,772.6,792.6
XS GIS Cut Line= 3
     2373405.063      608826.4322373007.75440825608853.218592477
     2372651.513      609371.517
#Sta/Elev= 30
       0 3428.18    42.4 3413.36    82.5  3396.6   130.6 3380.72   231.7 3357.45
   242.9 3351.65   250.9  3341.4   254.9 3338.46     307    3317   339.1 3300.34
   355.1  3282.7   398.2 3265.28   453.6 3227.12   463.4 3225.16   482.8  3227.5
   489.3 3225.13   500.8 3224.69     513 3226.99   536.1 3230.42   555.6 3242.57
   604.4 3255.18   628.4 3263.56   675.4 3285.71   793.4 3325.08   856.5 3348.18
   875.9 3359.06   895.3 3362.62   968.1 3391.74   982.7 3394.15  1027.1 3417.39
#Mann= 4 ,-1 , 0
       0      .1       0  122.35      .1       0   482.8    .045       0
     513      .1       0
Bank Sta=482.8,513
XS Rating Curve= 0 ,0
Exp/Cntr=0.3,0.1

Type RM Length L Ch R = 1 ,43646   ,450.2,440.7,435.4
XS GIS Cut Line= 3
      2373386.59      608737.5822372777.93614907608719.185719316
2372511.31459955 608387.41825069
#Sta/Elev= 30
       0 3428.19   191.9 3373.87     244 3362.66   278.3 3358.35     288 3352.88
     300 3340.63     416 3304.67     432 3295.08   480.1 3285.97   496.1 3278.53
   536.1 3270.05   592.9 3265.69   619.6 3260.34   645.6 3244.98   659.8  3231.3
   682.5 3213.84   696.5    3206   737.6 3198.97     748 3197.65   768.4 3199.03
   778.7 3199.78   787.8 3203.67   804.3 3222.64   843.9 3255.22   904.5 3292.42
     950  3323.5   965.2 3335.65   984.4 3346.81   999.3 3358.96  1034.6 3380.09
#Mann= 8 ,-1 , 0
       0      .1       0  642.43      .1       0   659.8      .1       0
   737.6    .045       0   768.4      .1       0  772.36      .1       0
  843.67      .1       0  884.92      .1       0
Bank Sta=737.6,768.4
XS Rating Curve= 0 ,0
Exp/Cntr=0.3,0.1

Type RM Length L Ch R = 1 ,43206   ,389.6,380.8,371.6
XS GIS Cut Line= 3
2373406.96989524608686.4667886842372935.87288429608340.527627742
2372554.87337597 608338.46066198
#Sta/Elev= 30
       0 3426.75    44.9  3411.3      80 3395.27   122.9 3368.97   142.9 3353.36
   151.5 3349.61     183  3329.1   214.5 3307.32   225.9 3290.86   256.1 3269.36
   283.1 3246.83     298 3237.13   322.9 3216.75   328.9  3210.7   337.7 3196.63
   342.7 3190.78   354.7 3185.66   374.7 3184.18   397.3 3185.01   414.8 3190.35
     432  3203.8   463.4  3220.4   543.5 3259.77     567 3268.87   593.6 3283.27
   605.6 3286.78   681.6 3317.51   745.6 3338.71   865.7 3375.11   965.5 3399.93
#Mann= 10 ,-1 , 0
       0      .1       0   15.29      .1       0   66.76      .1       0
  152.91      .1       0  208.46      .1       0  290.53      .1       0
   354.7    .045       0   397.3      .1       0  428.16      .1       0
  820.78      .1       0
Bank Sta=354.7,397.3
XS Rating Curve= 0 ,0
Exp/Cntr=0.3,0.1

Type RM Length L Ch R = 1 ,42825   ,400.5,386.2,379.4
XS GIS Cut Line= 2
2373666.50891973608196.6370067422372689.81128059608066.431746606
#Sta/Elev= 30
       0 3403.36    56.3 3366.41    80.5 3349.34   132.9 3316.14   197.5 3278.78
   286.4 3230.44   330.7 3200.81   354.9 3173.93   358.9 3171.71     371 3171.44
   387.2 3172.19   391.2 3173.92   395.2 3176.93   411.4 3177.99   443.7 3193.34
   471.4 3210.14     480 3216.31   496.3 3223.66   536.5 3248.43   548.6 3254.35
   584.4 3274.81   629.3 3305.39   645.4 3313.69   673.7 3325.43   701.9 3339.32
   722.1 3347.68   806.8 3375.32   899.7 3402.88   948.1 3412.83   985.3 3415.31
#Mann= 3 ,-1 , 0
       0      .1       0   354.9    .045       0   391.2      .1       0
Bank Sta=354.9,391.2
XS Rating Curve= 0 ,0
Exp/Cntr=0.3,0.1

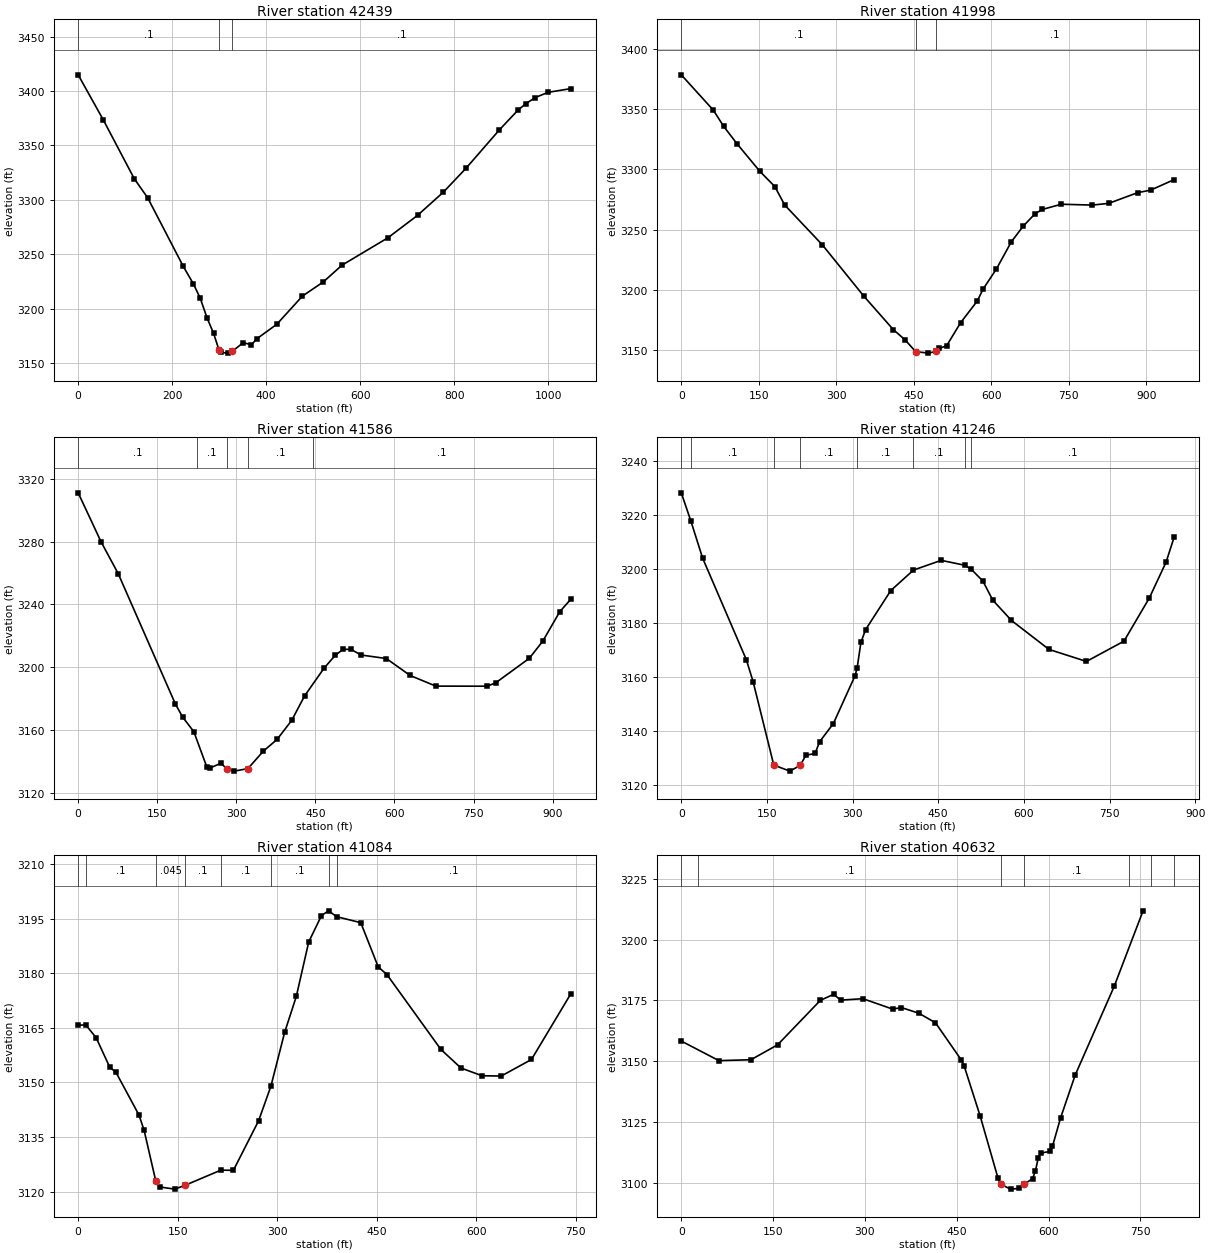
Type RM Length L Ch R = 1 ,42439   ,433,440.5,442.2
XS GIS Cut Line= 3
     2373602.858      607592.0792373150.83530273607925.217036081
2372677.48774567608040.349576708
#Sta/Elev= 30
       0 3414.83    53.6 3373.34   119.4 3319.41     148 3301.86   223.7  3238.9
   245.2 3222.87   259.6 3209.86   274.4 3191.47   288.2 3177.41   299.6 3162.29
   303.2 3159.98   318.2 3159.28   328.2 3160.94   351.1 3168.89   368.8 3166.95
   379.7  3172.3   422.8 3185.81   477.2 3211.64   521.9 3224.73   561.5 3240.05
     659 3265.13   722.2 3285.78     777 3307.03   825.1 3328.89   896.6 3364.37
   936.2 3382.49   952.7 3388.32   972.8 3393.98    1000 3398.75  1048.7 3402.18
#Mann= 3 ,-1 , 0
       0      .1       0   299.6    .045       0   328.2      .1       0
Bank Sta=299.6,328.2
XS Rating Curve= 0 ,0
Exp/Cntr=0.3,0.1

Type RM Length L Ch R = 1 ,41998   ,409.7,412.1,414.1
XS GIS Cut Line= 3
2373348.22369786607350.097516569     2372953.378      607619.486
2372583.34655946607918.229649121
#Sta/Elev= 30
       0 3378.47    62.1 3349.13    82.2 3335.62   108.1 3321.16   151.9 3298.49
     181 3285.78   200.2 3270.44     273 3237.42   353.1 3194.94   410.4 3167.06
   432.8 3158.72   453.5 3148.86     478 3147.58   493.7 3149.07   499.3 3151.45
   513.6 3153.78   540.7  3172.9   572.6 3190.69   584.2 3200.81   609.9 3217.41
   638.7 3239.91   661.5 3252.81   684.2 3263.03   698.5 3266.75   735.4 3271.11
   795.4  3270.4   827.3 3271.84   883.3 3280.74   908.1 3282.76   953.6  3291.5
#Mann= 3 , 0 , 0
       0      .1       0   453.5    .045       0   493.7      .1       0
Bank Sta=453.5,493.7
XS Rating Curve= 0 ,0
Exp/Cntr=0.3,0.1

Type RM Length L Ch R = 1 ,41586   ,365.9,340.2,322.6
XS GIS Cut Line= 3
2373202.36179263607068.9309873682372766.70421478607374.516214668
2372700.57596169607771.742645853
#Sta/Elev= 30
       0 3311.16    43.5 3279.88    75.8 3259.75   184.5 3176.53   198.4 3168.15
   219.4 3158.95   243.8 3136.68     251 3135.94   271.1 3138.89     282  3135.1
     296 3133.82     322 3135.42   351.3 3146.58   377.3    3154   405.1 3166.18
   429.5 3181.74   466.3 3199.37   488.1 3207.77   502.8 3211.42   517.4 3211.45
   536.6 3207.82   584.6 3205.57   629.8 3194.76   678.5 3187.99   775.9 3187.94
     792 3190.08   855.7 3205.68   881.3 3216.59   913.7 3235.46   934.8 3243.43
#Mann= 5 ,-1 , 0
       0      .1       0   225.6      .1       0     282    .045       0
     322      .1       0   446.3      .1       0
Bank Sta=282,322
XS Rating Curve= 0 ,0
Exp/Cntr=0.3,0.1

Type RM Length L Ch R = 1 ,41246   ,177.1,161.3,150.1
XS GIS Cut Line= 3
2372712.64083038606893.6057552472372754.95315319607346.952071044
2372664.28389003607744.385674558
#Sta/Elev= 30
       0 3228.33    16.8 3217.88    37.4 3204.12   113.8 3166.54   125.8 3158.34
     162 3127.42   190.1 3125.17   208.43127.315   218.2 3131.05   234.3 3131.71
   242.3 3136.06   266.4 3142.82   304.4 3160.56   308.1 3163.53   314.6 3172.87
   322.8 3177.62     367 3192.12   406.7  3199.7   455.3  3203.3   496.3 3201.49
   508.1 3199.94   528.2 3195.63   545.5 3188.56   578.3 3181.01     644 3170.28
   709.6 3165.83   775.3 3173.34   819.6  3189.3   849.1 3202.66     863 3211.78
#Mann= 8 ,-1 , 0
       0      .1       0    16.8      .1       0     162    .045       0
   208.4      .1       0   308.1      .1       0   406.7      .1       0
   496.3      .1       0   508.1      .1       0
Bank Sta=162,208.4
XS Rating Curve= 0 ,0
Exp/Cntr(USF)=0,0
Exp/Cntr=0.3,0.1

Type RM Length L Ch R = 1 ,41084   ,454.7,452.4,453.8
XS GIS Cut Line= 3
2372502.74507095 607046.019003082372738.91816937 607334.96821288
2372646.55997446607692.526367474
#Sta/Elev= 30
       0 3165.71    11.5 3165.75      27 3162.28    47.6 3154.14    56.9 3152.76
    91.6 3141.02    99.3 3136.85   117.1 3122.76   122.9 3121.25   145.6 3120.66
   161.7 3121.76   214.9 3125.87   233.9 3125.83   271.8 3139.41   290.4 3148.93
   311.1 3163.72   328.7 3173.61   347.4 3188.57   366.6  3195.8   377.2 3197.11
   389.6 3195.49   425.8 3193.86   452.1 3181.71   465.2 3179.61   546.6 3159.02
   576.8 3153.93   608.6  3151.8   637.5 3151.73     683 3156.27   742.5 3174.37
#Mann= 8 ,-1 , 0
       0      .1       0    11.5      .1       0   117.1    .045       0
   161.7      .1       0   214.9      .1       0   290.4      .1       0
   377.2      .1       0   389.6      .1       0
Bank Sta=117.1,161.7
XS Rating Curve= 0 ,0
Exp/Cntr(USF)=0,0
Exp/Cntr=0.3,0.1

Type RM Length L Ch R = 1 ,40632   ,415.6,447.6,471
XS GIS Cut Line= 3
2372492.72239031607098.3779308132372390.76494617607334.862835955
2372644.09864211607762.128392986
#Sta/Elev= 30
       0 3158.31    61.5 3150.27   113.8 3150.64   157.4 3156.78   227.1 3175.02
   248.8 3177.51   260.5 3175.13   296.7 3175.72   345.1 3171.46   359.7 3172.06
   387.8 3169.78   415.2 3165.84   457.5 3150.51   462.2 3147.97   488.2 3127.53
   517.4 3101.96   522.6 3099.39   537.8 3097.48   552.4 3097.77   559.8 3099.42
   573.8  3101.8   578.4 3104.88   583.1  3110.3   586.9 3112.27   601.7 3112.96
   606.3 3115.03   619.5 3126.69   643.5 3144.38   707.1 3180.76   754.3 3211.82
#Mann= 7 ,-1 , 0
       0      .1       0   27.94      .1       0   522.6    .045       0
   559.8      .1       0  732.03      .1       0   767.7    .045       0
   804.9      .1       0
Bank Sta=522.6,559.8
XS Rating Curve= 0 ,0
Exp/Cntr=0.3,0.1

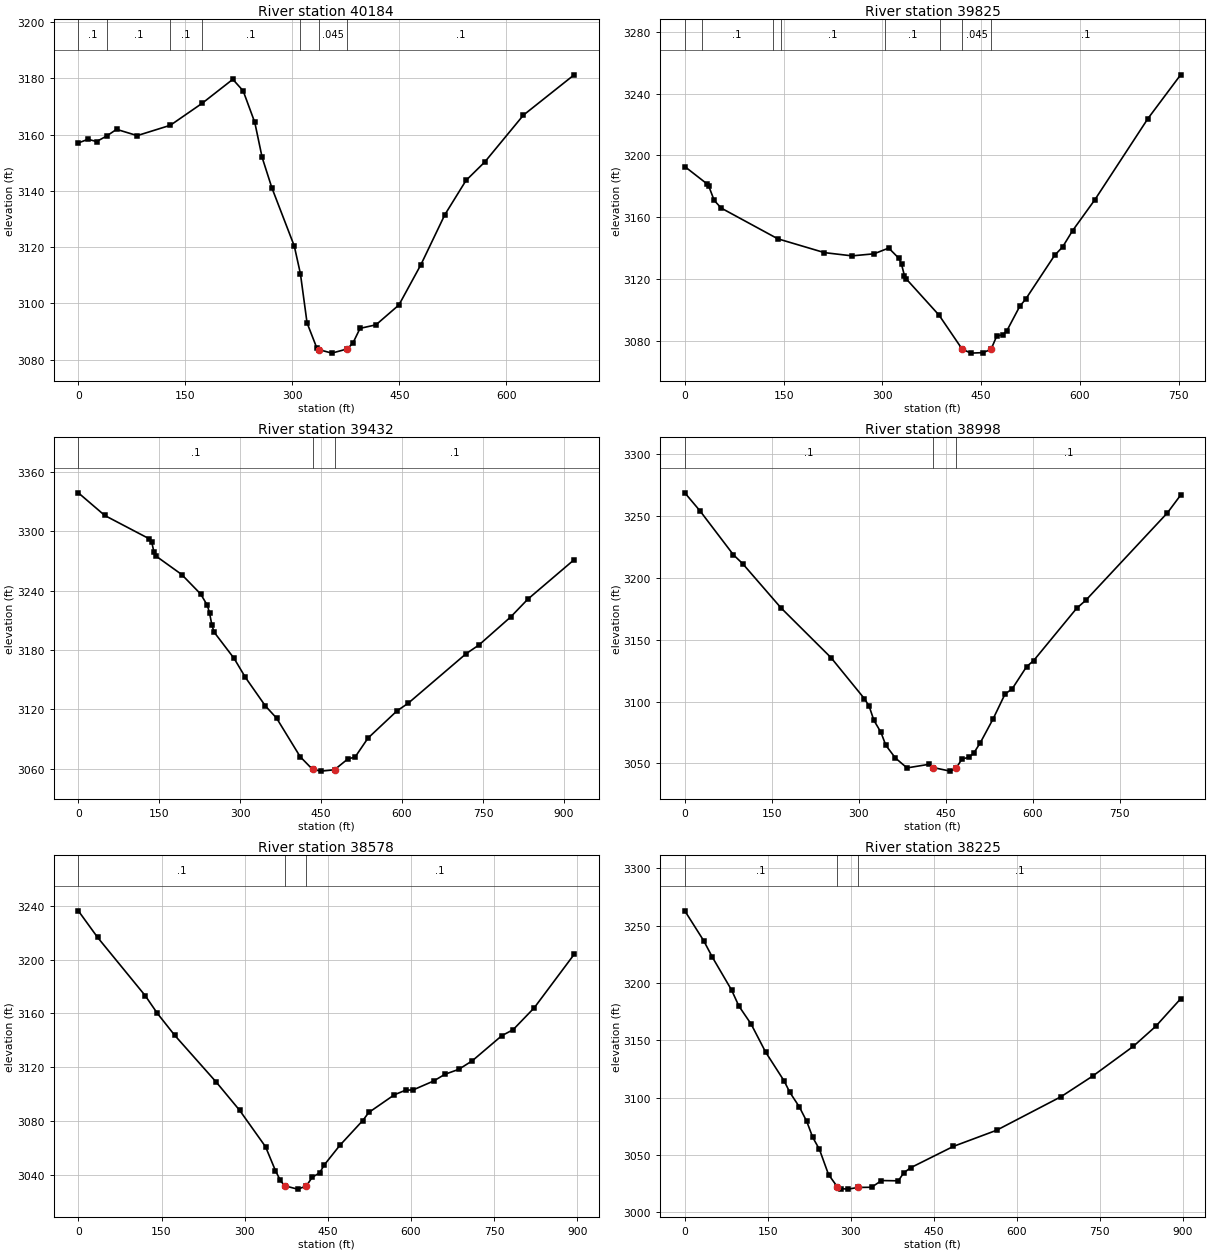
Type RM Length L Ch R = 1 ,40184   ,331.1,359.2,375.1
XS GIS Cut Line= 3
2372468.62083546607082.6140444082372351.47594737607326.186207017
     2372008.311      607576.805
#Sta/Elev= 30
       0 3157.03    13.6 3158.33    25.6 3157.52    40.3 3159.58    53.6 3161.87
    82.5 3159.63     129 3163.31   173.4 3171.09   216.6 3179.65   231.1 3175.55
   247.4 3164.33   257.7 3151.89   271.3 3141.11   302.8 3120.35   311.4  3110.5
   320.7 3093.02   334.3 3084.16   337.2 3083.54   355.4 3082.28   377.2 3083.78
   385.1 3085.92     395 3091.09   417.3 3092.34   449.5 3099.41   480.3 3113.72
   513.9 3131.51   543.6  3143.7   569.9 3150.26   624.1 3166.93   695.2 3181.25
#Mann= 7 ,-1 , 0
       0      .1       0    40.3      .1       0     129      .1       0
   173.4      .1       0   311.4      .1       0   337.2    .045       0
   377.2      .1       0
Bank Sta=337.2,377.2
XS Rating Curve= 0 ,0
Exp/Cntr=0.3,0.1

Type RM Length L Ch R = 1 ,39825   ,409.1,393.6,382.2
XS GIS Cut Line= 3
2372577.95280241606883.3234897172372380.52082807607121.746536842
2371975.87001404606941.071161404
#Sta/Elev= 30
       0 3192.77    33.2 3181.73    36.4 3180.06    44.6 3170.87    55.2 3165.89
   141.2 3145.96     212    3137   253.9 3134.91   287.3 3136.24   309.6 3139.97
   325.2 3133.22     329 3129.51   333.4 3122.07   336.2 3119.96     386 3096.47
     421 3074.51   434.2 3071.88   452.4  3072.2   464.8 3074.26   473.5 3082.88
   482.7 3083.89   488.7  3086.2   508.6 3102.31   517.4 3106.81   561.4 3135.24
   573.5 3140.65   588.6 3151.19   622.5 3171.27   703.1  3223.9   752.7 3252.22
#Mann= 8 ,-1 , 0
       0      .1       0   25.46      .1       0  133.75      .1       0
  146.17      .1       0  303.75      .1       0  387.58      .1       0
     421    .045       0   464.8      .1       0
Bank Sta=421,464.8
XS Rating Curve= 0 ,0
Exp/Cntr=0.3,0.1

Type RM Length L Ch R = 1 ,39432   ,420.6,433.4,440.6
XS GIS Cut Line= 2
 2372842.1991614606612.6150140362371953.00245614606844.595961405
#Sta/Elev= 30
       0 3338.79      49 3315.89   131.7 3292.25   135.9 3289.44     140 3279.22
   144.1 3274.78   191.6 3256.19   226.8 3236.44   239.2 3224.94   243.3 3217.01
   247.7 3204.73   251.6 3197.97   288.8 3171.31   309.6 3152.22   346.7 3123.32
   367.4 3111.02   411.2 3071.98   434.2 3059.12   450.6 3057.41   474.8 3058.79
   499.6 3069.76   512.9 3071.58   536.8 3090.75   590.6 3118.32   611.3    3126
   718.7 3176.12   742.4 3184.89   801.4  3213.3     833 3231.21     919 3271.18
#Mann= 3 ,-1 , 0
       0      .1       0   434.2    .045       0   474.8      .1       0
Bank Sta=434.2,474.8
XS Rating Curve= 0 ,0
Exp/Cntr=0.3,0.1

Type RM Length L Ch R = 1 ,38998   ,414,420.6,422.9
XS GIS Cut Line= 3
2372840.30669825 606417.07991228     2372400.654       606315.17
     2372008.572      606219.286
#Sta/Elev= 30
       0  3268.9    26.2  3254.3    83.7 3218.82    99.8 3211.55   165.8 3175.82
   252.1 3135.53   309.6 3102.38   317.8  3096.3     326 3084.84   338.3 3074.99
   346.5 3064.69   363.1 3054.33   383.1  3046.3   420.4 3049.17   428.6 3046.57
   457.4  3043.7   468.2 3046.43     478 3053.51   490.3 3054.98   498.6 3058.57
   509.4 3066.58   531.5  3085.9   552.1 3106.03   564.5  3110.3   589.2 3128.16
   601.5 3133.16   675.6 3175.44   691.3  3181.9   832.1 3252.68   854.9 3267.04
#Mann= 3 , 0 , 0
       0      .1       0   428.6    .045       0   468.2      .1       0
Bank Sta=428.6,468.2
XS Rating Curve= 0 ,0
Exp/Cntr=0.3,0.1

Type RM Length L Ch R = 1 ,38578   ,371.2,352.6,339.1
XS GIS Cut Line= 3
     2372975.588      606133.8462372426.24904105605871.948091578
2372147.22742842605933.001883158
#Sta/Elev= 30
       0 3236.25    34.8 3216.44   120.6 3173.14   142.7 3159.85   173.9 3143.58
   249.1  3108.6   290.9 3087.79   337.7 3060.64   355.4 3042.98   364.3 3035.65
   371.9 3031.66   395.3 3029.14   410.9  3031.3   421.9 3038.01     435 3041.18
   443.7 3047.23   471.6 3061.71     513 3080.21   523.8 3086.18     570 3099.37
   590.3 3102.77   603.6 3102.95   640.9 3109.63   661.3 3114.64   685.9 3118.24
   710.4 3124.62   763.7 3143.33   784.1 3147.77   822.3 3164.13   894.2 3203.87
#Mann= 3 ,-1 , 0
       0      .1       0   371.9    .045       0   410.9      .1       0
Bank Sta=371.9,410.9
XS Rating Curve= 0 ,0
Exp/Cntr=0.3,0.1

Type RM Length L Ch R = 1 ,38225   ,362.1,355.2,344.9
XS GIS Cut Line= 3
2372960.18100616605511.3847975362372686.77568842605632.459415789
      2372136.19      605863.177
#Sta/Elev= 30
       0 3263.01    34.1 3236.99    49.7 3222.67    84.7 3193.79    97.7 3179.98
   119.7 3164.37   146.2  3139.7   179.6 3114.58   189.7 3104.79   206.9 3092.09
   220.3 3079.44   231.1 3065.55   243.3 3054.96   259.7 3033.05   275.4 3022.48
   281.5 3020.74   295.1 3020.31   313.1 3021.79   337.6 3021.93   355.4  3027.8
   385.8 3027.55   395.6 3034.48   407.9 3038.91   485.5 3057.61   563.3 3071.62
   679.9 3100.92   737.1 3118.92   810.8 3144.94     851 3162.28     896 3186.29
#Mann= 3 ,-1 , 0
       0      .1       0   275.4    .045       0   313.1      .1       0
Bank Sta=275.4,313.1
XS Rating Curve= 0 ,0
Exp/Cntr=0.3,0.1

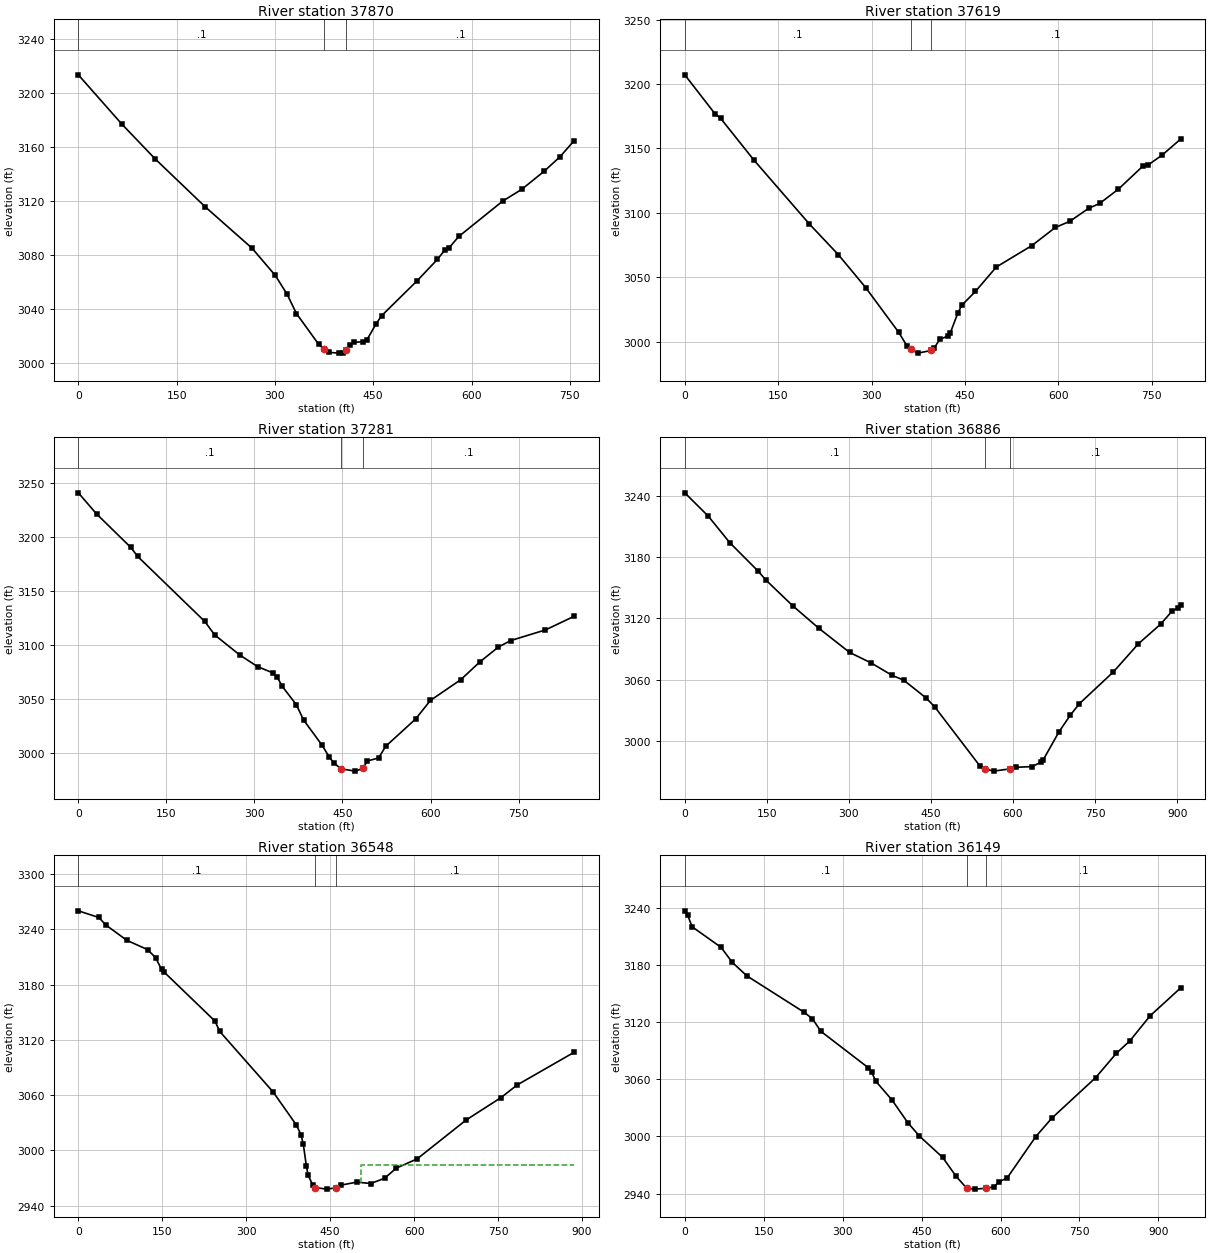
Type RM Length L Ch R = 1 ,37870   ,240.4,251.1,254.3
XS GIS Cut Line= 2
2372630.20318985605216.5578918952372128.18112947605782.665948421
#Sta/Elev= 30
       0 3213.58    66.4 3177.09   117.4 3151.25   193.9 3115.73   265.1 3085.22
   300.6 3065.05   318.7 3051.03   332.8 3036.88   366.9 3013.98   375.3 3010.32
   382.7 3008.15   397.1 3007.56   404.1 3007.97   409.1 3009.78   414.8 3013.89
   420.1 3015.59   434.8 3015.94   440.5  3017.5   454.6 3029.45   463.1 3035.41
   516.4 3060.83   547.8 3076.89   559.1 3083.79   565.9 3085.58   580.5 3093.91
   647.3 3120.01   676.7 3128.84   710.6  3142.1   734.7 3152.77   756.6 3164.81
#Mann= 3 ,-1 , 0
       0      .1       0   375.3    .045       0   409.1      .1       0
Bank Sta=375.3,409.1
XS Rating Curve= 0 ,0
Exp/Cntr=0.3,0.1

Type RM Length L Ch R = 1 ,37619   ,354.6,338.2,315.9
XS GIS Cut Line= 3
2372603.08752982605145.9397789482372148.24977846605354.561405505
2372031.19134386605626.525845614
#Sta/Elev= 30
       0 3207.23    48.8 3176.76    57.6 3173.39   110.4 3141.35   200.1 3091.32
   246.8  3067.4   290.6  3041.9   343.6 3007.13   356.8 2996.66     363 2993.89
   374.4 2990.97   395.7 2993.02   400.8 2995.06   409.6 3001.65   422.8 3004.29
   426.4 3006.51   438.4 3021.86   444.8 3028.06   466.9 3038.92   500.4 3057.87
   557.4  3074.5   595.3 3088.64   618.3 3093.34   648.8 3103.51   666.4 3107.26
   696.4 3118.32   735.9 3136.31   744.6  3137.3   766.7 3144.81   796.5 3157.28
#Mann= 3 ,-1 , 0
       0      .1       0     363    .045       0   395.7      .1       0
Bank Sta=363,395.7
XS Rating Curve= 0 ,0
Exp/Cntr=0.3,0.1

Type RM Length L Ch R = 1 ,37281   ,358.6,394.7,418.1
XS GIS Cut Line= 3
2372335.15105213604820.7934969092372044.25920063604993.917772433
 2372025.9203794605499.814488676
#Sta/Elev= 30
       0 3240.79      31 3221.28    89.4 3190.23     101 3181.94   215.3 3121.74
   232.4 3109.17   275.1 3090.59   305.3 3079.88     331 3074.15   338.5 3070.44
   347.5 3061.52   371.5 3044.53   383.6 3030.53   415.5  3006.9   427.5 2996.07
   435.5 2990.56   447.6 2985.21   471.6 2983.09   485.62985.711   491.6 2992.31
   511.6 2995.33   523.6 3006.07   574.7 3031.41   599.7 3048.52   651.7 3067.84
   683.7 3084.07   715.7 3098.01   736.7 3104.02   795.8 3113.84   844.7 3126.48
#Mann= 3 , 0 , 0
       0      .1       0   447.6    .045       0   485.6      .1       0
Bank Sta=447.6,485.6
XS Rating Curve= 0 ,0
Exp/Cntr=0.3,0.1

Type RM Length L Ch R = 1 ,36886   ,335,337.5,339.4
XS GIS Cut Line= 3
2372202.13619474604729.8729347372371882.50432316604996.011519999
2371407.64109053605118.434792631
#Sta/Elev= 30
       0 3242.77    42.9 3219.94    82.5 3193.81   133.8 3166.28     148 3157.54
     197 3132.36   245.4 3110.02   301.1 3086.64   341.1 3076.12   379.2 3064.03
     400 3059.49   440.5 3042.25     457 3033.19   539.6 2975.31   547.9 2972.68
   564.4  2970.4   595.3 2972.66   605.7 2974.15   634.6 2974.83   651.3  2979.2
   655.3  2981.6   684.1 3008.97   704.8 3025.26   721.4 3036.46   783.3 3067.45
     829 3094.98   870.1  3114.4   890.7 3127.06   900.9 3130.05   906.3 3133.04
#Mann= 3 ,-1 , 0
       0      .1       0   547.9    .045       0   595.3      .1       0
Bank Sta=547.9,595.3
XS Rating Curve= 0 ,0
Exp/Cntr=0.3,0.1

Type RM Length L Ch R = 1 ,36548   ,381.2,399.8,416.9
XS GIS Cut Line= 2
     2372166.023      604588.367      2371312.58       604826.12
#Sta/Elev= 30
       0 3260.17    36.6 3252.94    49.1 3244.81    86.4 3228.23   123.8    3218
   137.9 3209.38   148.7 3196.62   152.9 3193.86   244.2 3140.38   252.5 3129.28
     348 3063.44   389.6 3027.53   397.9 3016.93     402 3006.45   407.4 2983.15
   410.3 2973.44   418.6 2962.62   423.7 2959.56   443.5  2957.9   460.2 2959.28
   469.1 2962.23   497.5  2965.5   522.4    2964   547.1 2969.66   568.1 2980.71
   605.5 2990.81   692.7 3032.89     755 3057.23     784 3071.02   885.9 3106.54
#Mann= 3 ,-1 , 0
       0      .1       0   423.7    .045       0   460.2      .1       0
#XS Ineff= 2 , 0
                          505.13         2983.83
Permanent Ineff=
       F       F
Bank Sta=423.7,460.2
XS Rating Curve= 0 ,0
Exp/Cntr=0.3,0.1

Type RM Length L Ch R = 1 ,36149   ,473.3,474.4,476.8
XS GIS Cut Line= 3
     2372168.556       604523.072371787.25581684604494.229037896
     2371348.178      604146.996
#Sta/Elev= 30
       0  3236.6     5.6 3231.82    13.9  3219.9      69 3198.27    90.1  3182.6
   118.1 3168.34   226.5  3130.3   242.5 3123.48   258.5 3110.28   348.7 3072.06
   354.8 3067.84   362.8 3058.01   393.7 3038.25   423.8 3014.45   445.8 3000.41
   490.1    2978   515.6 2958.16     536 2945.55   551.3 2944.77   573.1 2945.75
   587.3 2947.16   597.2  2952.5   612.5 2956.41     667 2999.87   697.3 3019.11
   780.8  3061.7   819.8 3087.03   845.6 3100.15   884.3 3126.55   942.2 3155.74
#Mann= 3 ,-1 , 0
       0      .1       0     536    .045       0   573.1      .1       0
Bank Sta=536,573.1
XS Rating Curve= 0 ,0
Exp/Cntr=0.3,0.1

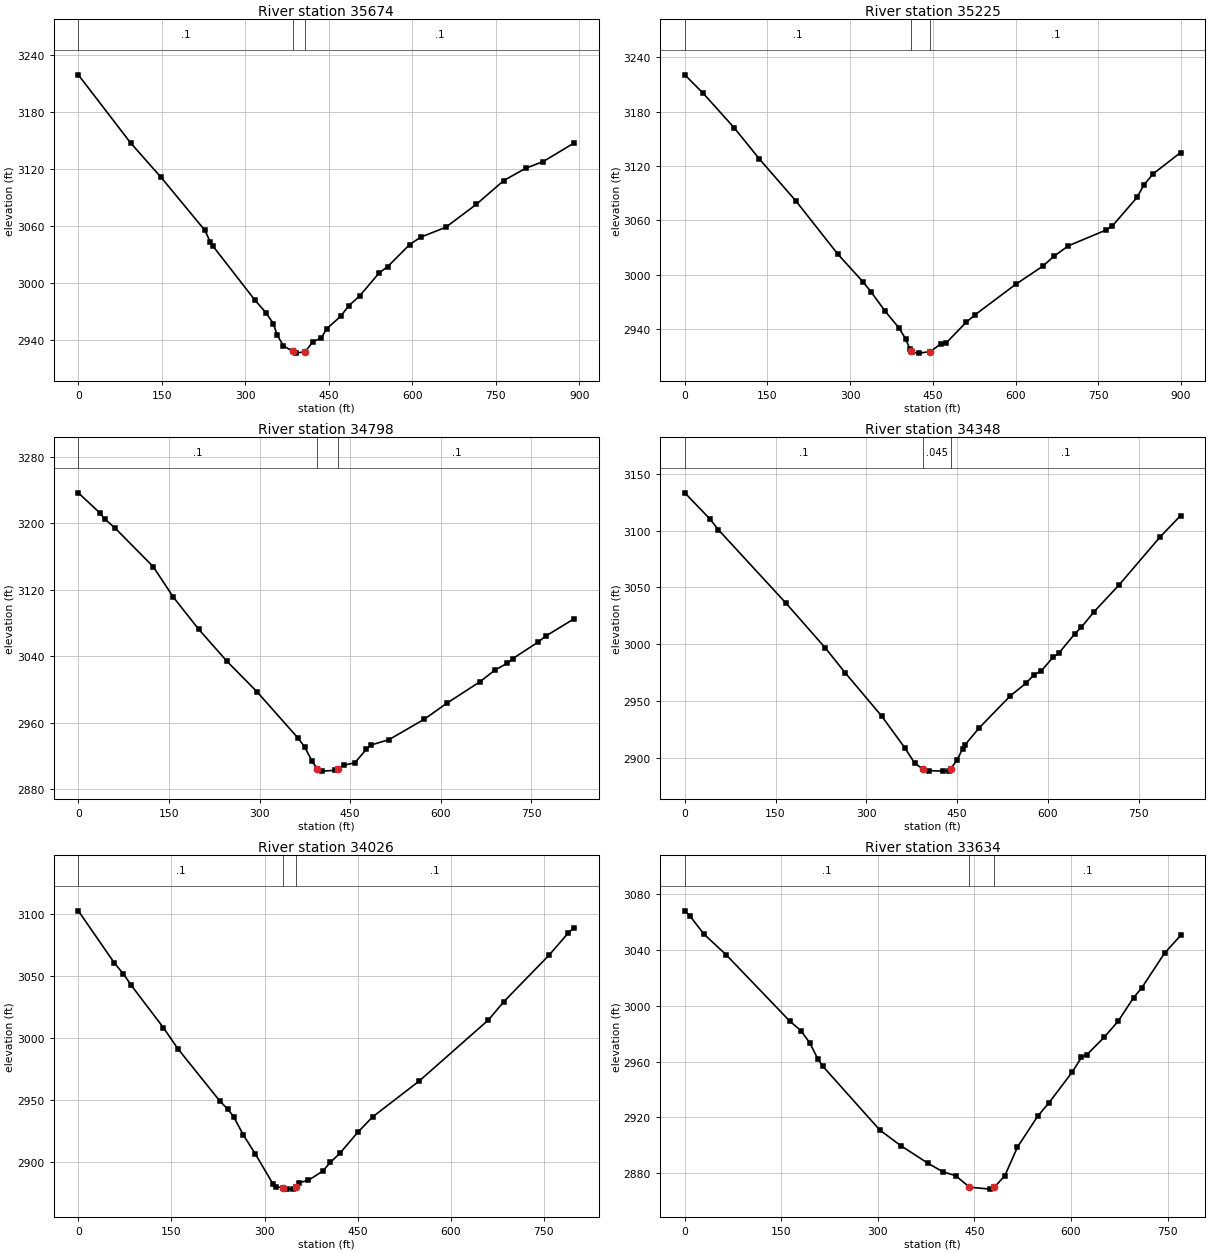
Type RM Length L Ch R = 1 ,35674   ,459.7,449.4,438.2
XS GIS Cut Line= 2
2372333.72202144604339.1606012552371617.06598159603809.743923326
#Sta/Elev= 30
       0 3218.82    93.8 3147.26   148.6 3110.97   227.5 3055.05   237.4 3042.43
   242.4 3038.17   316.9 2981.99   337.1  2968.4   350.5 2956.97   357.2 2945.05
   368.4 2933.64   385.6 2927.66   391.6 2925.86   407.82927.446   421.4  2937.8
   436.4 2941.78   446.3  2951.5   471.2 2964.52   486.1 2975.81   505.7 2986.15
   540.8 3010.43   555.7 3016.83   595.5  3040.2   615.4 3047.98   660.2 3058.29
   714.9 3082.35   764.6 3107.58   804.4 3120.59   835.2 3127.45     891  3147.1
#Mann= 3 ,-1 , 0
       0      .1       0   385.6    .045       0   407.8      .1       0
Bank Sta=385.6,407.8
XS Rating Curve= 0 ,0
Exp/Cntr=0.3,0.1

Type RM Length L Ch R = 1 ,35225   ,426.6,426.6,422.6
XS GIS Cut Line= 2
2372507.57977895603602.6106175442371625.19822807603777.053477194
#Sta/Elev= 30
       0 3220.49    33.5 3200.02    89.5  3162.1   135.4 3127.53   201.8  3081.1
   278.1 3022.24     323 2992.24     338 2980.91   363.7 2959.39   388.2 2941.45
   400.4 2929.34   408.6 2917.74   411.12915.567   412.9 2914.14   424.9 2913.36
   445.3    2915   463.9 2923.32   474.2 2924.61   510.5 2947.43   526.8 2955.76
   600.1 2989.19   649.2 3009.22   669.5 3020.07   695.4 3031.67   764.6 3049.33
   775.6 3053.69   820.4  3085.2   832.6 3098.72   849.4  3111.1   899.5 3134.77
#Mann= 3 ,-1 , 0
       0      .1       0   411.1    .045       0   445.3      .1       0
Bank Sta=411.1,445.3
XS Rating Curve= 0 ,0
Exp/Cntr=0.3,0.1

Type RM Length L Ch R = 1 ,34798   ,451.1,450.1,444.1
XS GIS Cut Line= 3
     2372312.125      603175.769     2371922.541      603303.294
      2371529.52      603423.063
#Sta/Elev= 30
       0 3236.73    35.1 3212.88    43.5 3205.35    60.4 3194.59   124.1 3147.68
   157.2 3111.16   199.3 3072.37   245.6  3034.2   296.1  2996.9   363.4 2941.61
   374.6 2930.79   387.2 2913.19   395.72904.302     404 2901.59   425.5 2902.61
   430.6 2904.01     439 2908.73   457.5 2911.49   476.6 2927.71     485 2933.12
   514.3  2939.5   572.9 2964.18   610.4 2983.57   664.8 3009.16   689.9 3023.47
   710.4 3031.56   719.2 3037.08     761 3056.93   773.5 3064.09   820.8 3085.05
#Mann= 3 ,-1 , 0
       0      .1       0   395.7    .045       0   430.6      .1       0
Bank Sta=395.7,430.6
XS Rating Curve= 0 ,0
Exp/Cntr=0.3,0.1

Type RM Length L Ch R = 1 ,34348   ,325.9,322.6,320.3
XS GIS Cut Line= 3
2372071.78560429602721.592453975     2371709.269      602915.213
     2371348.587      603106.774
#Sta/Elev= 30
       0  3133.1      42 3109.85    55.6  3100.6   167.3 3036.13   232.5 2996.66
   264.8 2975.17   325.4 2936.95     364  2908.8   380.1 2895.39   393.3 2890.61
   403.7 2889.04   427.4 2888.63   436.3 2889.14   439.2  2890.6   450.1 2898.44
   459.1 2908.37   462.9 2911.61     487  2926.9   538.2 2954.88   563.5  2965.7
   576.9 2973.15   589.4 2976.87   608.6 2988.62   617.7 2991.99   644.8 3009.41
   655.2 3014.94   676.5 3028.74   717.3 3051.97   785.2 3094.18   819.4 3113.13
#Mann= 3 ,-1 , 0
       0      .1       0   393.3    .045       0   439.2      .1       0
Bank Sta=393.3,439.2
XS Rating Curve= 0 ,0
Exp/Cntr=0.3,0.1

Type RM Length L Ch R = 1 ,34026   ,384.8,391.9,399.4
XS GIS Cut Line= 3
2371788.91472043602374.5475522492371566.00645614602629.659395711
2371269.80845614602981.924395711
#Sta/Elev= 30
       0 3102.58      58 3060.58    72.7 3051.66    85.4 3042.45     137 3008.43
   160.5 2991.36   228.2 2949.14   240.4 2942.93   250.1 2936.75     266 2921.84
   285.3 2906.52   313.3 2882.68   319.3 2880.13   329.8 2879.26   336.3 2878.24
   345.6 2878.37   350.5 2879.85   356.3 2883.56   370.4 2885.27   393.6 2892.67
     406 2899.74   421.5 2907.16   450.1 2923.94   474.4 2936.53     549 2965.27
   660.8 3014.59   685.7 3029.39   758.5  3066.8   789.8  3084.9     799 3089.13
#Mann= 3 ,-1 , 0
       0      .1       0   329.8    .045       0   350.5      .1       0
Bank Sta=329.8,350.5
XS Rating Curve= 0 ,0
Exp/Cntr=0.3,0.1

Type RM Length L Ch R = 1 ,33634   ,333.9,346.3,354.3
XS GIS Cut Line= 2
2371540.77731727602234.8753142752370966.01220712602747.530736306
#Sta/Elev= 30
       0 3068.11     8.1  3064.4    29.5 3051.52    63.8 3036.77   162.9  2989.1
   180.3 2982.14   194.1 2973.42   206.4 2962.07   213.9  2956.9   302.9 2910.88
   335.7  2899.6   378.2 2886.91   400.9 2880.94   420.8 2878.11   442.2  2869.9
   474.4 2868.49   480.8 2869.81   497.2 2878.16   516.8 2898.66   548.2 2920.83
   565.5 2930.31   602.1 2952.65   616.2 2962.99   624.5 2964.91   651.3 2977.31
   673.1 2988.91   697.1 3005.79   709.7 3012.77   745.2 3037.71   770.2 3050.42
#Mann= 3 ,-1 , 0
       0      .1       0   442.2    .045       0   480.8      .1       0
Bank Sta=442.2,480.8
XS Rating Curve= 0 ,0
Exp/Cntr=0.3,0.1