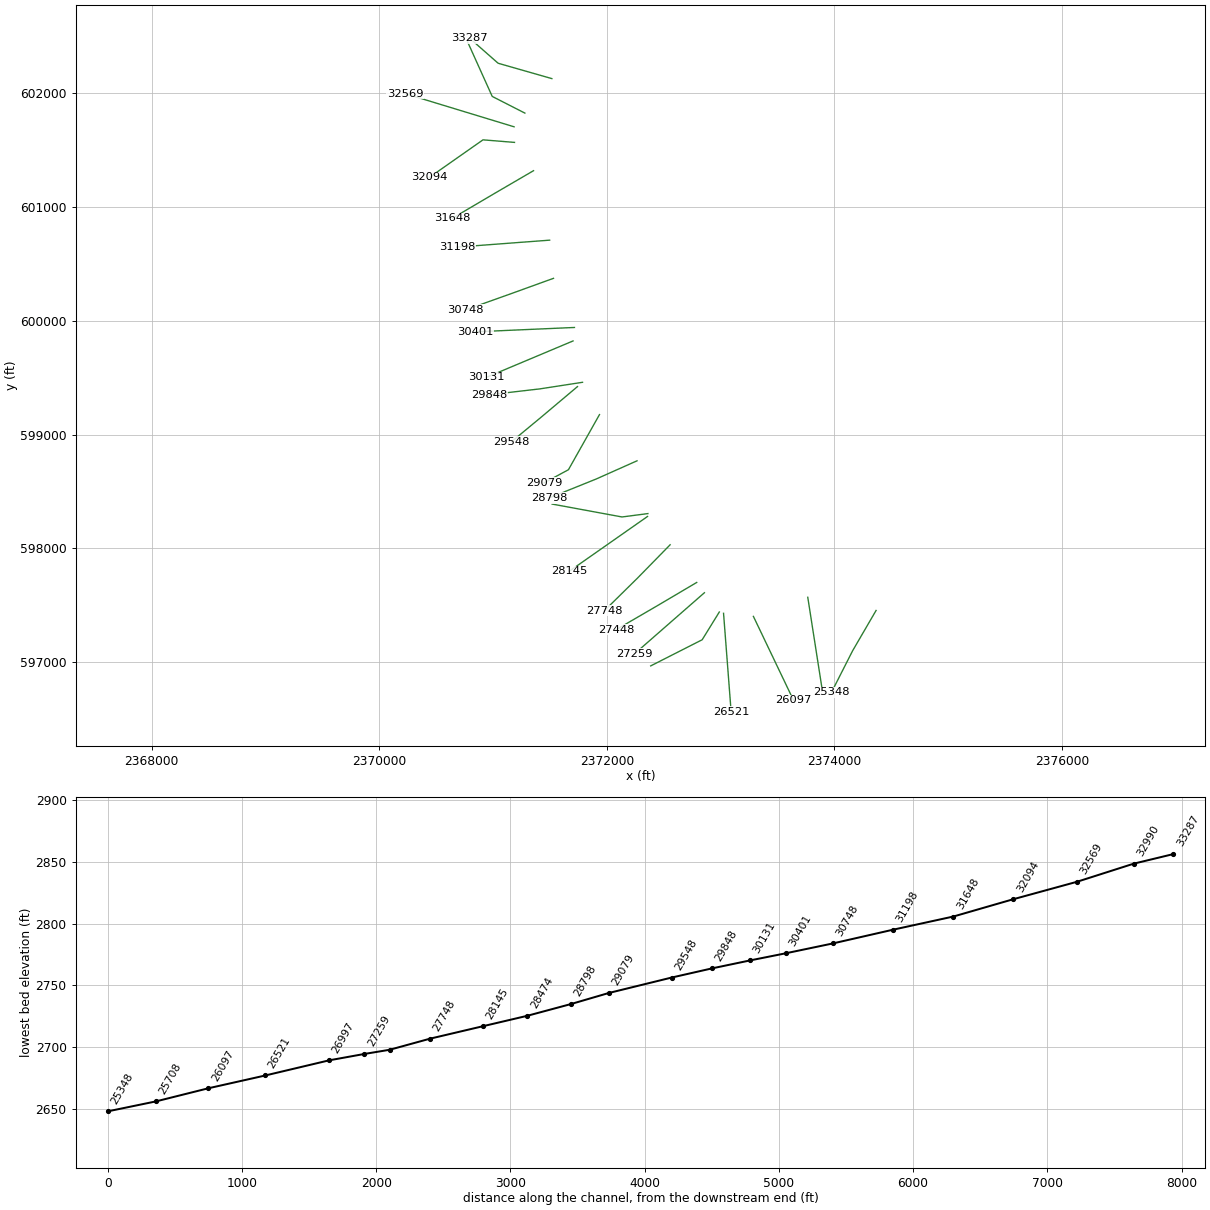
HEC-RAS study BIGRN.prj: BIGRN

--- BIGRN.g01 (geometry) --- (continued)

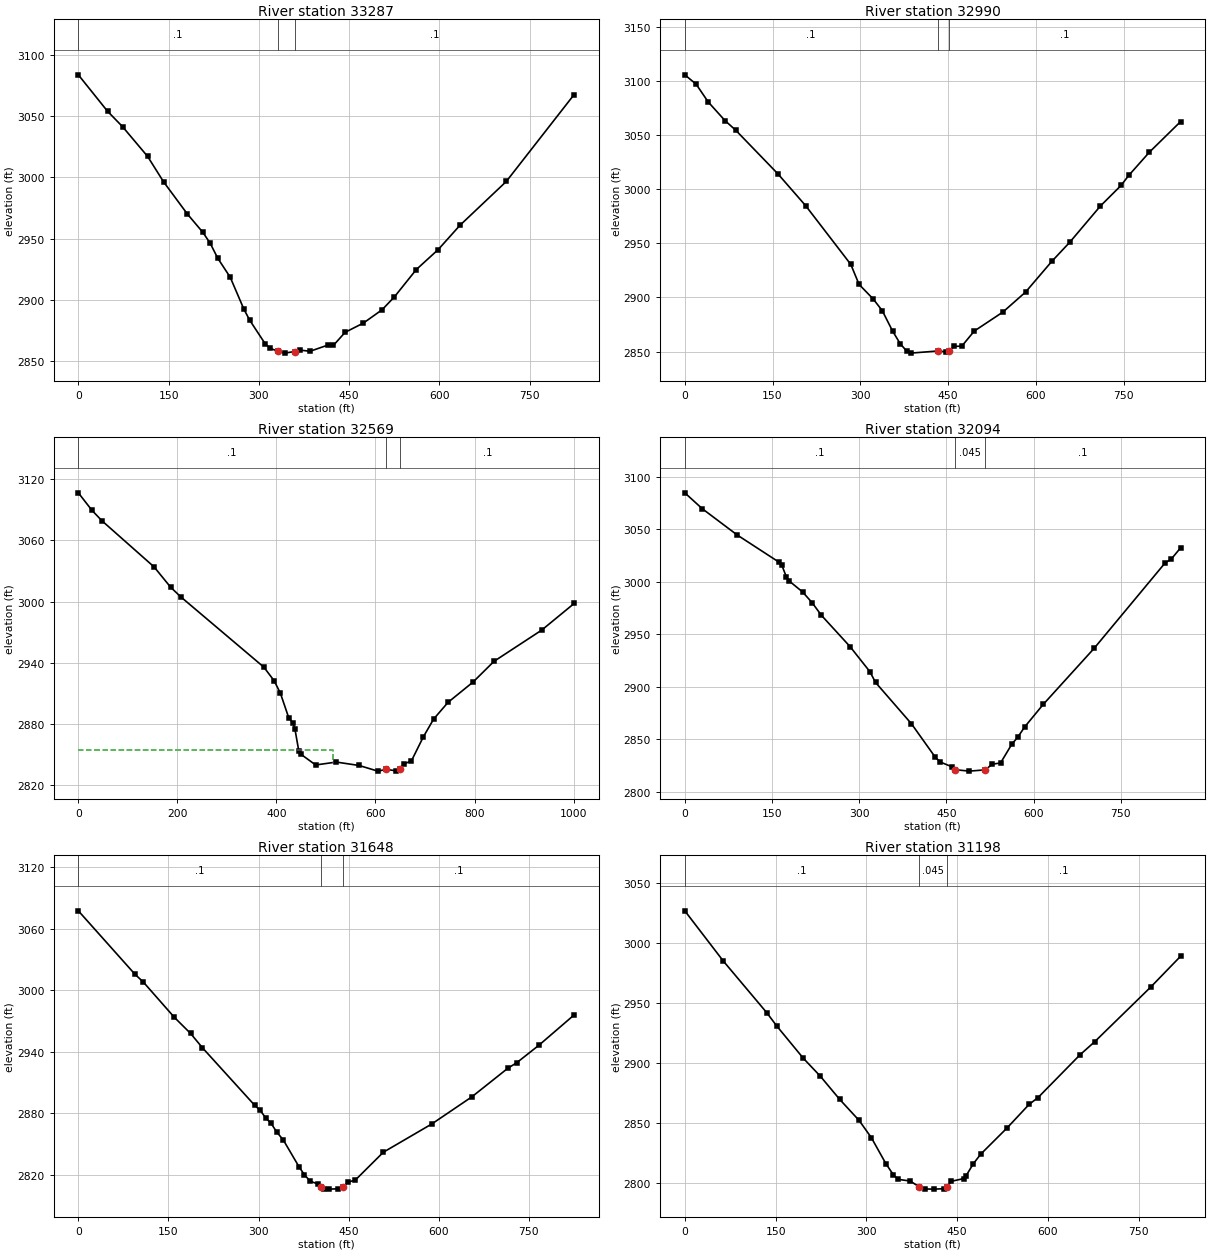
Type RM Length L Ch R = 1 ,33287   ,305.5,296.9,281.8
XS GIS Cut Line= 3
2371517.39990431602129.4724303692371044.76087158602264.651856843
   2370795.31348      602484.158
#Sta/Elev= 30
       0 3083.85    48.5 3054.09    73.5 3041.45   115.1 3017.17   141.6 2996.41
   181.2 2970.07   207.1 2954.98   219.1 2946.17   231.6    2934   252.4 2918.37
     275  2892.4   284.7 2883.33   310.6 2863.91     319 2860.24   331.4 2857.96
     343 2856.36   359.2 2857.67   368.8 2858.81     385 2857.87   414.6 2862.92
   423.9 2862.71   443.3 2873.36   473.8 2880.97   504.9 2891.87   525.3  2902.4
   561.6 2924.68   597.9 2940.97   634.2 2960.88   711.1 2996.67   823.9 3067.76
#Mann= 3 ,-1 , 0
       0      .1       0   331.4    .045       0   359.2      .1       0
Bank Sta=331.4,359.2
XS Rating Curve= 0 ,0
Exp/Cntr=0.3,0.1

Type RM Length L Ch R = 1 ,32990   ,414.8,421.1,438
XS GIS Cut Line= 3
2371280.01397368601826.3011810542370993.10716842601972.846923156
2370776.93553158602451.704662106
#Sta/Elev= 30
       0 3105.62    19.4 3096.97      40 3080.56    68.8  3063.3    86.8 3054.59
     159 3014.24   206.5 2984.81   283.8 2930.48   297.9 2912.02   322.2 2898.48
   337.6 2887.75   355.1 2869.01   368.3 2857.23   379.9 2850.07   385.9 2848.56
   432.22850.516   446.4  2849.8   451.7 2850.76   460.5 2854.71   473.7  2855.1
   494.8 2868.93   543.8  2886.5   582.5 2904.94   627.2  2933.2   658.1 2950.99
   710.6 2984.52   745.7  3003.4   758.9 3012.68     794 3034.05   847.6 3062.44
#Mann= 3 ,-1 , 0
       0      .1       0   432.2    .045       0   451.7      .1       0
Bank Sta=432.2,451.7
XS Rating Curve= 0 ,0
Exp/Cntr=0.3,0.1

Type RM Length L Ch R = 1 ,32569   ,460,475.3,491.5
XS GIS Cut Line= 2
2371185.17769825 601705.89708772      2370227.37      601997.392
#Sta/Elev= 30
       0 3106.49    27.6 3089.31    47.6 3079.15   153.1 3033.88   186.5 3013.98
   207.4  3004.4   374.7 2935.73   395.6  2922.3   408.1 2910.13   424.8  2886.3
   433.2 2881.29   437.4  2875.1   445.1 2853.81   449.9 2850.31   479.2 2839.98
     521 2842.82     567 2839.48   604.6 2833.95   621.42835.639   642.3 2834.22
   650.3 2836.01   656.7 2840.75   672.7 2844.06   696.6 2867.46   717.5 2884.95
   746.4 2901.24     797 2921.16   839.4 2941.49   935.6 2972.02  1001.2 2998.15
#Mann= 3 ,-1 , 0
       0      .1       0   621.4    .045       0   650.3      .1       0
#XS Ineff= 2 , 0
          513.65 2855.09
Permanent Ineff=
       F       F
Bank Sta=621.4,650.3
XS Rating Curve= 0 ,0
Exp/Cntr=0.3,0.1

Type RM Length L Ch R = 1 ,32094   ,446.8,445.8,443.7
XS GIS Cut Line= 3
     2371188.758      601568.8142370911.92198948601591.181814037
2370441.15499298601261.063417545
#Sta/Elev= 30
       0 3084.66    30.1 3069.51    90.3 3044.47   162.5 3018.51   166.6 3016.17
   174.6 3004.73   178.6 3001.17   202.7 2990.27   219.2 2979.96   234.8 2968.17
   284.1 2938.38   318.3 2914.48     328 2904.23   389.7 2864.94     431 2832.86
   439.6  2828.4   459.7 2823.88   464.8 2821.18   489.3 2819.81   517.1 2821.04
   528.3 2826.37     543 2827.56   562.5 2845.54   572.3 2851.88   584.8 2862.08
   616.3 2883.23   703.8 2936.57   826.3 3018.14   836.1 3021.27   852.7 3032.35
#Mann= 3 ,-1 , 0
       0      .1       0   464.8    .045       0   517.1      .1       0
Bank Sta=464.8,517.1
XS Rating Curve= 0 ,0
Exp/Cntr=0.3,0.1

Type RM Length L Ch R = 1 ,31648   ,456,449.9,438.2
XS GIS Cut Line= 3
2371356.18748343601320.036637427     2370997.135      601110.572
     2370644.147      600902.452
#Sta/Elev= 30
       0 3077.52    94.3 3015.58   108.2 3007.99   159.8 2973.57   186.9  2957.8
   206.6 2943.84   293.4  2887.8   302.7 2882.79   311.9 2875.36   320.7 2870.24
   330.5  2861.4   341.2 2853.84   367.6 2827.46   376.3 2819.92     386 2813.55
   399.2 2810.76   404.6 2807.72   409.2 2806.11   417.2 2805.82   432.4 2806.14
   440.6 2807.94   449.3 2812.77     461 2814.57   507.8 2841.84   588.3 2869.37
   655.3 2895.97   715.6 2924.06   729.6 2929.08   766.7 2946.24   825.5 2975.91
#Mann= 3 ,-1 , 0
       0      .1       0   404.6    .045       0   440.6      .1       0
Bank Sta=404.6,440.6
XS Rating Curve= 0 ,0
Exp/Cntr=0.3,0.1

Type RM Length L Ch R = 1 ,31198   ,445,450.1,455.7
XS GIS Cut Line= 3
     2371497.951      600709.314     2371089.601      600678.642
     2370681.251       600647.97
#Sta/Elev= 30
       0 3026.81    63.4 2985.14   135.6 2941.89   151.6 2931.12   195.8 2904.07
   223.8 2889.18   255.9 2869.83     288 2852.28   308.1 2838.03   332.1  2816.4
   344.2 2807.31   352.2 2803.31   372.3 2801.88   386.8  2797.2   396.3 2795.29
   411.9 2795.15   428.4 2795.51   432.4 2796.64   440.4 2801.65   460.6 2803.94
   464.5 2806.17   476.5  2816.2   488.6 2824.15   532.7 2846.28   568.6 2865.62
   583.6 2871.42     653 2907.05   677.1 2917.87   769.4 2963.24     819 2989.02
#Mann= 3 ,-1 , 0
       0      .1       0   386.8    .045       0   432.4      .1       0
Bank Sta=386.8,432.4
XS Rating Curve= 0 ,0
Exp/Cntr=0.3,0.1

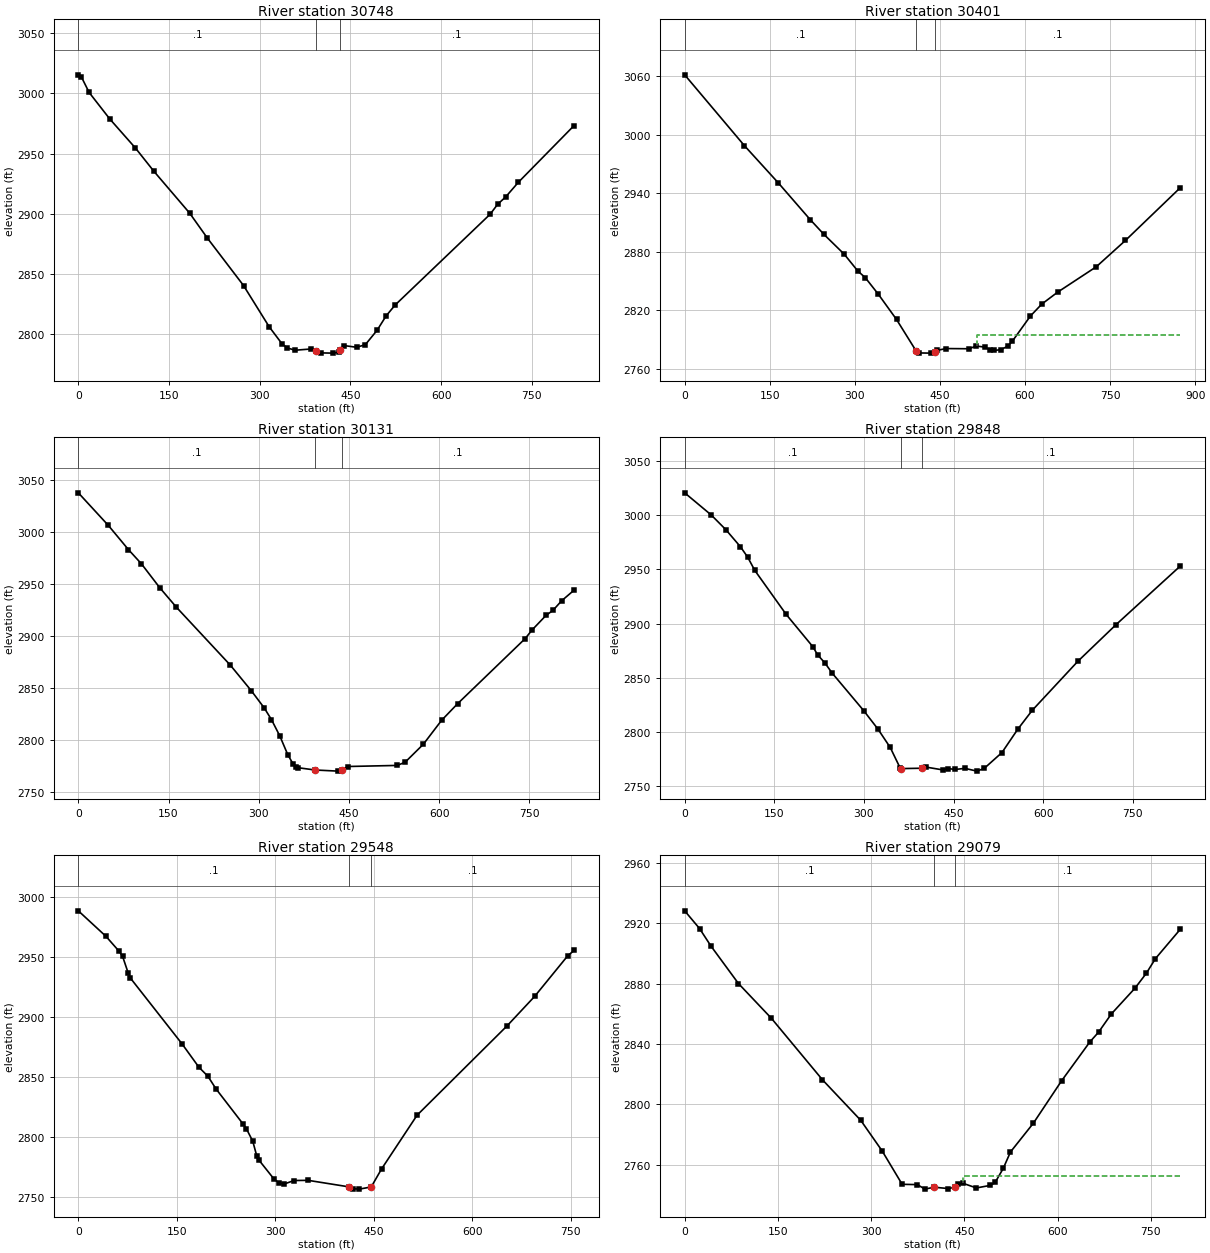
Type RM Length L Ch R = 1 ,30748   ,354.5,347.7,346.1
XS GIS Cut Line= 3
     2371531.612      600373.763     2371145.487      600234.018
     2370759.956      600096.569
#Sta/Elev= 30
       0 3015.51     5.2 3013.61    17.9 3000.82      52  2978.8    94.5 2954.58
   124.7 2935.44   184.1 2900.47   213.6 2879.57   273.2 2840.25   315.7 2805.88
   337.1  2791.6   345.5 2788.37   358.3  2786.4   384.6 2787.43   393.4 2785.68
   400.8 2784.18     422 2783.99   430.5 2784.76   432.62786.728     439 2790.31
   460.3 2788.86   474.7 2791.02   494.2 2803.04   509.1 2814.97     524 2824.02
   681.1 2899.53   693.8 2907.98   706.6 2913.81   727.8 2926.12   819.9 2973.28
#Mann= 3 ,-1 , 0
       0      .1       0   393.4    .045       0   432.6      .1       0
Bank Sta=393.4,432.6
XS Rating Curve= 0 ,0
Exp/Cntr=0.3,0.1

Type RM Length L Ch R = 1 ,30401   ,263.1,269.8,278.6
XS GIS Cut Line= 2
2371715.84432944599941.8197699792370842.66897271599903.531329435
#Sta/Elev= 30
       0 3061.45   105.2  2988.9   165.3  2950.5   221.3 2912.99   245.3 2897.98
   281.4 2877.45   305.4  2860.2   318.4  2853.5   341.5 2836.41   373.5  2810.6
   408.5 2777.89   413.5 2776.29   433.5 2776.09   441.1 2777.37   445.5 2779.02
   461.5 2780.78   501.6 2780.57   513.6 2783.36   529.6 2782.25   537.6 2779.63
   545.6 2778.81   557.6 2779.67   569.6 2783.21   577.7 2788.31   609.7 2814.22
   629.7 2826.41   657.7 2838.65   725.8 2864.68     777 2891.58     874 2945.82
#Mann= 3 ,-1 , 0
       0      .1       0   408.5    .045       0   441.1      .1       0
#XS Ineff= 2 , 0
                          515.42         2795.09
Permanent Ineff=
       F       F
Bank Sta=408.5,441.1
XS Rating Curve= 0 ,0
Exp/Cntr=0.3,0.1

Type RM Length L Ch R = 1 ,30131   ,284.6,282.4,274.2
XS GIS Cut Line= 2
      2371703.74      599823.368     2370943.778      599503.853
#Sta/Elev= 30
       0 3037.61      50 3006.24    83.3 2983.08     105 2969.37   135.5 2946.38
     163 2927.76   252.8 2872.04   287.5 2847.61   309.2 2830.91   321.2 2819.72
   335.2 2803.88   348.2  2786.2   356.9 2777.33   361.2 2774.61   365.6  2773.5
   393.4 2771.33   431.9 2770.23     438 2771.04     448 2774.67   530.5 2775.71
   543.5 2778.82   573.8 2796.07   604.2 2819.08   630.8 2835.04   743.1 2897.55
   754.6 2905.85   777.8 2919.86   789.3 2924.66   803.8  2933.9   824.4 2944.09
#Mann= 3 ,-1 , 0
       0      .1       0   393.4    .045       0     438      .1       0
Bank Sta=393.4,438
XS Rating Curve= 0 ,0
Exp/Cntr=0.3,0.1

Type RM Length L Ch R = 1 ,29848   ,291.4,300.3,309.2
XS GIS Cut Line= 3
2371786.78633789599459.774805263     2371411.985      599401.897
2370964.36996105599350.121974736
#Sta/Elev= 30
       0 3020.57    44.6 3000.06    68.8 2986.64    93.1 2970.98   105.3 2961.37
   117.4 2948.97     170 2908.32   214.6 2878.55   222.6 2871.05   234.8 2863.56
   246.9 2854.24   299.6 2819.67   323.4 2802.69   344.1 2785.62   360.3 2767.12
   362.8 2766.15   396.6 2766.48   404.7 2767.47   432.8 2764.87   440.8 2766.17
     453 2765.35   469.1 2766.37   489.2 2763.81   501.3 2766.27   531.1 2780.95
   557.7 2802.57   581.8  2819.9   658.3 2865.22   722.3 2899.07   829.8 2953.11
#Mann= 3 ,-1 , 0
       0      .1       0   362.8    .045       0   396.6      .1       0
Bank Sta=362.8,396.6
XS Rating Curve= 0 ,0
Exp/Cntr=0.3,0.1

Type RM Length L Ch R = 1 ,29548   ,465.3,468.7,476.6
XS GIS Cut Line= 3
2371742.49278145599421.984928369     2371417.095      599148.007
2371163.22116677598937.923014455
#Sta/Elev= 30
       0  2988.1    42.1 2966.85    62.4 2954.25    67.3 2950.34    75.8 2936.56
    79.3 2932.11   158.2 2877.14   183.7 2857.84   197.3 2850.39   209.7 2839.83
   250.7 2810.74   255.9 2806.67   265.6 2796.36   271.7 2784.07   274.5 2780.94
   297.7 2764.99   305.8 2761.44   313.4 2760.64   328.5 2763.57     350 2763.71
   412.8 2758.23     418 2756.75   427.8  2756.4     446  2758.2   461.9 2773.31
   515.9 2817.97     653 2892.38   694.9 2916.87   745.1 2950.54   754.9 2955.15
#Mann= 3 ,-1 , 0
       0      .1       0   412.8    .045       0     446      .1       0
Bank Sta=412.8,446
XS Rating Curve= 0 ,0
Exp/Cntr=0.3,0.1

Type RM Length L Ch R = 1 ,29079   ,288.7,281.2,264.6
XS GIS Cut Line= 3
     2371935.747      599175.7172371662.91577001598691.116830207
2371450.46974714  598576.8088507
#Sta/Elev= 30
       0 2928.38    23.9 2916.65    42.3 2905.01    86.5 2880.19   139.4 2857.18
   221.6 2816.39   283.2 2789.52   317.7 2769.17   349.8 2747.09   374.3 2746.87
   386.5 2743.89     401 2745.17   424.3 2744.26   434.2  2745.2   438.9 2747.19
   447.8 2747.74   469.2 2744.67   491.8 2746.39   499.4 2748.32   512.4  2757.6
   524.1 2768.54   560.9  2787.6   606.3  2815.7   651.7 2841.43   665.7 2847.91
   686.4 2860.05   724.4 2877.12   742.6 2886.98   757.2 2896.67   797.4 2916.23
#Mann= 3 ,-1 , 0
       0      .1       0     401    .045       0   434.2      .1       0
#XS Ineff= 2 , 0
                          447.99          2752.9
Permanent Ineff=
       F       F
Bank Sta=401,434.2
XS Rating Curve= 0 ,0
Exp/Cntr=0.3,0.1

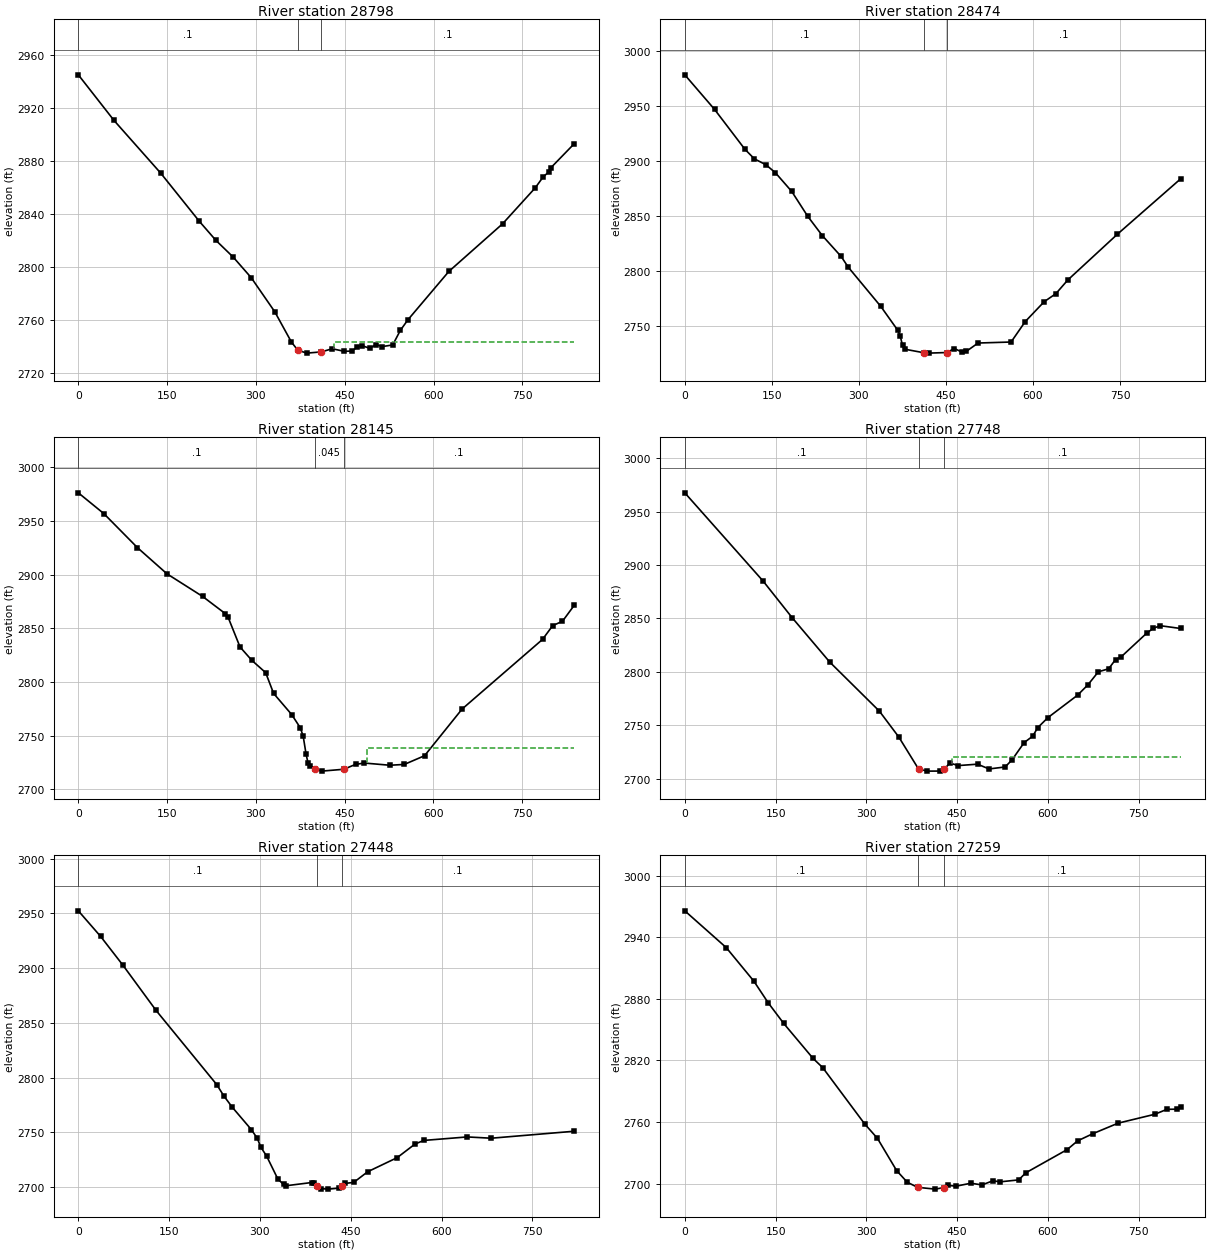
Type RM Length L Ch R = 1 ,28798   ,335,324.7,313.6
XS GIS Cut Line= 3
2372265.76958421 598769.53820842     2371908.928      598610.434
      2371494.52      598443.065
#Sta/Elev= 30
       0 2945.12    60.2 2910.71   139.1 2870.92   204.2 2834.61   232.4 2820.11
   261.8 2807.39   292.1 2791.91   331.8 2766.23   360.1 2743.22   370.8 2737.17
     386 2734.96   410.5 2735.89   428.9 2738.27   449.1 2736.33   462.1 2736.51
   470.7 2739.43   479.3  2740.6   492.3 2738.58   502.7 2741.36   513.8 2739.92
   531.1 2741.15     544 2752.16     557 2760.26     626 2796.69   716.6 2832.58
   771.8 2859.74   785.6 2868.25   794.3 2871.55   798.6  2875.1   837.6 2893.05
#Mann= 3 ,-1 , 0
       0      .1       0   370.8    .045       0   410.5      .1       0
#XS Ineff= 2 , 0
                          432.36         2743.07
Permanent Ineff=
       F       F
Bank Sta=370.8,410.5
XS Rating Curve= 0 ,0
Exp/Cntr=0.3,0.1

Type RM Length L Ch R = 1 ,28474   ,306.3,328.4,339.4
XS GIS Cut Line= 3
       2372361.5      598305.665 2372134.0809946598275.900527988
2371519.49231547598389.343157137
#Sta/Elev= 30
       0 2978.64    51.2 2947.23   103.6  2910.9   119.8 2902.26   139.9 2896.77
   156.1 2889.58   184.3 2872.52   211.8 2849.96   236.8 2832.47   269.4 2813.38
   281.6 2803.68   337.8  2767.9     367  2746.2     371 2741.32   375.1 2732.61
   379.2 2729.03   411.7 2725.83   419.9 2725.47   451.1 2726.02   464.6 2729.66
   476.8 2726.55   484.9 2727.02   505.3 2734.66   562.2 2735.58   586.6 2754.19
   619.2 2772.24   639.5 2779.63   659.8 2791.95   745.3 2833.62   854.3 2884.01
#Mann= 3 ,-1 , 0
       0      .1       0   411.7    .045       0   451.1      .1       0
Bank Sta=411.7,451.1
XS Rating Curve= 0 ,0
Exp/Cntr=0.3,0.1

Type RM Length L Ch R = 1 ,28145   ,391.7,397.1,399.9
XS GIS Cut Line= 2
2372358.10030468598280.224730909     2371671.567      597799.514
#Sta/Elev= 30
       0 2976.17    43.2 2956.78     100 2925.09   149.8 2900.78   210.2 2879.66
   248.3 2863.76   253.1 2860.42   273.3 2832.66   293.4 2820.15   316.6 2808.78
   330.1 2789.42   360.6 2769.79   375.2 2757.43   380.1 2749.52     385 2732.74
   388.2 2724.81   391.1 2721.76   399.8 2719.36   411.2 2717.09   448.7 2718.82
   468.6 2723.37   483.5 2724.62   526.6 2722.56     551 2723.33   585.2 2731.42
   648.7  2774.9   784.6  2839.7   801.8 2852.54   818.3 2856.59   838.1 2871.35
#Mann= 3 ,-1 , 0
       0      .1       0   399.8    .045       0   448.7      .1       0
#XS Ineff= 2 , 0
                          487.68         2738.48
Permanent Ineff=
       F       F
Bank Sta=399.8,448.7
XS Rating Curve= 0 ,0
Exp/Cntr=0.3,0.1

Type RM Length L Ch R = 1 ,27748   ,305.6,299.8,294.6
XS GIS Cut Line= 3
2372556.91221032598031.423789684     2372270.619      597739.084
     2371978.512      597451.423
#Sta/Elev= 30
       0 2967.75   129.5 2884.96   177.3 2850.76   239.5 2809.11   321.5 2763.12
   353.5 2738.91   386.1 2708.95   400.7 2706.93   420.9 2706.99     429 2709.09
     438 2714.52   451.7 2712.13   483.6 2713.45   502.6 2708.97   529.2 2710.83
   540.6  2717.5   560.6 2733.68   574.8  2739.7     583 2747.66   599.9 2757.09
   648.9 2778.14     666 2787.84   683.1 2799.99   700.2 2802.85   711.6 2811.49
   720.4 2813.79   762.9 2836.15   774.1 2840.87   785.7 2843.21   819.1 2840.61
#Mann= 3 ,-1 , 0
       0      .1       0   386.1    .045       0     429      .1       0
#XS Ineff= 2 , 0
                          440.71         2720.35
Permanent Ineff=
       F       F
Bank Sta=386.1,429
XS Rating Curve= 0 ,0
Exp/Cntr=0.3,0.1

Type RM Length L Ch R = 1 ,27448   ,185.7,188.7,193.3
XS GIS Cut Line= 3
     2372790.488      597700.213     2372437.919      597491.896
     2372083.882      597286.115
#Sta/Elev= 30
       0 2952.37    36.9 2928.92    73.8 2902.56   128.4 2861.33   228.6 2793.54
   240.3 2783.21   254.2 2772.89   285.7 2752.44   295.7 2744.32   301.4 2736.36
     311 2728.18   329.6 2707.18   338.9 2702.28   343.5  2701.1   385.3 2704.01
     390 2703.55     395  2700.9   400.9  2698.4   413.2 2697.98   430.1  2698.9
   435.4 2701.08   440.9 2703.24   454.8 2704.11     478 2713.88   526.7 2726.77
   555.9 2739.11   570.5 2742.49   642.3 2745.69   682.1 2744.52     819 2750.89
#Mann= 3 ,-1 , 0
       0      .1       0     395    .045       0   435.4      .1       0
Bank Sta=395,435.4
XS Rating Curve= 0 ,0
Exp/Cntr=0.3,0.1

Type RM Length L Ch R = 1 ,27259   ,267.8,262.4,256.8
XS GIS Cut Line= 3
2372858.26447238597609.9774141212372549.99147238597340.427414121
2372241.71747239597070.876414121
#Sta/Elev= 30
       0  2965.8    68.4    2930   114.1 2897.24   137.9 2876.04   163.4 2856.04
   211.9 2821.95   227.8    2813   296.9 2758.28   318.2 2744.07     350 2712.57
   367.5 2701.29   384.5 2696.33   413.8 2694.58   427.6 2696.09   435.1 2698.19
   448.3 2697.48   472.6 2700.35   490.8 2698.67   509.1 2702.75   520.6 2701.67
   551.6 2703.58   563.1 2710.42   631.7 2733.16   648.8 2741.61   674.2 2748.66
   715.7 2758.86   776.4 2767.54   796.4 2772.37   812.3 2772.49     819  2774.9
#Mann= 3 ,-1 , 0
       0      .1       0   384.5    .045       0   427.6      .1       0
Bank Sta=384.5,427.6
XS Rating Curve= 0 ,0
Exp/Cntr=0.3,0.1

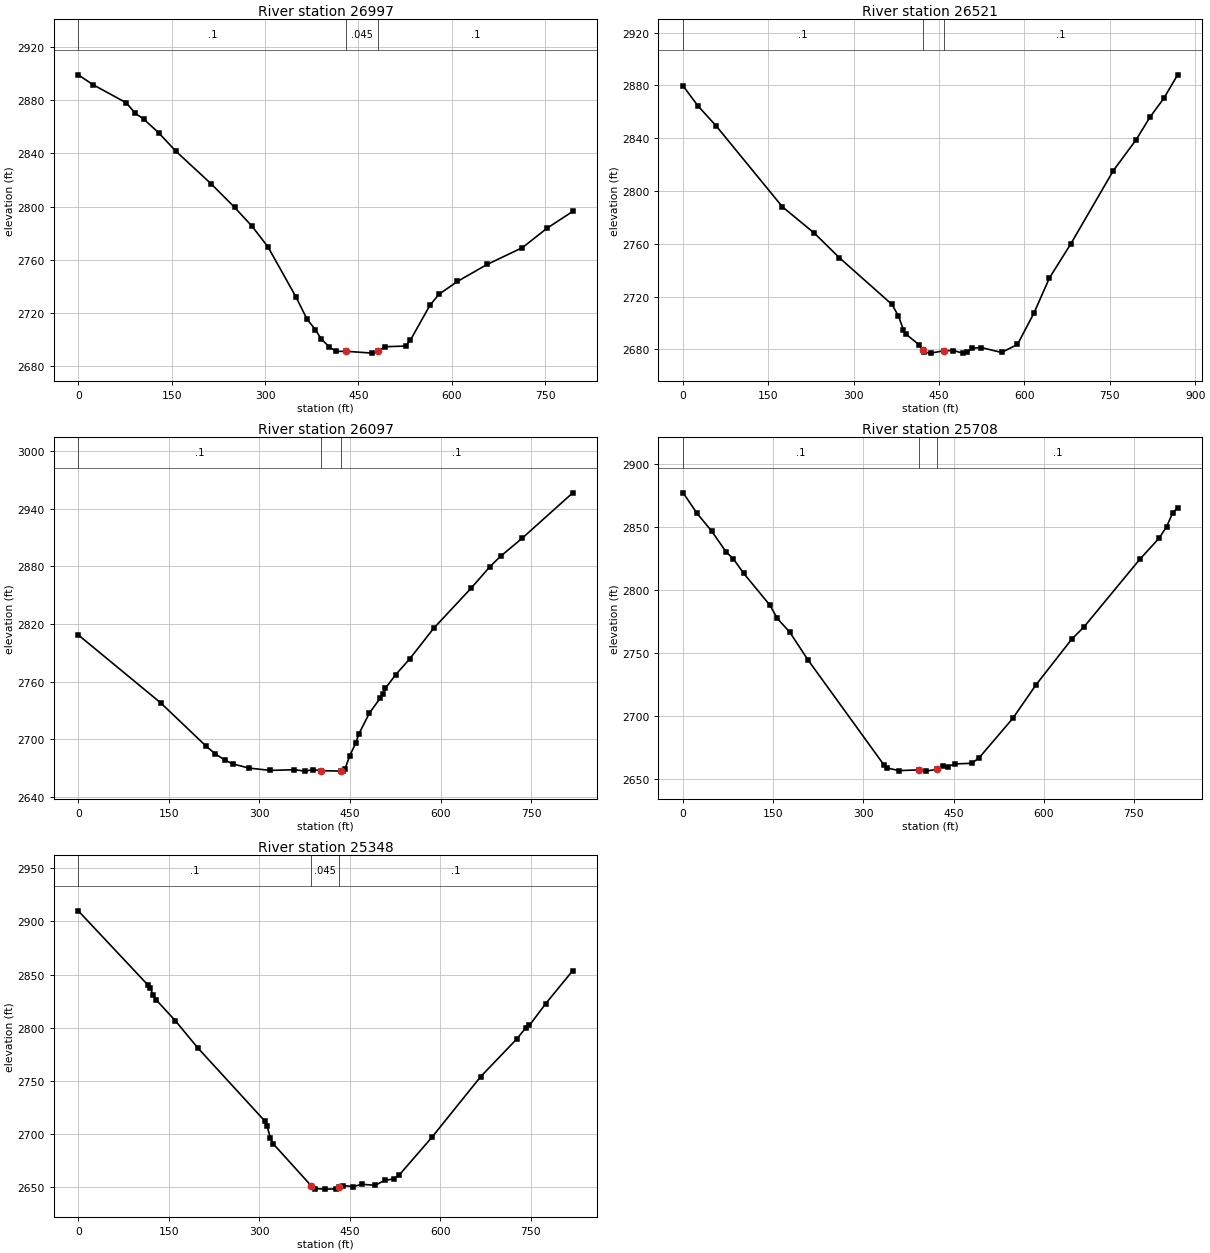
Type RM Length L Ch R = 1 ,26997   ,438.6,476.1,495
XS GIS Cut Line= 3
     2372989.307      597440.5842372838.61041663597196.578208317
2372386.08254906 596966.54496318
#Sta/Elev= 30
       0 2899.34    23.4 2891.98    77.2 2878.22    91.3 2870.43   104.8 2866.05
   128.9 2855.74   157.1 2841.59   213.6 2817.07   251.2 2799.35   279.4 2784.99
   304.6 2769.66   349.5 2732.01   367.4 2715.14   380.9 2707.14   389.8 2700.45
   403.3 2693.99   414.1 2690.76   430.7 2690.79   472.4 2689.42   481.3  2690.8
     493 2694.25   525.9 2694.75   533.4 2699.05   564.8 2725.41   579.5 2733.81
   609.2 2743.51   656.8 2756.31   713.4 2768.96   753.3 2783.71   794.4 2796.32
#Mann= 3 ,-1 , 0
       0      .1       0   430.7    .045       0   481.3      .1       0
Bank Sta=430.7,481.3
XS Rating Curve= 0 ,0
Exp/Cntr=0.3,0.1

Type RM Length L Ch R = 1 ,26521   ,420.3,424.2,432.4
XS GIS Cut Line= 2
2373026.40616947597428.8990126322373093.17292211596562.235038947
#Sta/Elev= 30
       0 2879.63    26.1 2864.49    58.2 2849.28   174.5 2788.03   230.7 2768.05
   274.8 2749.38   367.1 2714.03   378.4 2705.33   387.2 2694.87   391.2  2691.7
   415.2 2683.29     421  2679.4   423.4 2677.82   435.3 2677.18   459.4 2679.02
   475.2  2679.1   491.5 2677.15   499.5 2677.92   507.5 2680.77   523.4 2681.41
   559.7 2677.67   587.7 2683.71   616.8 2707.67   643.9 2734.16   681.4 2759.95
   756.2 2815.49   796.4 2838.97   820.4 2855.89   845.1  2870.4   869.2 2888.08
#Mann= 3 ,-1 , 0
       0      .1       0     421    .045       0   459.4      .1       0
Bank Sta=421,459.4
XS Rating Curve= 0 ,0
Exp/Cntr=0.3,0.1

Type RM Length L Ch R = 1 ,26097   ,393.7,388.9,384.6
XS GIS Cut Line= 3
     2373288.811      597401.922     2373465.444      597032.475
     2373642.076      596663.027
#Sta/Elev= 30
       0 2808.69   136.4 2737.97   211.7 2692.81     227 2684.75   242.8 2678.34
   255.7 2674.36   282.7 2669.97   318.1 2667.56   358.1 2668.27   375.4  2666.8
   389.1 2668.35     4022667.279   435.7 2666.84   438.7  2667.1   441.7 2668.86
   449.6 2682.86   459.7 2696.13   464.5 2705.28   482.2 2727.25   499.9 2742.65
   504.4 2747.14   508.8 2753.12   525.6 2767.18   548.7 2783.52   588.6 2815.54
   650.7 2857.38   681.9 2879.87   699.4 2890.56   734.9 2909.22     819 2956.69
#Mann= 3 ,-1 , 0
       0      .1       0     402    .045       0   435.7      .1       0
Bank Sta=402,435.7
XS Rating Curve= 0 ,0
Exp/Cntr=0.3,0.1

Type RM Length L Ch R = 1 ,25708   ,373.7,360.1,349.5
XS GIS Cut Line= 2
     2373766.727      597569.705     2373893.773      596756.587
#Sta/Elev= 30
       0 2877.02    23.1 2860.73    47.4 2846.71    71.7 2830.04    83.8 2824.47
   100.5 2813.32   144.5 2787.83   156.7 2777.38   177.6 2766.37   207.4 2744.71
   334.4    2661   339.2 2658.75   359.1 2656.64     392 2657.19   403.7 2656.22
   422.7 2657.64     432 2660.25   440.1 2659.76   452.2 2661.91   480.6 2662.45
   492.8 2666.89   548.7 2698.12   587.2 2724.64   646.7 2760.87   666.8 2770.45
   759.9 2824.22   792.3 2841.09   804.5 2850.04   814.8 2861.12     823 2865.08
#Mann= 3 ,-1 , 0
       0      .1       0     392    .045       0   422.7      .1       0
Bank Sta=392,422.7
XS Rating Curve= 0 ,0
Exp/Cntr=0.3,0.1

Type RM Length L Ch R = 1 ,25348   ,448.7,450,449.8
XS GIS Cut Line= 3
     2374367.259      597454.179      2374161.13      597100.146
      2373975.59      596734.904
#Sta/Elev= 30
       0    2910   114.9 2840.48   119.5  2837.3   124.1 2830.46   128.8  2826.4
   160.8  2806.6   198.2 2780.93   309.3 2712.06   312.9 2707.13   318.5 2695.96
   323.2 2690.69     386 2651.22   392.6  2648.6   409.4 2648.13   427.3 2648.35
   432.6 2649.89   439.2 2651.53   455.9 2650.46   469.4 2652.69   491.8 2651.75
   507.6 2656.28   522.5 2657.77   531.4 2661.17   586.1 2697.02   666.8 2754.02
   726.3 2789.27   741.7 2800.06   747.6 2802.26   774.5  2822.7   819.3 2853.72
#Mann= 3 ,-1 , 0
       0      .1       0     386    .045       0   432.6      .1       0
Bank Sta=386,432.6
XS Rating Curve= 0 ,0
Exp/Cntr=0.3,0.1