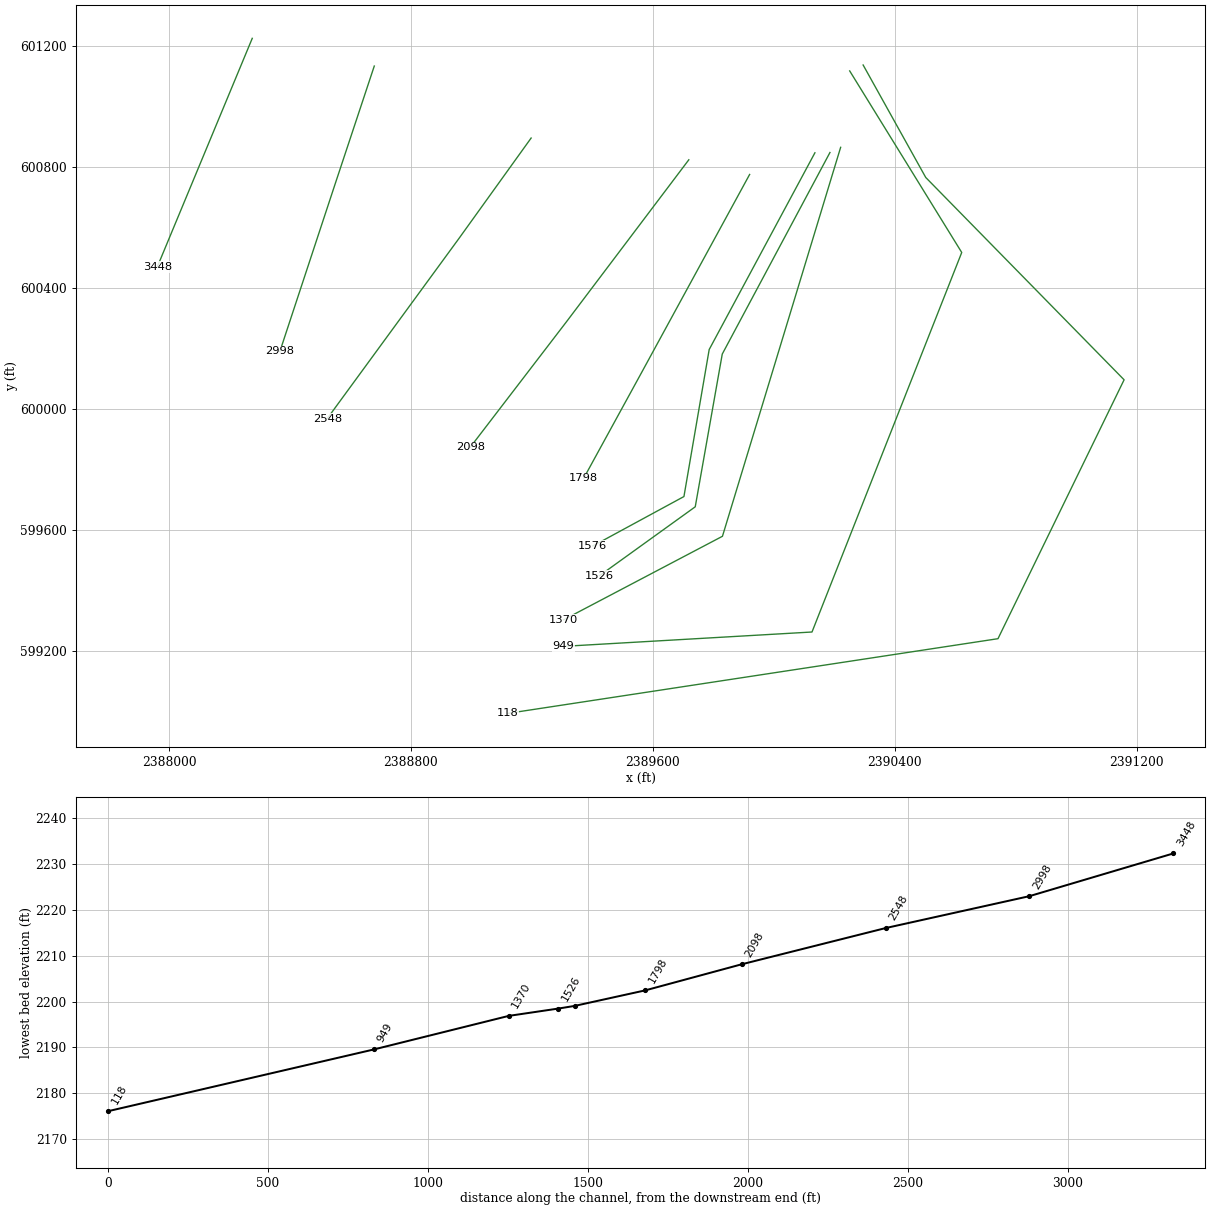
HEC-RAS study BIGRN.prj: BIGRN

--- BIGRN.g01 (geometry) --- (continued)

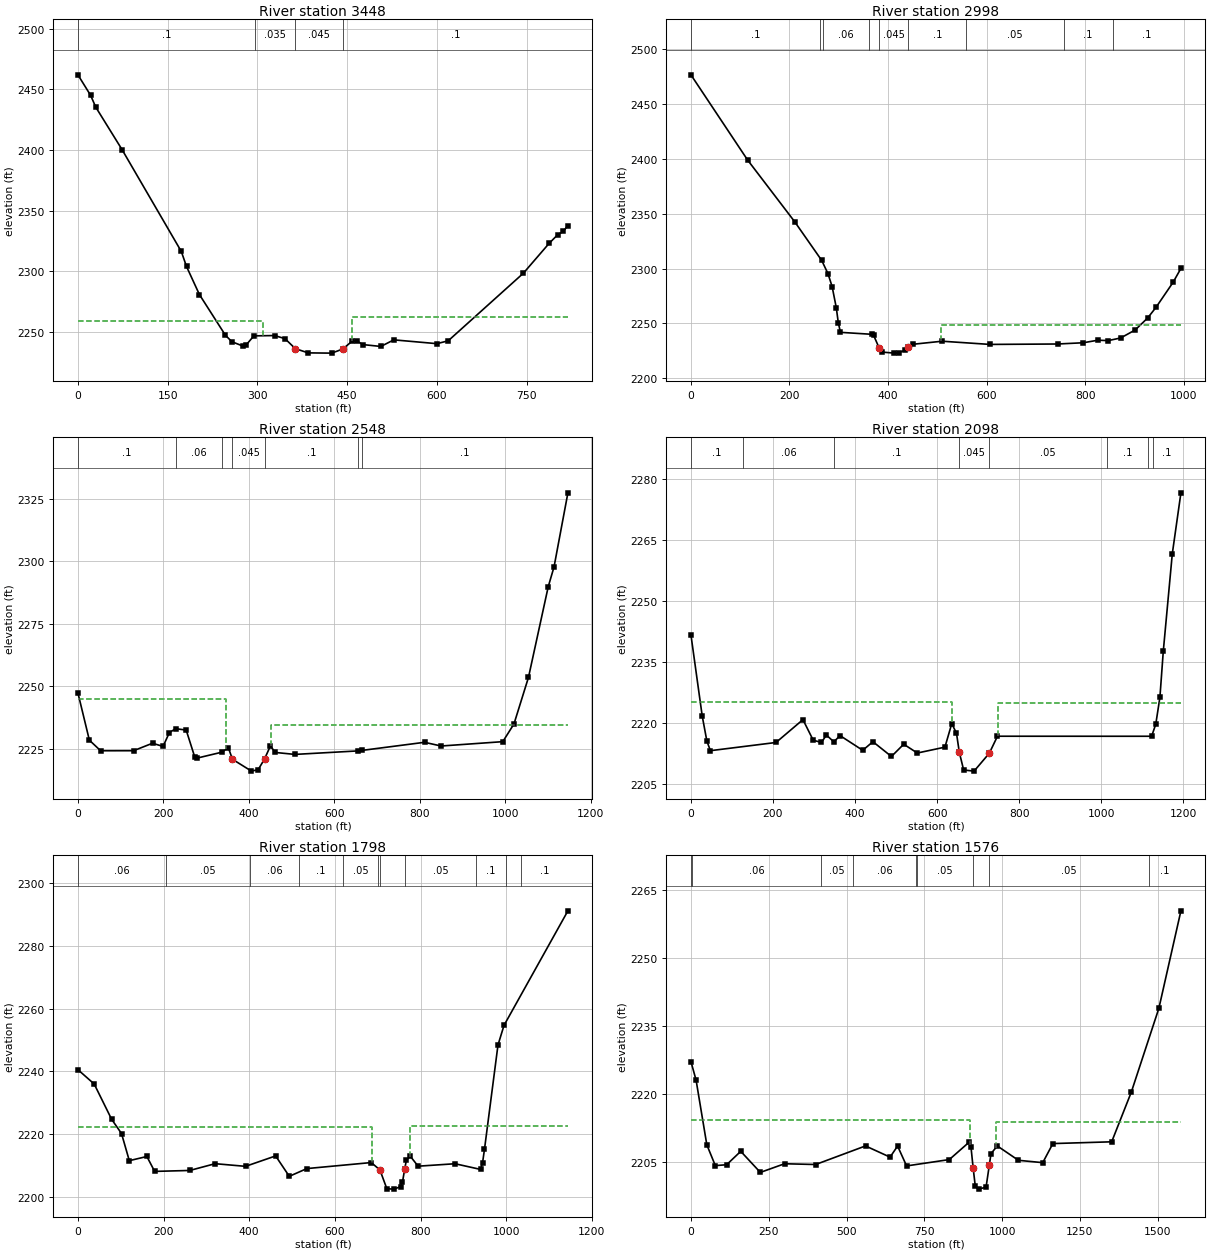
Type RM Length L Ch R = 1 ,3448    ,443.9,450.1,451.6
XS GIS Cut Line= 3
     2388275.454      601226.455     2388118.332      600848.298
     2387961.209      600470.141
#Sta/Elev= 30
       0 2461.97    21.2 2445.08    29.8 2435.32    73.7 2400.32   172.8 2316.22
   181.5 2303.82   203.1 2280.64   246.4  2247.2   257.2 2241.78   275.6 2238.19
   281.1 2239.03   294.1 2246.57   328.7 2246.83   346.1 2244.28   363.4 2236.01
     385 2232.53     424 2232.33   442.5 2235.64   458.7 2242.34   467.3 2242.13
     476 2239.39   506.3 2237.84     528 2243.28     600 2240.14   618.9 2242.49
   744.6 2298.29   787.9 2323.07     802 2330.05   811.1 2332.73     819 2337.59
#Mann= 4 ,-1 , 0
       0      .1       0  295.68    .035       0   363.4    .045       0
   442.5      .1       0
#XS Ineff= 2 , 0
          310.18 2259.18  458.87         2261.78
Permanent Ineff=
       F       F
Bank Sta=363.4,442.5
XS Rating Curve= 0 ,0
Exp/Cntr=0.3,0.1

Type RM Length L Ch R = 1 ,2998    ,462.9,449.7,440.9
XS GIS Cut Line= 3
     2388679.011      601134.804      2388550.15      600746.567
2388366.81645662600190.802301286
#Sta/Elev= 30
       0 2476.32   115.1 2398.72   210.6 2342.58   265.4 2307.39   278.1 2295.34
   286.5 2283.63   294.9 2264.52   299.1 2250.61   303.4 2241.92   366.6 2240.15
   370.8 2239.12   381.8 2227.88   387.6 2223.95   412.9    2223   421.4 2223.24
     434 2225.67   440.9 2228.48   450.8 2231.08   509.7 2233.84   606.7 2230.93
   744.1 2231.31   796.2 2232.44   825.7 2234.75   846.8  2234.4     872  2236.8
   901.5 2244.08   926.8 2254.99   943.8  2264.7   978.4 2287.45   994.3  2300.1
#Mann= 9 ,-1 , 0
       0      .1       0  262.26    .055       0  267.21     .06       0
  361.15      .1       0   381.8    .045       0   440.9      .1       0
  558.89     .05       0  756.62      .1       0  855.48      .1       0
#XS Ineff= 2 , 0
                          507.37         2248.15
Permanent Ineff=
       F       F
Bank Sta=381.8,440.9
XS Rating Curve= 0 ,0
Exp/Cntr=0.3,0.1

Type RM Length L Ch R = 1 ,2548    ,452.8,450,450.7
XS GIS Cut Line= 3
     2389197.781      600896.693     2388958.785      600564.171
2388523.58854459599969.043575073
#Sta/Elev= 30
       0 2247.33    26.8 2228.41    53.2 2224.18   130.3  2224.2   174.6 2227.19
   199.3 2225.91     214 2231.44   228.8 2233.02   253.4 2232.45   273.1 2221.85
   278.1 2221.21   337.2 2223.62     352 2225.43   361.7 2220.77   406.2 2216.03
   421.9 2216.63   436.7 2220.87   450.5 2226.11     462  2223.5   507.8 2222.72
   656.6 2224.13   663.8  2224.3   811.2 2227.56     850 2226.08   994.4 2227.82
  1020.6 2234.92  1054.5 2253.54  1100.8 2289.86  1114.3 2297.72  1146.8 2327.38
#Mann= 7 ,-1 , 0
       0      .1       0   228.8     .06       0   337.2      .1       0
   361.7    .045       0   436.7      .1       0   656.6     .05       0
   663.8      .1       0
#XS Ineff= 2 , 0
       0     347 2244.76  450.82       0 2234.55
Permanent Ineff=
       F       F
Bank Sta=361.7,436.7
XS Rating Curve= 0 ,0
Exp/Cntr=0.3,0.1

Type RM Length L Ch R = 1 ,2098    ,296.9,300.1,308.3
XS GIS Cut Line= 3
2389719.28830274600824.797298689     2389313.314      600287.306
2388996.59854983599874.241862878
#Sta/Elev= 30
       0 2241.72    27.5 2221.71    38.9 2215.51    47.5 2213.16   207.4 2215.18
     273 2220.81   298.1 2215.72   318.2  2215.2   330.2 2217.02   348.3 2215.32
   363.3 2216.88   418.7 2213.25   443.5 2215.37   488.6 2211.73   518.6 2214.75
   551.7 2212.58     619 2214.03   635.7 2219.84   647.2 2217.43   654.1 2212.74
   664.6  2208.4     690 2208.12   727.1 2212.52     747 2216.72  1122.7 2216.71
  1132.8 2219.68  1142.9 2226.29  1151.1 2237.63  1173.1 2261.69  1194.1  2276.7
#Mann= 8 ,-1 , 0
       0      .1       0  127.22     .06       0  348.61      .1       0
   654.1    .045       0   727.1     .05       0 1014.12      .1       0
 1113.56     .05       0 1125.25      .1       0
#XS Ineff= 2 , 0
           636.2 2225.23  749.18         2224.79
Permanent Ineff=
       F       F
Bank Sta=654.1,727.1
XS Rating Curve= 0 ,0
Exp/Cntr=0.3,0.1

Type RM Length L Ch R = 1 ,1798    ,216.5,221.7,232.6
XS GIS Cut Line= 3
2389920.42331974600776.244454517     2389568.624      600131.224
     2389371.949      599772.045
#Sta/Elev= 30
       0 2240.52      38 2235.95    78.7 2224.71   101.8 2220.17     120 2211.52
     161 2212.85   179.2  2208.1   261.2  2208.4   320.5 2210.56   391.4 2209.71
   461.7 2213.03   493.6 2206.53   534.6    2209     685 2210.92   705.2 2208.57
   721.4 2202.57   738.6 2202.45   753.3 2203.26   757.9 2204.68   762.9 2208.71
     767 2211.68   776.1 2212.94   794.4 2209.76   880.7 2210.54   940.3 2208.73
   944.9 2210.85   949.4 2215.16   980.9 2248.36     995 2254.64  1144.2 2291.14
#Mann= 11 ,-1 , 0
       0     .06       0  204.58     .05       0  401.88     .06       0
  515.51      .1       0  619.15     .05       0  700.92      .1       0
   705.2    .045       0   762.9     .05       0  930.19      .1       0
  998.73      .1       0 1033.89      .1       0
#XS Ineff= 2 , 0
          685.56 2222.26  774.41         2222.63
Permanent Ineff=
       F       F
Bank Sta=705.2,762.9
XS Rating Curve= 0 ,0
Exp/Cntr=0.5,0.3

Type RM Length L Ch R = 1 ,1576    ,47.8,50.5,47.8
XS GIS Cut Line= 4
2390136.34321897600847.9318184242389786.67373139600197.263334119
2389703.17308544599711.0157816622389401.94379498 599547.59651664
#Sta/Elev= 30
       0 2227.19    16.7 2223.05    51.1 2208.82    78.4 2204.23   114.7 2204.42
   160.1 2207.38   223.1 2202.73   300.9 2204.64   400.8 2204.47   561.1 2208.57
   639.9  2206.1   664.2 2208.54   693.1 2204.16   830.4 2205.56   893.1 2209.34
     900 2208.35   906.9 2203.77   913.9 2199.66   924.2 2199.04   948.5 2199.48
   958.9  2204.3   964.3 2206.86   984.6 2208.57  1052.4  2205.4  1130.7 2204.88
  1163.2 2209.09  1352.2 2209.48  1415.4 2220.47  1503.9 2238.95  1574.7 2260.44
#Mann= 9 ,-1 , 0
       0     .05       0    4.17     .06       0  418.37     .05       0
  521.23     .06       0  722.77      .1       0  728.06     .05       0
   906.9    .045       0   958.9     .05       0 1470.69      .1       0
#XS Ineff= 2 , 0
          897.46 2214.31  980.19         2213.82
Permanent Ineff=
       F       F
Bank Sta=906.9,958.9
XS Rating Curve= 0 ,0
Exp/Cntr=0.5,0.3

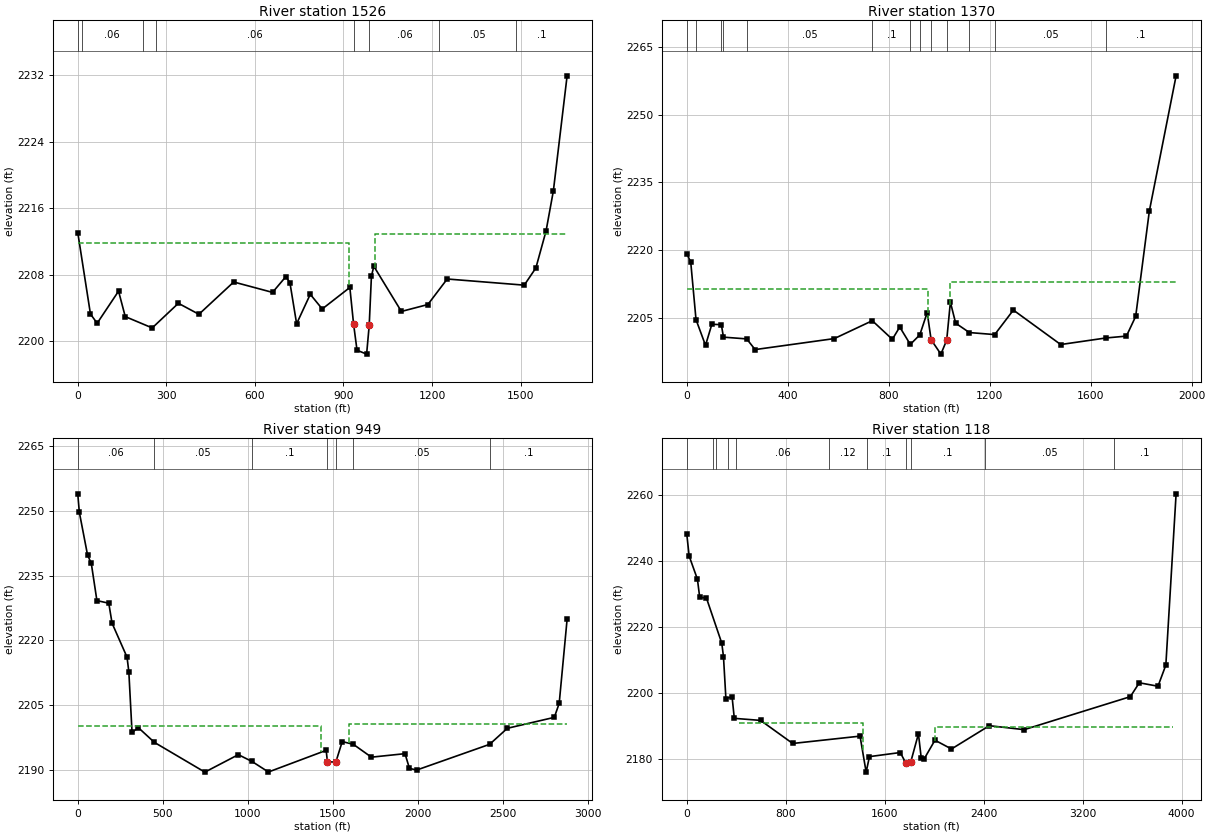
Type RM Length L Ch R = 1 ,1526    ,158.1,155,152.4
XS GIS Cut Line= 4
 2390186.0613382600848.8229404952389829.92291997600182.315553148
2389740.56658018599677.1272998172389424.88658828599449.808503945
#Sta/Elev= 30
       0 2213.08      43 2203.29    65.7 2202.18   138.2 2206.04   160.9 2202.98
   252.2 2201.62   340.8 2204.58   410.4 2203.26   528.3 2207.14   659.8 2205.89
   705.1 2207.79   718.8 2207.04   741.4 2202.12   787.6 2205.66   828.2  2203.9
   921.7 2206.48   934.42202.068     946 2198.94   978.5 2198.47   987.3 2201.92
   994.8 2207.84  1002.9 2209.03  1096.3  2203.6  1185.9 2204.43  1251.5  2207.5
  1512.5 2206.76  1551.9 2208.83  1586.4 2213.28  1611.1 2218.08  1657.7 2231.92
#Mann= 8 ,-1 , 0
       0     .05       0   13.19     .06       0  219.84     .05       0
  265.77     .06       0   934.4    .045       0   987.3     .06       0
  1225.3     .05       0 1484.73      .1       0
#XS Ineff= 2 , 0
          918.14 2211.82 1006.49         2212.95
Permanent Ineff=
       F       F
Bank Sta=934.4,987.3
XS Rating Curve= 0 ,0
Exp/Cntr=0.5,0.3

Type RM Length L Ch R = 1 ,1370    ,424.1,421.8,420.3
XS GIS Cut Line= 3
2390221.46433493600866.0067910752389830.55377226599579.603367448
 2389305.0367618599303.323619275
#Sta/Elev= 30
       0  2219.2    15.8 2217.29    36.7 2204.53    74.3 2198.82    99.4  2203.5
     137 2203.41   145.4 2200.64   237.4 2200.25   270.8 2197.88   584.4 2200.32
   734.9 2204.29   814.3 2200.16   843.6 2202.89   885.4 2199.03     923 2201.14
   952.3  2206.1   967.9 2200.06  1006.6 2196.87  1029.62199.978  1044.2 2208.42
  1065.1 2203.74  1119.5 2201.66  1219.7 2201.21  1293.6 2206.65  1481.1    2199
  1660.6 2200.46  1741.4 2200.87  1778.1 2205.25  1832.3 2228.67  1938.2 2258.67
#Mann= 13 ,-1 , 0
       0     .05       0    36.7     .06       0     137     .05       0
   145.4     .06       0   237.4     .05       0   734.9      .1       0
   885.4     .05       0     923      .1       0   967.9    .045       0
  1029.6     .05       0  1119.5     .06       0  1219.7     .05       0
  1660.6      .1       0
#XS Ineff= 2 , 0
          956.12 2211.43 1043.12          2212.9
Permanent Ineff=
       F       F
Bank Sta=967.9,1029.6
XS Rating Curve= 0 ,0
Exp/Cntr(USF)=0,0
Exp/Cntr=0.3,0.1

Type RM Length L Ch R = 1 ,949     ,629.5,830.9,624.6
XS GIS Cut Line= 4
2390251.38323153601118.6795906982390621.91549975600518.231061286
2390126.70502118599263.0068495622389303.51418574599215.483604756
#Sta/Elev= 30
       0 2253.92     9.2 2249.66    57.5 2239.79    79.7 2237.81   112.7 2229.22
   182.5 2228.62   201.9 2223.99     290 2216.13   300.6 2212.73   319.4 2198.75
     357 2199.81     451 2196.42   747.9 2189.54   944.9 2193.58  1025.5    2192
    1122 2189.57  1461.7 2194.58  1469.12191.954  1518.42191.847  1556.3 2196.61
    1622 2195.96  1727.9    2193  1925.5 2193.81  1951.9  2190.4  1994.9 2190.03
  2423.5 2195.97  2527.7 2199.68  2804.2 2202.21  2832.9 2205.45  2879.5 2224.92
#Mann= 7 ,-1 , 0
       0     .06       0     451     .05       0  1025.5      .1       0
  1469.1    .045       0  1518.4      .1       0    1622     .05       0
  2423.5      .1       0
#XS Ineff= 2 , 0
         1431.44 2200.19 1598.72         2200.78
Permanent Ineff=
       F       F
Bank Sta=1469.1,1518.4
XS Rating Curve= 0 ,0
Exp/Cntr=0.3,0.1

Type RM Length L Ch R = 1 ,118     ,,,
XS GIS Cut Line= 5
2390295.83811185601138.2670309672390502.87123724600766.306384887
2391158.89784304600097.1182800432390741.82780964599240.907408688
2389120.80459456598993.891817396
#Sta/Elev= 30
       0 2248.18    19.3 2241.44    86.3 2234.43   104.6 2228.97   159.5  2228.7
   283.1 2215.07   296.8 2211.02   316.4 2198.32   366.4 2198.85   384.3 2192.33
   596.9 2191.71   856.2 2184.73  1400.5 2186.95  1449.8 2176.06  1476.5 2180.75
  1725.7 2181.99  1770.2 2178.82  1810.4 2179.14  1872.5 2187.66  1894.8 2180.39
  1918.1 2180.02    2006 2185.72  2139.5 2183.06  2445.4 2190.11    2727 2188.91
  3584.8 2198.89  3657.6 2203.09  3808.4 2202.05    3872 2208.45  3954.9 2260.26
#Mann= 11 ,-1 , 0
       0     .06       0  212.17     .05       0  235.87     .06       0
  335.48     .05       0  398.95     .06       0 1150.73     .12       0
 1456.91      .1       0  1770.2    .045       0  1810.4      .1       0
 2412.18     .05       0 3455.73      .1       0
#XS Ineff= 2 ,-1
   421.1  1421.12190.798 2003.51 3932.472189.731
Permanent Ineff=
       F       F
Bank Sta=1770.2,1810.4
XS Rating Curve= 0 ,0
Exp/Cntr=0.3,0.1
LCMann Table=0

Chan Stop Cuts=-1
Use User Specified Reach Order=0
Composite Channel Slope=5

--- BIGRN.g02 (geometry) ---

Geom Title=Geometry_backup
Program Version=5.07

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
River Reach=BIGRN           ,Main
Reach XY= 30
2379496.59970866622879.461536355     2378615.191      620578.786
     2377406.934      619770.554     2377796.478      618673.518
      2376330.16      615176.987     2375290.982       614339.64
     2375425.978      612730.954     2374134.081      612184.411
     2374448.233      610661.253      2373559.54      610628.175
     2373778.853      609596.567     2372547.601      608760.622
     2373361.498      607801.624     2372215.106      607316.848
      2372701.18      605659.784     2371748.415      605101.796
     2372084.786      603661.704     2370573.527      601861.373
     2371347.092      599230.685      2372857.45      596932.263
     2376651.505      596891.343     2378265.513      594369.079
     2380179.192      594860.855     2381356.236      593630.805
     2383894.369      594919.318     2383652.281      596949.241
     2384927.342      597331.008     2385273.116      599295.808
     2387563.193      600894.536     2391054.011      599607.638

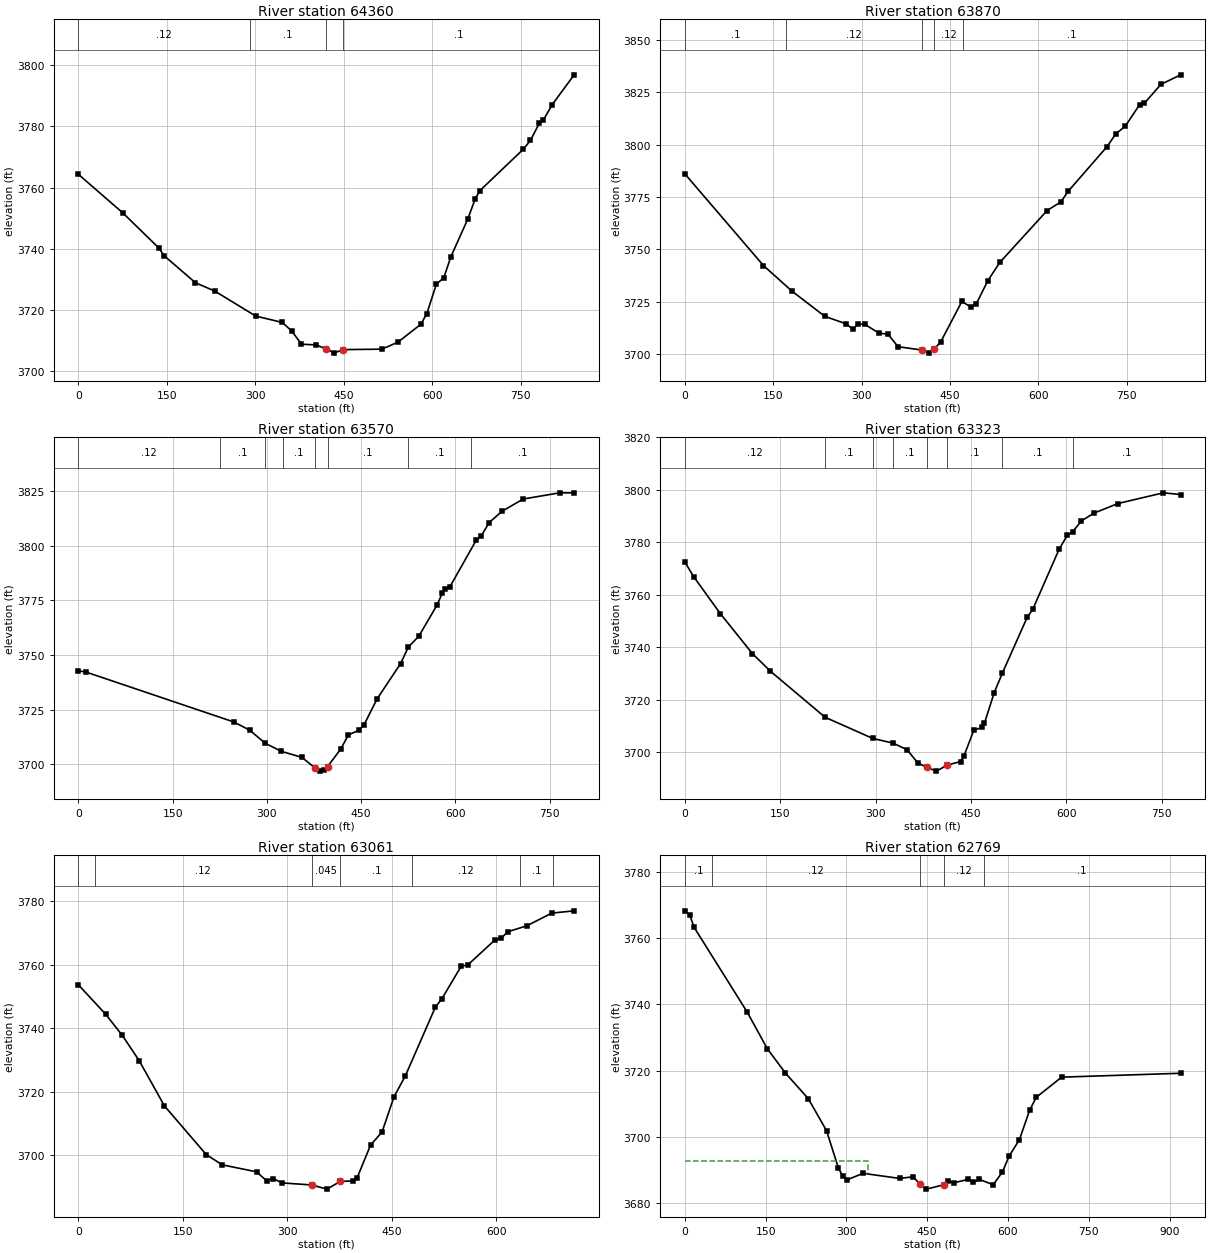
Type RM Length L Ch R = 1 ,64360   ,490.1,490.1,490.1
XS GIS Cut Line= 2
 2379961.1624795622775.866377598     2379138.232      622948.161
#Sta/Elev= 30
       0 3764.34    75.6 3751.68   136.4 3740.25   145.5  3737.7   198.6 3728.87
   231.3 3726.15   300.8 3717.97   345.8 3715.89   362.1 3713.05   378.4 3708.77
   403.3 3708.53   420.73707.206   433.8 3705.85     448 3706.99   514.9 3707.15
   541.8 3709.42   580.8 3715.28     591 3718.79   607.3 3728.49   619.6 3730.43
   631.8 3737.39   660.2 3749.59   672.7 3756.14   680.4 3758.89   754.8 3772.57
   766.7 3775.41   781.8 3781.07   788.6 3782.08   803.5 3787.08   840.8 3796.86
#Mann= 4 ,-1 , 0
       0     .12       0  291.05      .1       0   420.7    .045       0
     448      .1       0
Bank Sta=420.7,448
XS Rating Curve= 0 ,0
Exp/Cntr=0.3,0.1

Type RM Length L Ch R = 1 ,63870   ,301.1,300,296.3
XS GIS Cut Line= 3
     2379891.978      622457.902     2379482.792      622484.259
2379053.30643252622528.979803514
#Sta/Elev= 30
       0 3786.05   133.5 3742.25   181.6  3730.1   237.7 3717.99   273.8 3714.42
   285.8 3711.78   293.8 3714.34   305.9 3714.11   329.9 3709.93   344.8 3709.52
     362 3703.51   402.53701.895   414.1 3700.43   423.4  3702.4   434.2 3705.65
   470.4 3725.09   485.3 3722.52   494.5 3723.73   514.6 3735.09   534.8 3743.72
   615.2 3768.52   638.3 3772.58   651.4 3777.86   716.9 3799.02   731.8 3805.14
   747.9 3808.78     772 3818.97   780.1 3819.66   808.2 3828.69   841.8 3833.29
#Mann= 5 ,-1 , 0
       0      .1       0  172.57     .12       0   402.5    .045       0
   423.4     .12       0  471.73      .1       0
Bank Sta=402.5,423.4
XS Rating Curve= 0 ,0
Exp/Cntr=0.3,0.1

Type RM Length L Ch R = 1 ,63570   ,246.1,247.2,245.2
XS GIS Cut Line= 3
2379697.81248776622174.321905213     2379327.754      622273.688
     2378936.253       622379.81
#Sta/Elev= 30
       0 3742.71    11.5 3742.24   247.5 3719.28   272.4 3715.58   297.2 3709.57
   322.9 3705.84   355.6  3703.1   376.23698.324   384.2 3696.77   391.5 3697.34
   396.6 3698.86   417.4 3706.88   429.8 3713.43   446.4 3715.48   454.7  3718.1
   475.4 3729.92   512.7 3746.06   525.1 3753.67   541.5 3758.52   570.7 3772.88
     579 3778.35   583.1 3780.02   591.4 3781.37   632.8  3802.5   641.2 3804.64
   653.6 3810.69   674.3 3815.89   707.8 3821.47   765.5 3824.28   788.8  3824.3
#Mann= 8 ,-1 , 0
       0     .12       0  225.29      .1       0   297.2      .1       0
  325.12      .1       0   376.2    .045       0   396.6      .1       0
  524.83      .1       0  624.68      .1       0
Bank Sta=376.2,396.6
XS Rating Curve= 0 ,0
Exp/Cntr=0.3,0.1

Type RM Length L Ch R = 1 ,63323   ,213.5,202.8,184.2
XS GIS Cut Line= 2
2379623.97533879 621925.341129482378880.74968476622160.818564421
#Sta/Elev= 30
       0 3772.48    13.9  3766.9    55.8 3752.81   106.2 3737.58   134.6 3730.85
   220.6 3713.29   295.4 3705.23   327.2 3703.45   349.5 3700.92   366.3 3695.91
   380.73694.176   395.7 3692.76   412.9 3695.08   433.5 3696.41   438.8 3698.47
   454.5  3708.4   467.4  3709.4   471.2 3711.04   486.5 3722.71   499.3  3730.1
   538.4 3751.41   547.1 3754.41   588.7 3777.41   601.3 3782.57   609.7 3783.98
   623.6 3788.11   643.3 3791.09     681 3794.75   752.4 3798.83   779.6 3798.18
#Mann= 8 ,-1 , 0
       0     .12       0   220.6      .1       0   295.4      .1       0
   327.2      .1       0   380.7    .045       0   412.9      .1       0
   499.3      .1       0   609.7      .1       0
Bank Sta=380.7,412.9
XS Rating Curve= 0 ,0
Exp/Cntr(USF)=0,0
Exp/Cntr=0.3,0.1

Type RM Length L Ch R = 1 ,63061   ,280.8,291.6,281.7
XS GIS Cut Line= 2
2379415.21819043621647.7999380152378823.95648704622044.688264336
#Sta/Elev= 30
       0 3753.74    39.1 3744.48      63 3737.83    87.3 3729.86   123.6 3715.58
   183.6 3700.25   206.5    3697   255.9 3694.79   270.4 3691.97     280 3692.67
   292.6  3691.3   335.13690.652   357.1 3689.34   376.43691.796   394.6  3691.9
   400.4 3692.91   419.7 3703.21   436.2 3707.35   453.4 3718.46   469.6    3725
   512.8 3746.69   522.3 3749.39   549.8 3759.55   559.4 3759.99     598  3767.8
   607.6 3768.51   617.2 3770.46   644.3 3772.33   679.9 3776.31   712.1 3777.03
#Mann= 7 ,-1 , 0
       0      .1       0   23.41     .12       0   335.1    .045       0
   376.4      .1       0  479.37     .12       0  634.45      .1       0
  681.01     .12       0
Bank Sta=335.1,376.4
XS Rating Curve= 0 ,0
Exp/Cntr=0.3,0.1

Type RM Length L Ch R = 1 ,62769   ,354.4,364.7,359.3
XS GIS Cut Line= 2
2379415.20795526621519.8711069512378546.20949983621823.736112202
#Sta/Elev= 30
       0 3768.22       9 3767.04    17.4 3763.21   115.8 3737.69   153.4 3726.57
   186.9 3719.27   229.3 3711.56   263.2 3701.89   285.3 3690.58   292.9 3688.29
   301.4 3687.08     331 3689.04   398.8  3687.5   424.2 3687.99     436 3685.85
   448.6 3684.27   481.8 3685.63   487.8 3686.64   500.5  3686.2   525.9 3687.22
   534.4 3686.29   547.1 3687.19   572.6 3685.59   589.5 3689.37   602.2 3694.23
   621.4 3699.22   640.1 3708.02   652.6 3711.97   699.7 3718.05   920.6 3719.22
#Mann= 5 ,-1 , 0
       0      .1       0   50.71     .12       0     436    .045       0
   481.8     .12       0  555.06      .1       0
#XS Ineff= 2 , 0
          339.93 3692.69
Permanent Ineff=
       F       F
Bank Sta=436,481.8
XS Rating Curve= 0 ,0
Exp/Cntr=0.3,0.1

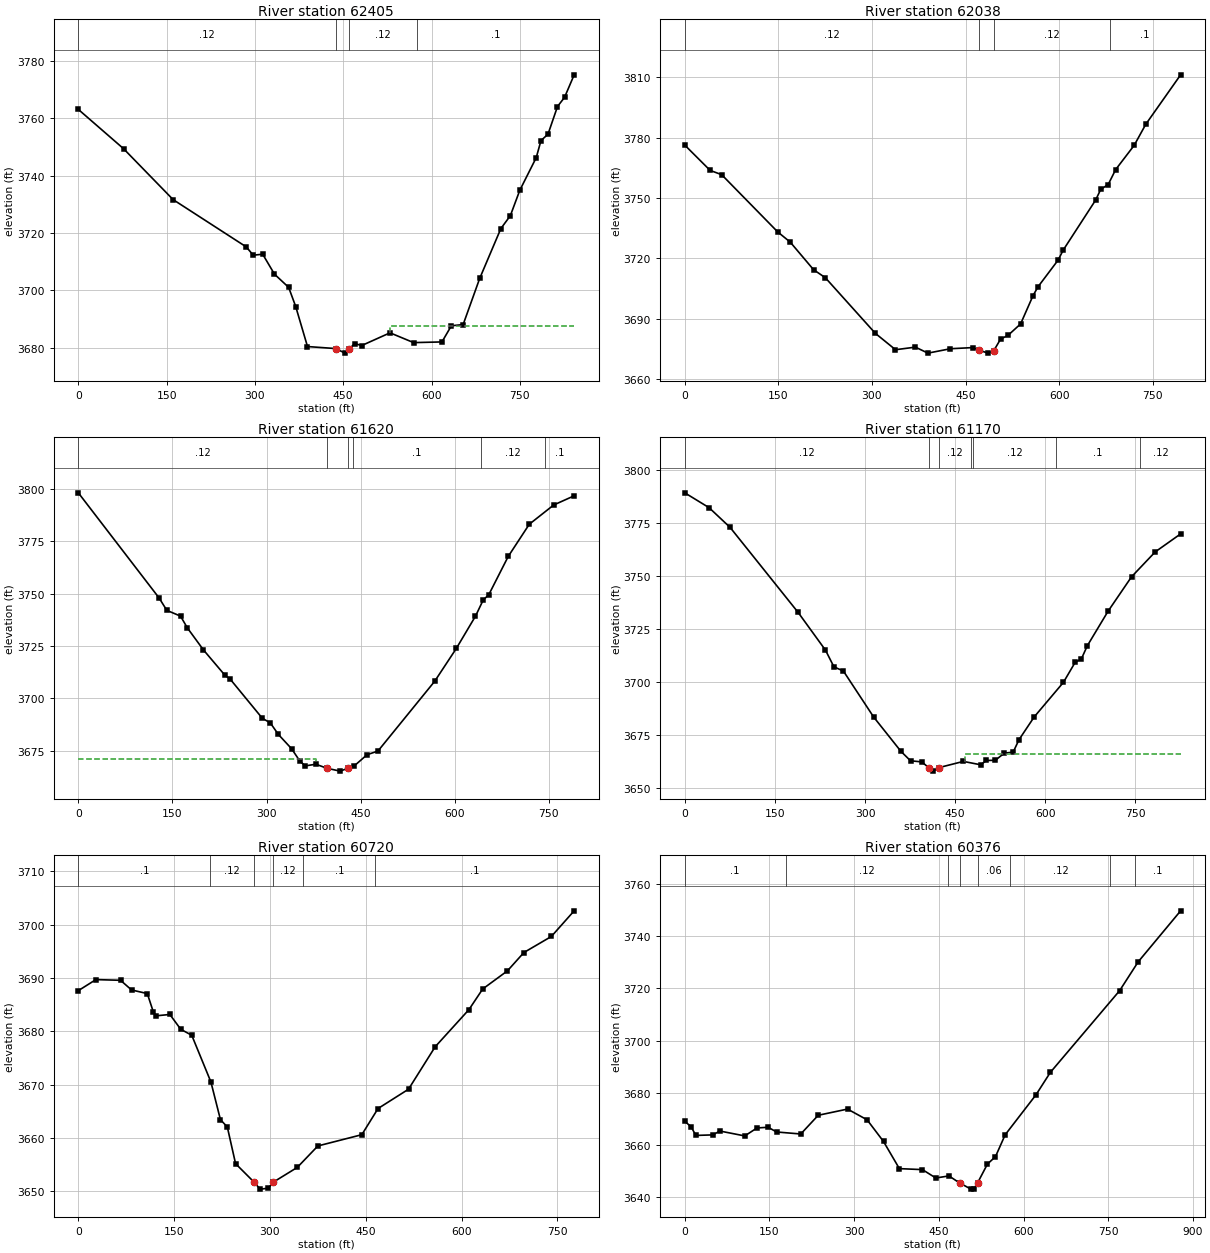
Type RM Length L Ch R = 1 ,62405   ,361.3,367.2,363.9
XS GIS Cut Line= 2
2379315.46727816621370.2826728752378474.43951127621416.839725742
#Sta/Elev= 30
       0 3763.13    76.8 3749.42     161 3731.64   285.2 3715.14   297.2 3712.23
   313.2 3712.58   333.2 3705.61   357.3    3701   369.3 3694.29   389.3 3680.34
   437.4 3679.63     453 3678.04   460.6 3679.59   469.4 3681.36   481.5  3680.7
   529.5 3685.13   569.6 3681.71   617.7 3681.95   633.7 3687.59   653.7 3688.01
   681.8 3704.11   717.8 3721.54   733.9 3726.03   749.9 3734.87   777.9 3746.31
   785.9 3752.23   797.9  3754.5     814 3764.15     826 3767.35   842.3 3775.21
#Mann= 4 ,-1 , 0
       0     .12       0   437.4    .045       0   460.6     .12       0
  574.51      .1       0
#XS Ineff= 2 , 0
                          529.07         3687.64
Permanent Ineff=
       F       F
Bank Sta=437.4,460.6
XS Rating Curve= 0 ,0
Exp/Cntr=0.3,0.1

Type RM Length L Ch R = 1 ,62038   ,417.3,417.1,407.2
XS GIS Cut Line= 2
2379179.17714538621099.7198261172378387.00976317621163.324506441
#Sta/Elev= 30
       0 3776.31    40.6 3763.73    59.1  3761.6   148.9 3733.12     169 3728.03
   206.4  3714.3   225.2 3710.33   305.4 3682.63   337.7 3674.48   369.6 3675.76
   389.7 3672.78   425.8 3674.97   461.9 3675.54   471.4 3674.24     486  3672.8
   495.43674.081   506.1 3679.75   518.1 3681.64   538.2 3687.31   558.2 3701.43
   566.2 3705.83   598.4 3719.11   606.4 3724.02   658.5 3748.97   666.6 3754.27
   678.6  3756.7   690.6 3764.15   720.3 3776.22   738.8 3786.66   794.7  3811.3
#Mann= 4 ,-1 , 0
       0     .12       0   471.4    .045       0   495.4     .12       0
  680.95      .1       0
Bank Sta=471.4,495.4
XS Rating Curve= 0 ,0
Exp/Cntr(USF)=0,0
Exp/Cntr=0.3,0.1

Type RM Length L Ch R = 1 ,61620   ,454.9,450,440.7
XS GIS Cut Line= 3
     2379045.575      620592.156     2378663.985      620734.439
2378308.45531277620877.210599747
#Sta/Elev= 30
       0 3798.11   128.7 3747.96   141.1 3742.03   162.9 3739.29   173.8 3733.66
   199.4 3723.18   233.5 3711.14   242.1 3709.21   293.3 3690.55     306 3688.35
   318.9 3682.82   339.9 3676.04   353.1 3670.15   361.6 3667.83   378.7 3668.62
   396.1 3666.72   417.2 3665.33   430.3 3666.73   438.8 3667.55   460.3 3673.17
   477.6  3674.9   568.1 3708.21   602.6 3723.88   633.1 3739.26   645.4 3746.97
   654.3  3749.5   685.3 3767.76   718.9 3783.13   757.7 3792.29   790.4 3796.69
#Mann= 6 ,-1 , 0
       0     .12       0   396.1    .045       0   430.3     .12       0
  438.03      .1       0  641.62     .12       0  743.42      .1       0
#XS Ineff= 2 , 0
          378.31 3671.21
Permanent Ineff=
       F       F
Bank Sta=396.1,430.3
XS Rating Curve= 0 ,0
Exp/Cntr=0.3,0.1

Type RM Length L Ch R = 1 ,61170   ,450.4,450,447.2
XS GIS Cut Line= 3
     2378639.925      620032.367     2378421.017      620382.689
     2378180.502      620717.215
#Sta/Elev= 30
       0 3789.41    40.4  3782.4    75.3 3773.11   188.5 3732.99   234.1 3715.14
   248.2 3707.25   263.9 3705.29   314.3 3683.56   359.7 3667.36   375.6 3662.92
   394.5 3662.38   405.63659.719   413.1 3658.03   423.2 3659.71   463.6 3662.62
   492.2 3661.03     502 3663.05   516.8 3663.16   531.6 3666.51   546.4    3667
   556.2 3672.89   581.4 3683.61   630.1 3699.95   649.8 3709.49   659.7 3710.86
   669.9 3717.25   704.3 3733.49   743.4 3749.76   782.8 3761.52   825.1 3770.02
#Mann= 7 ,-1 , 0
       0     .12       0   405.6    .045       0   423.2     .12       0
  476.99      .1       0  480.36     .12       0  617.64      .1       0
  758.28     .12       0
#XS Ineff= 2 , 0
                          465.69         3666.22
Permanent Ineff=
       F       F
Bank Sta=405.6,423.2
XS Rating Curve= 0 ,0
Exp/Cntr=0.3,0.1

Type RM Length L Ch R = 1 ,60720   ,326.2,344.5,345.6
XS GIS Cut Line= 3
2378112.62683839619973.186157707     2378009.757      620240.182
 2377829.4003197620696.081101321
#Sta/Elev= 30
       0 3687.61    27.5 3689.68    66.1 3689.55    83.3 3687.74     108 3687.06
   117.6 3683.56   121.9 3682.89   143.3 3683.14   160.4 3680.36   177.6 3679.24
   207.6 3670.48   222.5 3663.42   233.3 3662.03   246.2 3655.16   275.1  3651.7
   284.7 3650.38   297.6 3650.55   305.2 3651.68   342.9 3654.46   375.1 3658.48
   443.9 3660.59   469.3  3665.5     517 3669.12   558.7 3677.07   611.7 3684.06
   633.2 3687.92   671.9 3691.32   697.7 3694.76   740.7 3697.77   776.4 3702.58
#Mann= 6 ,-1 , 0
       0      .1       0  206.66     .12       0   275.1    .045       0
   305.2     .12       0  352.06      .1       0  465.16      .1       0
Bank Sta=275.1,305.2
XS Rating Curve= 0 ,0
Exp/Cntr=0.3,0.1

Type RM Length L Ch R = 1 ,60376   ,402.1,405.5,405.4
XS GIS Cut Line= 3
     2377977.519      619824.7682377846.76171598620139.675633672
2377406.17783839620446.843142985
#Sta/Elev= 30
       0 3669.07      11 3667.05    19.6 3663.69    49.9  3663.9    61.9 3665.38
   106.2  3663.5   127.9 3666.55   147.6 3666.81   162.5 3665.01   205.4 3664.24
   236.3  3671.4   288.2 3673.77   322.8 3669.67   351.9 3661.38     380 3650.99
   420.9 3650.61   444.5 3647.41   467.8  3648.2   486.5 3645.54   506.8 3643.15
   511.7  3643.2   518.6 3645.57     536 3652.75   550.2 3655.57   567.4 3663.95
     622 3679.24   647.3 3687.78   770.1 3719.07     803 3730.11   878.1  3749.6
#Mann= 8 ,-1 , 0
       0      .1       0  178.42     .12       0  466.44     .06       0
   486.5    .045       0   518.6     .06       0  576.64     .12       0
  753.65      .1       0  797.03      .1       0
Bank Sta=486.5,518.6
XS Rating Curve= 0 ,0
Exp/Cntr=0.3,0.1

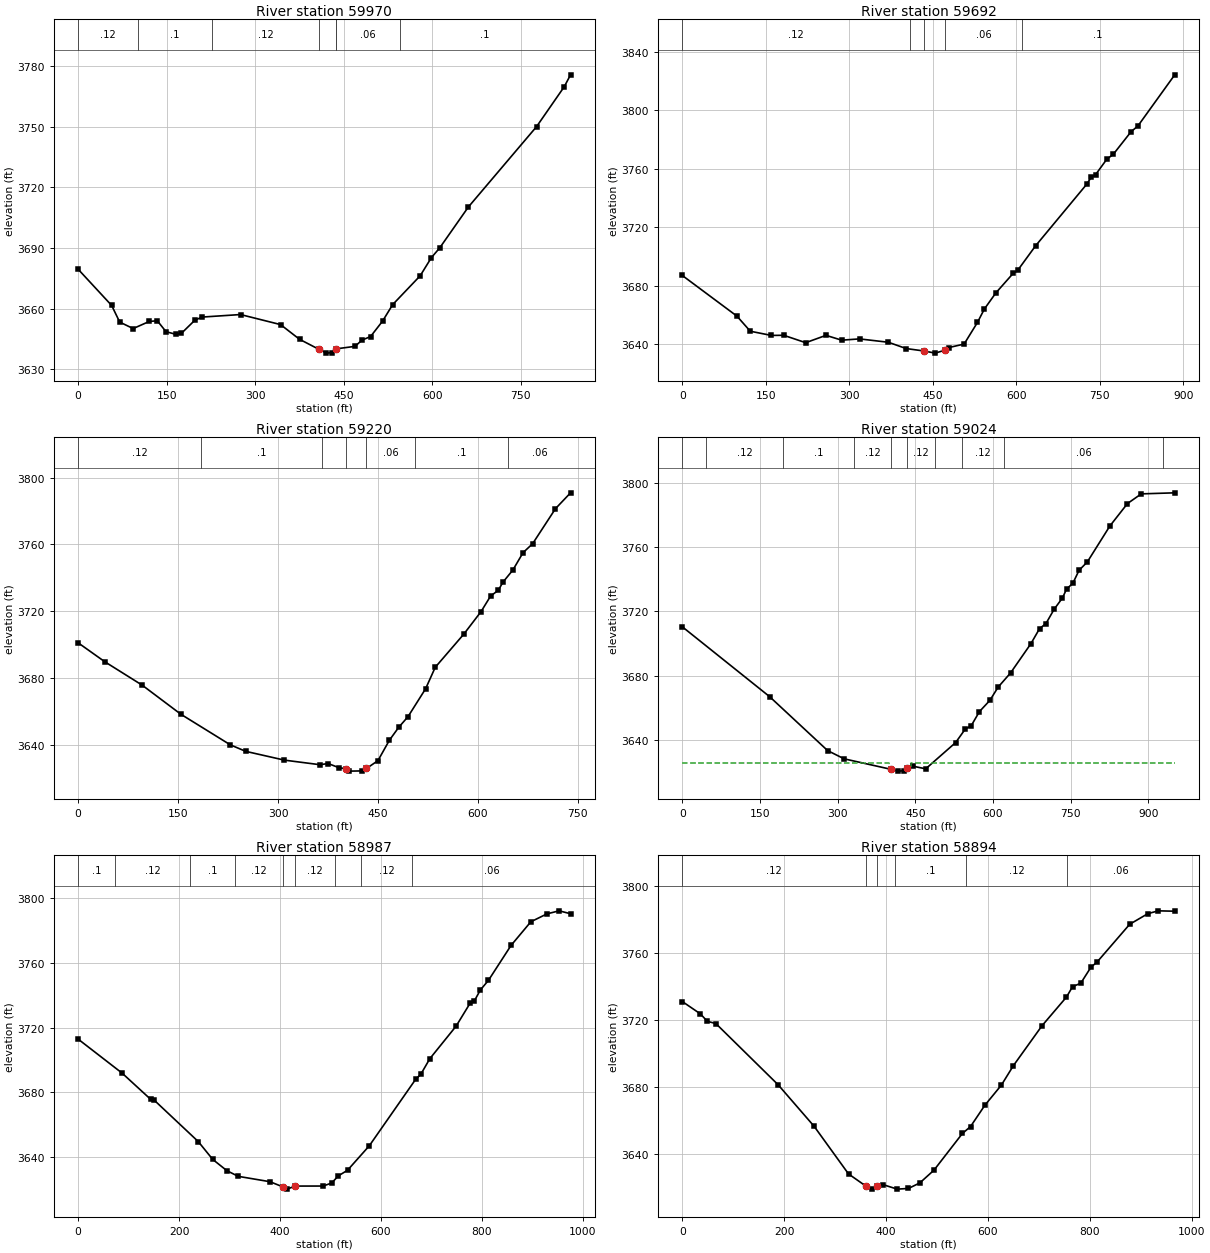
Type RM Length L Ch R = 1 ,59970   ,268.5,278.5,285.4
XS GIS Cut Line= 3
     2377876.704      619692.066     2377503.841      619893.632
2377153.59997942620107.897026433
#Sta/Elev= 30
       0 3679.48    56.8 3661.57    70.4 3653.36    93.2 3650.16   120.5 3653.67
   134.1 3654.02   148.9 3648.61   165.9 3647.29     175  3647.8   197.8  3654.3
   210.1 3655.84   275.1 3657.09     343 3652.12   375.1 3644.86   407.9 3639.91
   420.6 3638.01   429.8 3638.28   437.2 3640.13   469.2 3641.36   480.8 3644.42
   495.5 3646.21   515.8 3653.82     533 3662.01   579.6 3676.26   598.6 3685.25
   612.7 3690.05   661.2 3710.26   776.8 3750.01   823.7 3769.75   834.4 3775.63
#Mann= 7 ,-1 , 0
       0     .12       0  100.71      .1       0  226.88     .12       0
   407.9    .045       0   437.2     .12       0  437.47     .06       0
  544.77      .1       0
Bank Sta=407.9,437.2
XS Rating Curve= 0 ,0
Exp/Cntr=0.3,0.1

Type RM Length L Ch R = 1 ,59692   ,456.6,471.5,479
XS GIS Cut Line= 3
2377860.80923474619635.1902781622377414.29223474619651.760278162
2376976.53320013619667.855713027
#Sta/Elev= 30
       0 3686.88    98.1  3659.1   122.1 3648.77   159.9  3645.9   182.2 3645.99
   221.7 3640.93   258.2 3645.95   286.3 3642.65   318.4 3643.52   370.3 3641.22
   402.3 3636.91   434.8 3635.23   454.4 3633.79   472.2 3635.84   478.4 3637.56
   506.4 3639.98   530.4 3654.81   542.8 3663.96   563.6 3675.05   594.5 3688.33
   602.5 3690.31   634.7 3707.12   726.6 3749.24   734.6 3753.95   742.6 3755.81
   762.6  3766.3   774.6 3769.83   806.6 3785.29   818.6 3789.08   884.9 3824.12
#Mann= 5 ,-1 , 0
       0     .12       0  409.46     .06       0   434.8    .045       0
   472.2     .06       0  609.64      .1       0
Bank Sta=434.8,472.2
XS Rating Curve= 0 ,0
Exp/Cntr=0.3,0.1

Type RM Length L Ch R = 1 ,59220   ,184.4,196.3,203.2
XS GIS Cut Line= 3
     2377889.802      619457.541     2377542.235      619218.572
2377284.38480194619033.770356893
#Sta/Elev= 30
       0 3701.18      40 3689.86    96.2 3675.83   154.2 3658.46   228.5 3640.14
   251.5 3636.28   309.5 3631.03   362.9 3628.29   375.2 3628.99     392 3626.41
   401.8 3625.99   407.1 3624.45   426.1 3624.58   432.7 3626.03   449.9  3630.7
   467.1 3642.92   481.4  3650.8     495 3656.99   521.5 3673.74   535.9 3686.53
   578.9 3706.43   604.7 3719.87     619 3729.15   630.5 3732.58   637.7 3737.54
   652.5 3744.75   667.7  3755.1   682.1 3760.47   716.4 3781.43     739 3790.89
#Mann= 7 ,-1 , 0
       0     .12       0  184.55      .1       0  366.33     .06       0
   401.8    .045       0   432.7     .06       0  505.33      .1       0
  645.39     .06       0
Bank Sta=401.8,432.7
XS Rating Curve= 0 ,0
Exp/Cntr=0.5,0.3

Type RM Length L Ch R = 1 ,59024   ,39,37.4,37.3
XS GIS Cut Line= 4
2377942.87159607619382.0866732192377720.52236004619206.111655017
2377636.57337682618976.5211560742377214.23984152618950.644614837
#Sta/Elev= 30
       0 3710.39   168.5 3667.02   280.7 3633.45   312.5 3628.35   402.8 3621.84
   416.9  3620.7   427.8 3620.93   433.7 3622.43   444.6 3623.82   470.1 3622.13
     528 3638.49   546.4 3646.81   557.9 3648.88   573.9 3657.72     594 3664.66
     610 3672.92     634 3681.74   673.4 3699.97   690.1 3709.33   702.2 3712.34
   718.2 3721.33   734.2 3728.33   742.2 3733.86   754.3 3737.45   766.3 3745.53
   782.3 3750.73   825.8 3773.05   859.8 3787.01   886.5 3793.03   951.1 3793.68
#Mann= 10 ,-1 , 0
       0      .1       0   46.33     .12       0  193.54      .1       0
  331.78     .12       0   402.8    .045       0   433.7     .12       0
  488.05      .1       0  540.14     .12       0  622.11     .06       0
  927.56     .12       0
#XS Ineff= 2 , 0
             400    3626     442            3626
Permanent Ineff=
       F       F
Bank Sta=402.8,433.7
XS Rating Curve= 0 ,0
Exp/Cntr=0.5,0.3

Type RM Length L Ch R = 1 ,58987   ,97.4,93,85.5
XS GIS Cut Line= 4
2377958.34006662619365.7623006962377750.87850456619198.384822519
2377665.84304834 618945.16237363 2377224.0783027618932.399345987
#Sta/Elev= 30
       0 3712.96    86.9    3692   143.4 3675.83   151.1 3675.11   237.9 3649.66
   266.6 3638.63   294.7 3631.65   317.2 3628.15     380 3624.84   405.2  3621.7
   413.7 3620.25   430.3 3622.14   485.4 3622.16   502.3 3624.04   515.8 3628.51
   533.7 3631.92   576.8 3647.02   668.8 3688.17   678.8 3691.18   696.8 3700.88
   748.9 3721.02   776.9 3735.33   784.9 3736.51   796.9 3743.34   812.9 3749.28
   857.8 3770.93   896.9 3785.49   928.9  3790.4     953 3792.27   975.6 3790.47
#Mann= 9 ,-1 , 0
       0      .1       0   73.59     .12       0  222.33      .1       0
  311.52     .12       0   405.2    .045       0   430.3     .12       0
  509.43      .1       0  560.54     .12       0  661.67     .06       0
Bank Sta=405.2,430.3
XS Rating Curve= 0 ,0
Exp/Cntr=0.5,0.3

Type RM Length L Ch R = 1 ,58894   ,187.3,178.2,168.1
XS GIS Cut Line= 3
2378034.03375024619249.649533207 2377648.6215273618877.216432517
 2377218.5125951618902.468861895
#Sta/Elev= 30
       0 3731.15    35.4 3723.79    49.1 3719.34    65.8 3718.01   188.2 3681.37
   258.9 3656.52   326.3 3628.11   360.6 3620.78   371.7 3619.08   382.8 3620.74
   393.9 3621.73   421.8 3619.02     444 3619.42   466.3 3622.74   494.1 3630.36
   549.9 3652.29   565.9 3656.44   593.9 3669.11   626.4 3681.19     650 3692.83
   706.1 3716.65   754.2 3733.83   766.2 3740.05   782.3 3742.11   802.3 3751.69
   814.3 3754.77   878.4 3777.36     914 3783.69   934.5 3785.39   966.8 3785.16
#Mann= 6 ,-1 , 0
       0     .12       0   360.6    .045       0   382.8     .12       0
  418.42      .1       0  556.31     .12       0  755.99     .06       0
Bank Sta=360.6,382.8
XS Rating Curve= 0 ,0
Exp/Cntr=0.3,0.1

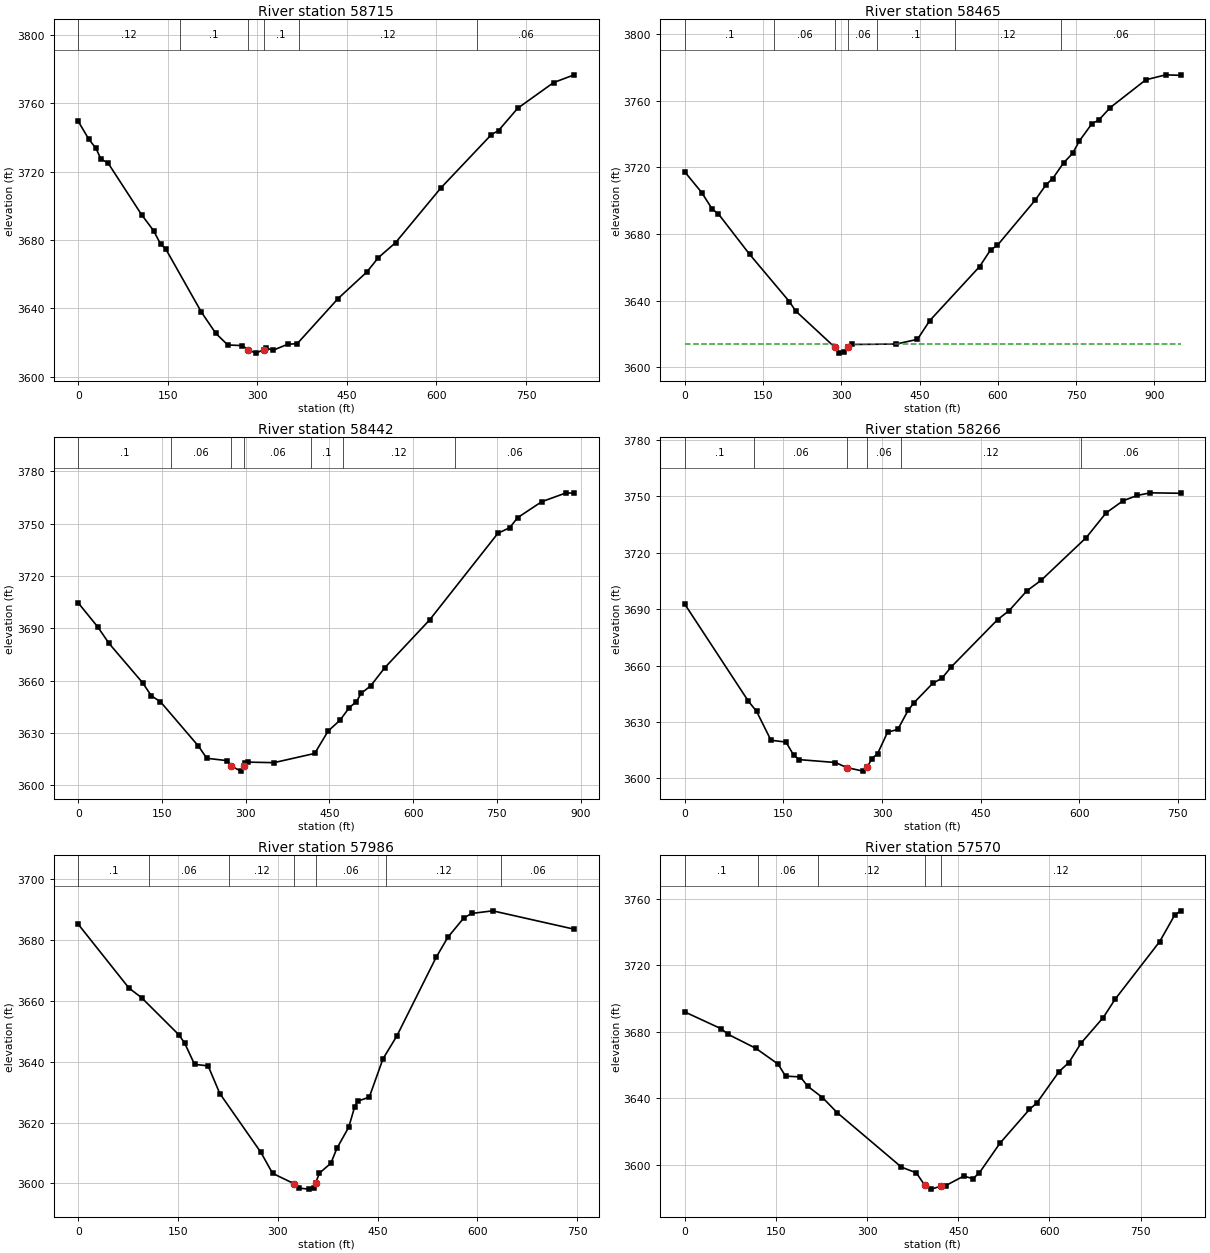
Type RM Length L Ch R = 1 ,58715   ,273.3,250.9,239
XS GIS Cut Line= 2
2378088.36502993618797.3093444132377260.40354185618864.857945466
#Sta/Elev= 30
       0 3749.24    17.5 3738.93    29.7 3733.47    37.7 3727.39    49.8 3724.97
     106 3694.79     126 3685.51   138.1 3677.43   146.1 3674.99   206.3 3637.81
   230.4 3625.44   250.4 3618.71   274.5 3618.32     285 3615.85   297.2 3613.93
   310.3 3615.86   314.7 3616.84   326.7 3615.69   350.8  3619.1   366.8 3619.48
   435.1 3645.79   483.2 3661.25   502.6 3669.69   531.4 3678.44   607.6  3710.5
   691.9 3741.54     704 3743.97   736.1 3756.97   796.3 3771.98   830.7  3776.5
#Mann= 6 ,-1 , 0
       0     .12       0   169.7      .1       0     285    .045       0
   310.3      .1       0  368.97     .12       0  667.86     .06       0
Bank Sta=285,310.3
XS Rating Curve= 0 ,0
Exp/Cntr(USF)=0,0
Exp/Cntr=0.5,0.3

Type RM Length L Ch R = 1 ,58465   ,22.6,22.6,22.7
XS GIS Cut Line= 3
2377729.93853701618294.4943046382377735.13252864618671.846541136
     2377195.925      618865.154
#Sta/Elev= 30
       0 3717.32    32.4 3704.95    52.4 3695.04    64.4 3692.08   124.4 3667.74
   200.4 3639.42   212.4  3633.8     2873612.108   296.4 3608.45   304.4 3608.85
   312.4 3612.23   320.4 3613.65   405.1 3613.91   445.8 3616.72   469.4 3627.97
   564.8  3660.4     586 3670.49     599 3673.19     671 3700.18   692.2  3709.6
     705 3713.33   726.2 3722.87   743.2 3728.48     756 3735.84   780.4 3746.39
     793 3748.37   815.5 3756.02   883.5 3772.67   921.7 3775.66   950.2 3775.35
#Mann= 7 ,-1 , 0
       0      .1       0  171.04     .06       0  287.04    .045       0
   312.4     .06       0  368.04      .1       0  518.28     .12       0
  720.31     .06       0
#XS Ineff= 2 , 0
             285    3614     324            3614
Permanent Ineff=
       F       F
Bank Sta=287,312.4
XS Rating Curve= 0 ,0
Exp/Cntr=0.5,0.3

Type RM Length L Ch R = 1 ,58442   ,168.7,175.5,177.8
XS GIS Cut Line= 3
 2377700.4763499618303.9596217452377714.65910471618654.129591179
2377205.43405158618827.651415789
#Sta/Elev= 30
       0 3704.54      35 3690.75      55 3681.39     115  3658.9     131  3651.3
   147.1 3647.96   215.1 3622.57   230.2 3615.54   267.2 3614.17   274.3 3611.05
   291.2 3608.18   296.9 3610.95   299.2 3612.85   303.2 3613.34   350.5 3613.03
   423.5 3618.32   447.6 3631.18   468.7  3637.3   485.6 3644.62   498.3 3647.98
   506.7 3652.77   523.6 3656.99     549 3667.44   629.3 3694.81   751.8 3744.53
     773 3747.72   786.9 3753.42   830.1 3762.59   874.2 3767.71   888.4 3767.43
#Mann= 7 ,-1 , 0
       0      .1       0  165.59     .06       0   274.3    .045       0
   296.9     .06       0  416.17      .1       0  473.33     .12       0
  674.79     .06       0
Bank Sta=274.3,296.9
XS Rating Curve= 0 ,0
Exp/Cntr=0.5,0.3

Type RM Length L Ch R = 1 ,58266   ,277.6,280.6,280.9
XS GIS Cut Line= 3
2377640.10339649618287.9879824582377507.79363158618645.891438598
2377161.19047018618782.523677193
#Sta/Elev= 30
       0  3692.6    96.7 3641.06   109.2 3635.65     131 3620.31   153.9 3619.34
   165.4 3612.49   173.7 3610.02   229.1 3608.48   246.2 3605.81   271.1  3603.9
   277.3 3605.92   284.6  3610.6   293.1 3613.09   308.4 3624.58     324 3626.08
   339.6 3636.18   348.5 3640.21   376.9  3650.5   391.3 3653.32   404.7 3659.08
   475.7  3684.4   493.4 3689.24   520.3 3699.73   541.8 3705.25   610.6 3728.02
   640.7 3741.12   666.5 3747.56     688 3750.39   708.1 3751.79   754.1 3751.56
#Mann= 6 ,-1 , 0
       0      .1       0  105.37     .06       0   246.2    .045       0
   277.3     .06       0  328.66     .12       0  602.88     .06       0
Bank Sta=246.2,277.3
XS Rating Curve= 0 ,0
Exp/Cntr=0.3,0.1

Type RM Length L Ch R = 1 ,57986   ,400.5,415.4,428.3
XS GIS Cut Line= 3
2377433.42210253618125.7700458232377242.65971758618539.219101159
2376986.56945568618675.383177263
#Sta/Elev= 30
       0  3685.1    76.1 3664.18      95 3661.04     151 3648.86   159.8 3646.13
   174.7 3639.13   195.1 3638.62   212.7 3629.54   274.4 3610.23     292 3603.33
     324 3599.95   331.6 3598.48   346.5 3598.14   353.7 3598.56   356.7 3600.19
   362.5  3603.4   379.7 3606.66   388.7 3611.54   406.5 3618.48   415.3 3625.08
   419.7    3627   437.4 3628.35     458 3640.94   478.7 3648.39   537.8 3674.23
   555.6 3680.89   579.3 3687.16   591.1 3688.68   622.9 3689.55   745.4 3683.52
#Mann= 7 ,-1 , 0
       0      .1       0  106.88     .06       0  226.78     .12       0
     324    .045       0   356.7     .06       0  462.58     .12       0
  635.14     .06       0
Bank Sta=324,356.7
XS Rating Curve= 0 ,0
Exp/Cntr=0.3,0.1

Type RM Length L Ch R = 1 ,57570   ,440,450,453.2
XS GIS Cut Line= 3
2377422.06546316 618096.48711579     2377022.211       618165.47
     2376616.987      618227.877
#Sta/Elev= 30
       0  3691.9    60.2 3681.72    70.7 3678.54     117 3669.99   153.6 3660.47
   165.7 3653.26   190.1 3652.79   202.2 3647.17   226.5 3640.39     251 3631.18
   356.5 3598.46   380.9 3595.04   394.93587.541   405.8 3585.23   421.4 3587.04
   429.5 3587.39   459.1 3593.12     474 3591.49   484.7 3595.06   518.5 3612.85
   567.1 3633.23   579.2 3637.09   615.7 3655.98   631.9 3661.42   652.1  3673.2
   688.5 3688.53   708.1  3699.6   781.4 3734.29   805.9 3750.14   815.8 3752.78
#Mann= 5 ,-1 , 0
       0      .1       0  120.23     .06       0  219.56     .12       0
  394.94    .045       0   421.4     .12       0
Bank Sta=394.9,421.4
XS Rating Curve= 0 ,0
Exp/Cntr=0.3,0.1