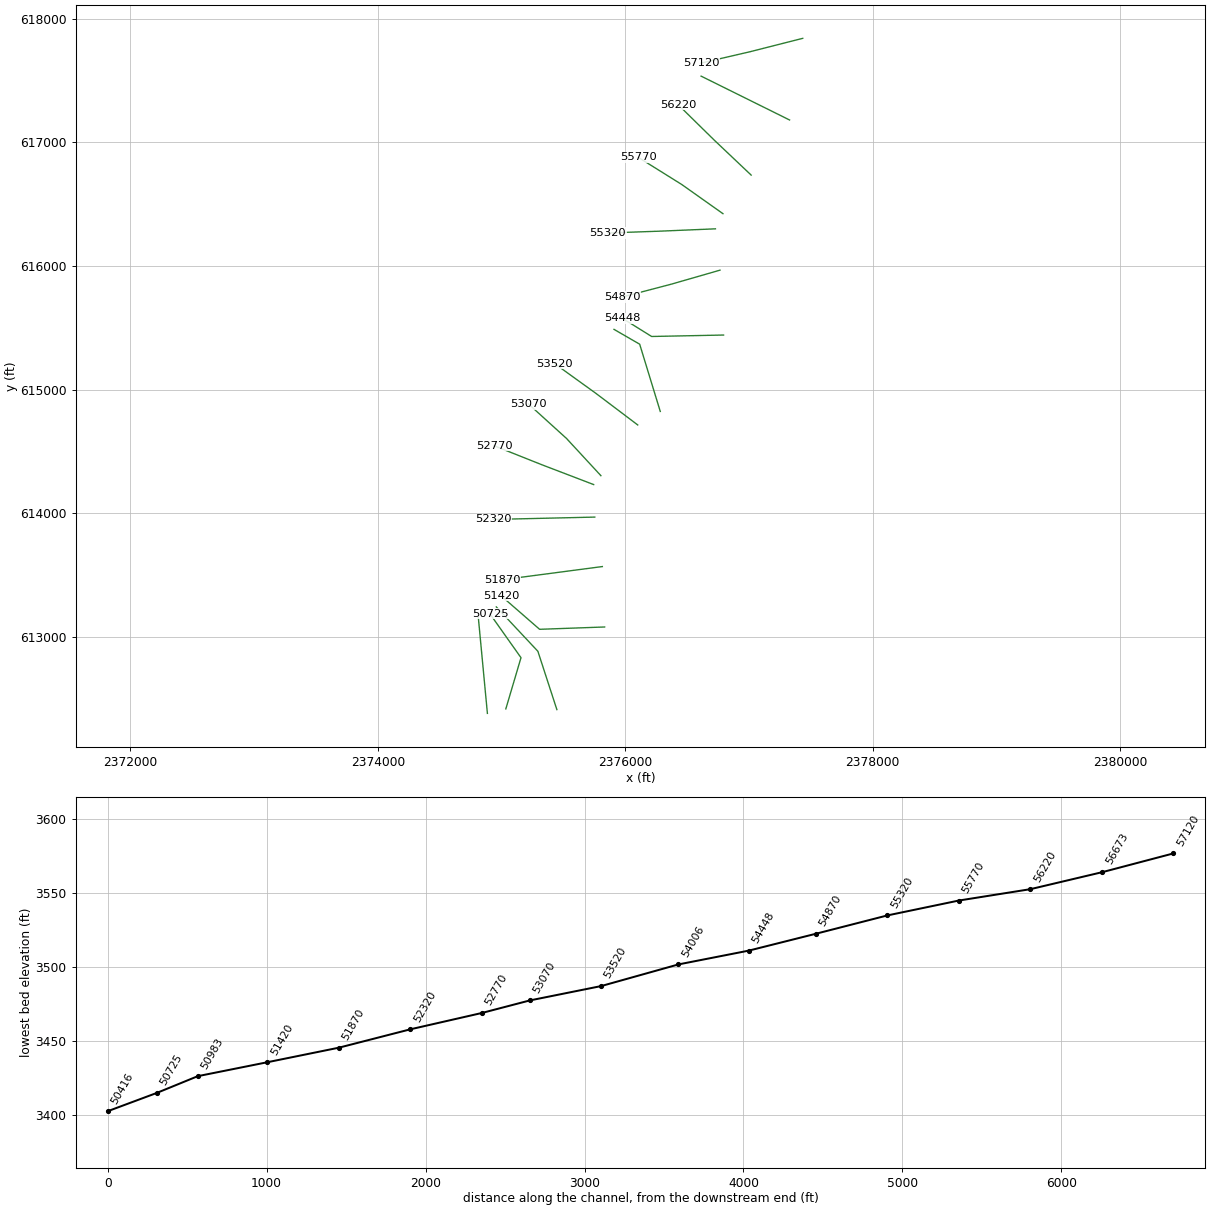
HEC-RAS study BIGRN.prj: BIGRN

--- BIGRN.g02 (geometry) --- (continued)

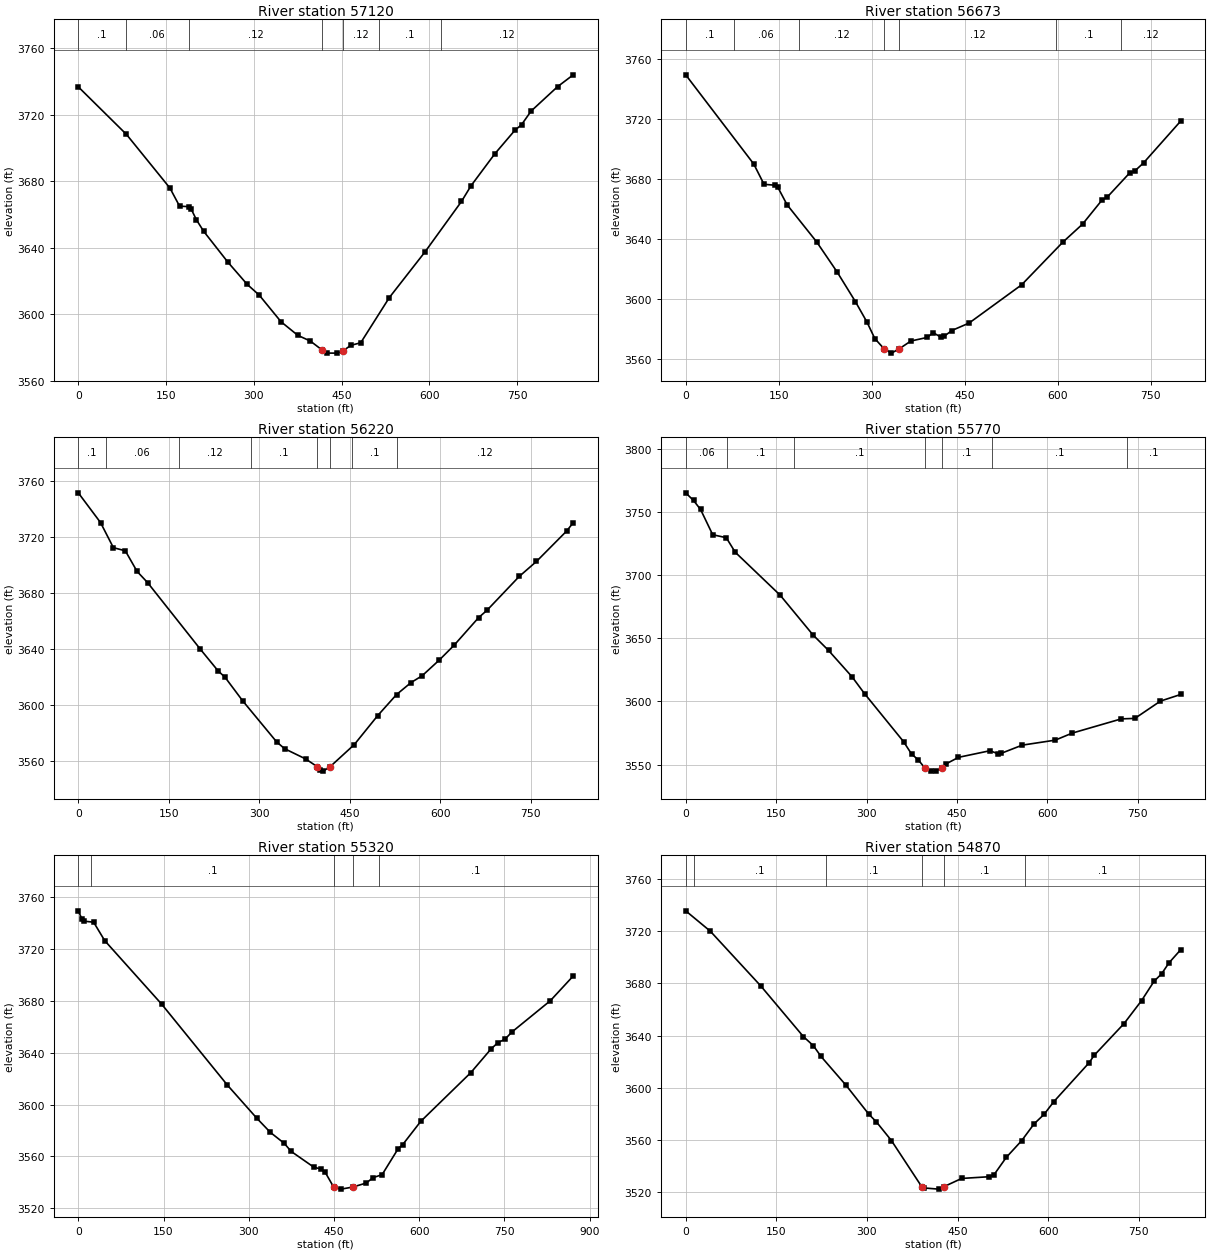
Type RM Length L Ch R = 1 ,57120   ,454.8,447.2,436.2
XS GIS Cut Line= 3
2377434.50330464 617841.26810054     2377009.846      617733.218
     2376612.566      617641.032
#Sta/Elev= 30
       0  3736.8    82.3 3708.18   156.6  3675.9   173.1    3665   189.6 3664.68
   192.6  3663.5     202 3656.72   214.4 3649.82   255.7 3631.28   288.7 3617.92
   309.3 3611.44   346.5 3595.43   375.3 3587.22   396.6 3583.81   417.1 3578.32
   424.9 3576.56   441.4 3576.54   452.7 3578.01   466.2 3581.28   482.7 3582.76
   531.7 3610.01   592.7 3637.51   654.9  3667.8   671.3 3677.29   711.9 3696.48
     746 3710.56   757.6 3714.03     774 3722.23   819.1 3736.88     846 3744.03
#Mann= 7 ,-1 , 0
       0      .1       0   80.72     .06       0  189.01     .12       0
   417.1    .045       0   452.7     .12       0  513.21      .1       0
  620.54     .12       0
Bank Sta=417.1,452.7
XS Rating Curve= 0 ,0
Exp/Cntr=0.3,0.1

Type RM Length L Ch R = 1 ,56673   ,453.3,452.8,446.2
XS GIS Cut Line= 2
2377327.91385185617181.0439610142376613.07715774617535.670578568
#Sta/Elev= 30
       0 3749.72   109.7  3690.2   126.3 3676.62   144.2 3676.02   148.7 3674.53
   163.4    3663   211.2 3638.16     244 3618.19   273.7 3598.25   292.2 3584.68
   304.9 3573.64   320.13566.684   331.7 3563.92   344.1 3566.75     363    3572
   389.8 3574.44   398.7 3577.65   411.1 3574.65   416.6 3575.11     429 3579.01
   456.8 3583.97   541.6 3609.53   608.1 3638.03   639.8 3650.04   671.1 3666.06
     680 3668.25   715.7 3684.18   724.5 3685.72   738.1  3690.9     798 3718.82
#Mann= 7 ,-1 , 0
       0      .1       0   77.98     .06       0  181.93     .12       0
  320.16    .045       0   344.1     .12       0  597.75      .1       0
   701.7     .12       0
Bank Sta=320.1,344.1
XS Rating Curve= 0 ,0
Exp/Cntr=0.3,0.1

Type RM Length L Ch R = 1 ,56220   ,447.7,450,452
XS GIS Cut Line= 3
     2377017.528        616735.4     2376720.492      617016.991
     2376426.858      617305.376
#Sta/Elev= 30
       0 3751.72    36.9 3730.42    58.2 3712.45      78 3710.21    97.5 3695.45
   114.8  3687.5   202.5  3639.7   231.8 3624.26   243.5 3619.59   272.5 3602.85
     329 3573.35   342.3 3568.47   377.2 3561.14   396.33555.601   400.7 3553.38
   406.2 3552.44   417.5 3555.55   457.7 3571.43   496.7 3592.26   527.8 3607.27
   551.9 3615.87   570.3 3620.74   598.6 3631.94   623.2 3642.55     664  3662.4
   677.8 3667.59   731.3 3691.86   759.8 3702.56   809.8 3724.31   820.9 3730.36
#Mann= 8 ,-1 , 0
       0      .1       0   46.08     .06       0  166.25     .12       0
  286.42      .1       0  396.29    .045       0   417.5     .12       0
  454.35      .1       0  528.21     .12       0
Bank Sta=396.3,417.5
XS Rating Curve= 0 ,0
Exp/Cntr=0.3,0.1

Type RM Length L Ch R = 1 ,55770   ,440.8,450,460.6
XS GIS Cut Line= 3
      2376789.63      616423.369     2376456.019      616659.701
     2376106.304      616878.125
#Sta/Elev= 30
       0 3765.34      13 3759.28    24.7 3752.13    44.8 3732.14    67.3 3729.78
    82.2 3718.26   156.7 3684.24   211.2 3652.73     237 3640.43     276 3619.54
   296.7  3606.2   361.4 3568.17   374.7 3558.36   385.9  3553.7   397.23547.004
   406.3 3544.78     415 3544.85   424.5 3547.32   432.4 3550.62   452.6 3555.71
   504.7 3560.94   518.8 3558.46   523.5  3558.9   558.3 3565.37   613.1 3569.34
   641.4 3574.93   722.7 3586.19   745.2 3586.56   787.6 3600.27   821.2 3605.53
#Mann= 7 ,-1 , 0
       0     .06       0   68.72      .1       0  179.31      .1       0
  397.25    .045       0   424.5      .1       0  508.45      .1       0
  732.71      .1       0
Bank Sta=397.2,424.5
XS Rating Curve= 0 ,0
Exp/Cntr=0.3,0.1

Type RM Length L Ch R = 1 ,55320   ,446.5,450,453.9
XS GIS Cut Line= 3
2376729.06247719616300.708866667     2376266.934      616281.313
     2375858.527      616267.157
#Sta/Elev= 30
       0  3749.4     6.3 3743.15    10.3 3741.42      27 3740.63    46.5 3726.43
   146.8 3677.38   262.5 3614.95   313.9 3589.57   338.2 3578.45   362.6 3570.03
   374.6 3563.86   414.7 3551.62   426.7 3550.31   434.7 3547.62   449.7 3536.14
   462.5 3534.74   482.7  3536.3   506.8 3539.44   518.8 3543.57   534.8 3545.93
   562.8 3565.79   570.8 3568.97   602.8 3587.02   690.9  3624.6   726.9 3643.07
   738.9 3647.81   750.9 3650.31   762.9 3655.82   830.9 3680.09   871.2 3699.17
#Mann= 5 ,-1 , 0
       0     .06       0      22      .1       0   449.7    .045       0
   482.7      .1       0  528.88      .1       0
Bank Sta=449.7,482.7
XS Rating Curve= 0 ,0
Exp/Cntr=0.3,0.1

Type RM Length L Ch R = 1 ,54870   ,426.7,422,417.5
XS GIS Cut Line= 3
     2376765.853      615966.514     2376372.378      615853.168
     2375976.155      615749.181
#Sta/Elev= 30
       0 3735.63    40.7 3720.04     124 3678.21   194.7  3639.3   211.4 3632.23
   223.9 3624.06   265.5 3601.86   302.9 3579.87   315.7 3573.83   340.4 3559.63
   390.4 3524.39   394.5 3523.28   418.4 3522.38   427.7 3524.35   456.7 3530.57
   502.1 3531.88   510.4 3533.53   530.6 3546.75   555.9 3559.48   576.6 3572.42
   593.1 3579.69   609.2 3589.42   667.6 3619.22   675.8 3624.82   725.5 3649.29
   754.4 3666.84   775.1 3681.67   787.5 3687.34   799.9 3695.85   819.1  3705.8
#Mann= 6 ,-1 , 0
       0     .06       0   13.32      .1       0  232.99      .1       0
   390.4    .045       0   427.7      .1       0  560.85      .1       0
Bank Sta=390.4,427.7
XS Rating Curve= 0 ,0
Exp/Cntr=0.3,0.1

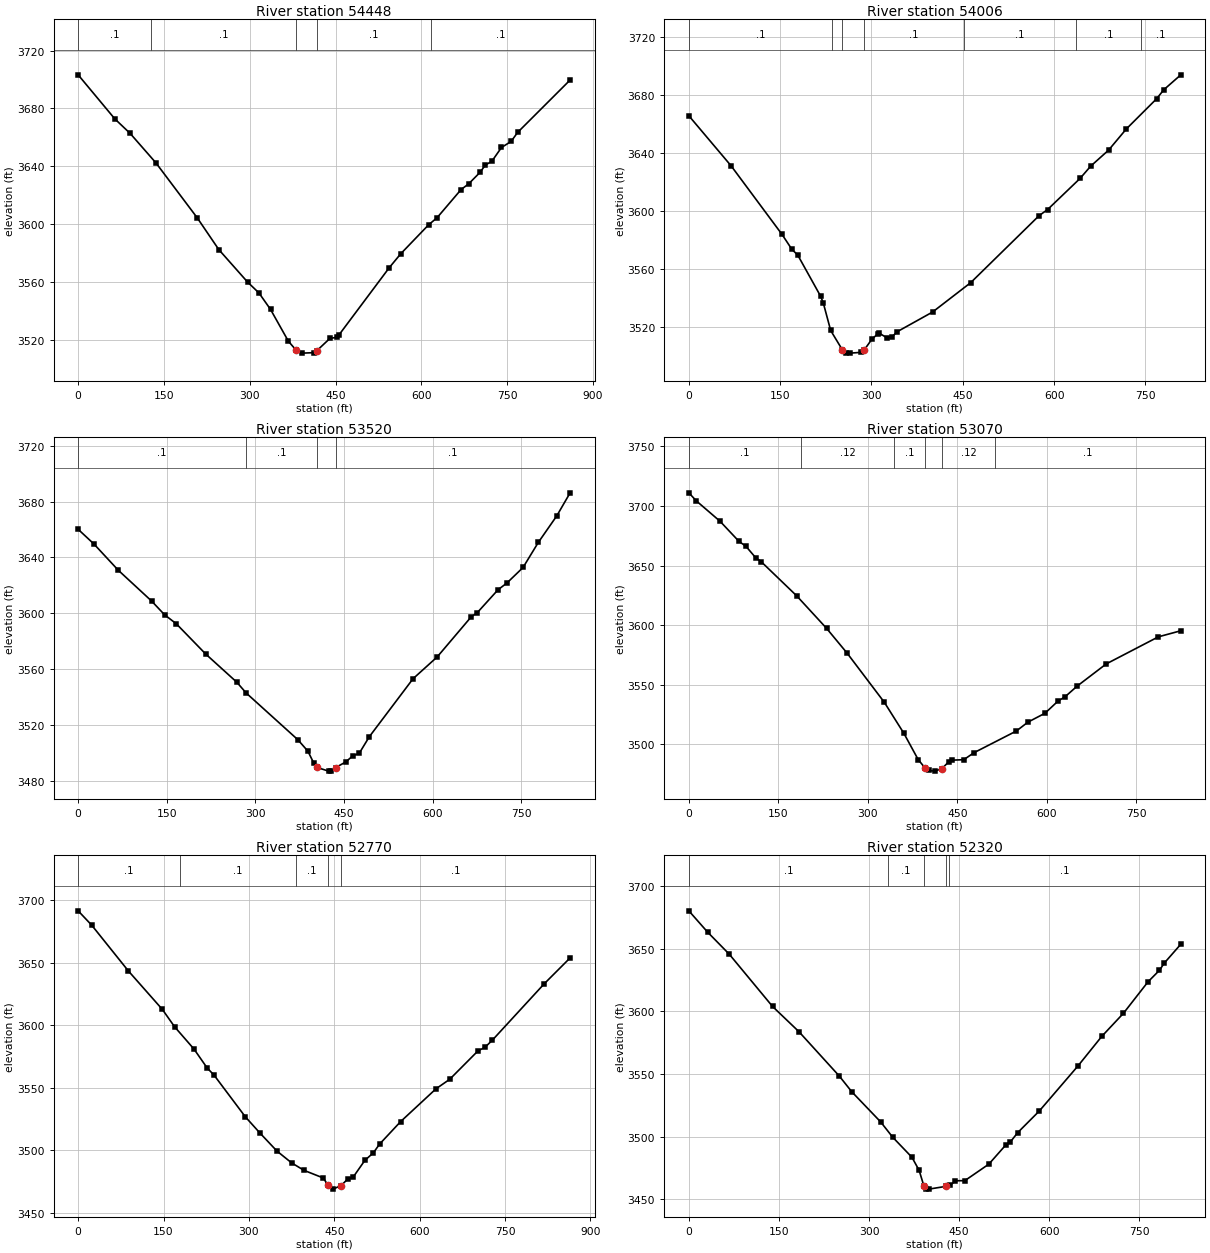
Type RM Length L Ch R = 1 ,54448   ,464.1,442.1,418.9
XS GIS Cut Line= 3
     2376794.766      615441.8072376213.52962807615430.129470176
     2375976.869      615577.332
#Sta/Elev= 30
       0 3703.23      64 3672.86      91 3662.73     136 3642.42   208.1 3604.52
     246 3582.49   296.1 3560.16   316.1 3552.59   336.3 3541.24   367.6 3519.22
   380.8  3513.2   392.1 3511.02   412.1 3511.34   417.6 3512.81   440.1 3521.16
   452.1 3521.96   456.1 3523.64   544.1 3570.13   564.1 3579.68   612.9 3599.71
   627.5 3604.54   669.4 3623.96   682.7 3627.92     703 3636.02   711.8 3640.91
   723.3 3643.53   740.1 3653.05     757 3657.23   768.3 3663.44   860.1 3699.65
#Mann= 5 ,-1 , 0
       0      .1       0  126.64      .1       0   380.8    .045       0
   417.6      .1       0  617.46      .1       0
Bank Sta=380.8,417.6
XS Rating Curve= 0 ,0
Exp/Cntr=0.3,0.1

Type RM Length L Ch R = 1 ,54006   ,469.7,485.9,489.9
XS GIS Cut Line= 3
2376283.07065965614824.0405122822376116.72863168 615367.77020256
     2375909.292      615487.627
#Sta/Elev= 30
       0 3665.53    69.5 3630.94   153.1 3583.63   169.1 3573.46   178.9 3569.39
   216.3 3541.12   220.8 3536.47     233 3517.36   252.4 3503.85   258.1 3501.88
   265.2 3501.73   283.2 3502.27   287.6 3503.62   300.4 3511.17     310 3514.92
   313.2 3515.42   325.1 3512.34   333.4  3512.7   341.8  3516.4   400.4 3530.09
   463.1 3550.38   575.5 3596.64   589.4 3600.83   642.6 3622.25   660.2 3630.78
   689.5 3641.79   718.7 3656.43   768.5 3677.29   780.2 3683.47   808.2 3693.78
#Mann= 7 ,-1 , 0
       0      .1       0  235.82      .1       0   252.4    .045       0
   287.6      .1       0  452.56      .1       0  636.05      .1       0
   742.3      .1       0
Bank Sta=252.4,287.6
XS Rating Curve= 0 ,0
Exp/Cntr=0.3,0.1

Type RM Length L Ch R = 1 ,53520   ,449.4,450,446.6
XS GIS Cut Line= 3
2376100.98379158614714.700336843     2375761.504      614971.229
2375431.06042143615209.464526789
#Sta/Elev= 30
       0 3660.15    26.9 3649.57      68 3630.85   124.5 3608.78   146.3 3599.01
   166.2 3592.56   215.9 3570.95   268.5 3550.81   284.4 3543.08   371.9 3509.64
   388.9 3501.47   398.9 3492.91   404.4 3489.81   423.9 3487.15   428.9 3487.39
     436 3489.73     453 3493.67   464.5 3497.95   475.9 3499.92   493.1 3511.85
     567 3553.26   607.8 3568.82   665.6  3597.6   675.5 3600.42   710.9 3616.92
   725.9 3621.73   753.2 3632.83     779 3650.74   810.3 3669.75   832.9 3686.25
#Mann= 4 ,-1 , 0
       0      .1       0  284.32      .1       0   404.4    .045       0
  435.97      .1       0
Bank Sta=404.4,436
XS Rating Curve= 0 ,0
Exp/Cntr=0.3,0.1

Type RM Length L Ch R = 1 ,53070   ,294.8,300,303.6
XS GIS Cut Line= 3
     2375803.359      614304.474     2375524.974      614605.843
     2375218.146      614884.179
#Sta/Elev= 30
       0 3710.99    12.7 3704.17    52.3 3687.12    84.2 3670.16    95.6 3666.18
   112.2  3656.4     121 3653.32   180.5 3624.66   230.8 3597.28   265.4 3576.36
   327.7 3535.13   360.5 3509.06   384.3 3487.17   395.9 3480.06   401.8 3477.97
   411.8 3477.44   424.1 3479.51   435.6 3485.31   441.6 3486.65   460.7 3487.03
   478.1 3492.96   548.8 3511.08   568.3 3518.56   596.9 3526.02   618.5 3536.14
   630.6 3539.88   650.9 3548.84   699.5 3567.41   786.9 3590.15   824.5 3595.24
#Mann= 6 ,-1 , 0
       0      .1       0  187.58     .12       0  344.47      .1       0
   395.9    .045       0   424.1     .12       0  513.21      .1       0
Bank Sta=395.9,424.1
XS Rating Curve= 0 ,0
Exp/Cntr=0.3,0.1

Type RM Length L Ch R = 1 ,52770   ,447.1,450,454.1
XS GIS Cut Line= 3
     2375744.984      614232.506     2375326.322      614392.829
2374939.69901853   614546.754668
#Sta/Elev= 30
       0 3691.48    23.8 3680.03    88.1 3643.51     148 3612.66   169.4 3598.84
   203.7  3580.9   226.6 3565.93     239 3560.04   293.7 3526.87   319.5 3513.83
   349.3 3499.46   375.2 3489.98   396.9 3484.03   430.7 3477.94   439.3 3471.96
   447.9 3469.03   461.9 3471.87   473.7 3477.06   483.4 3478.75   503.8 3492.03
   518.8 3498.09   529.6    3505   566.6    3523   628.7  3549.2   652.8  3556.8
   702.6 3579.56   714.8 3582.38   727.7 3588.06   819.1 3633.25   864.4 3653.86
#Mann= 5 ,-1 , 0
       0      .1       0  179.52      .1       0   382.4      .1       0
   439.3    .045       0   461.9      .1       0
Bank Sta=439.3,461.9
XS Rating Curve= 0 ,0
Exp/Cntr=0.3,0.1

Type RM Length L Ch R = 1 ,52320   ,447.9,450,451.9
XS GIS Cut Line= 3
     2375754.006      613969.508     2375344.616      613960.047
     2374935.225      613950.585
#Sta/Elev= 30
       0 3680.39    31.3 3663.34    67.3 3645.72   139.3    3604   183.3 3583.81
   250.5 3548.34   271.3 3535.79   319.3 3511.74   339.4 3499.48   371.4 3483.47
   383.4 3472.97   391.4 3460.37   395.4 3458.21   399.4 3458.02   427.4 3460.17
   435.4 3461.16   443.7  3464.7   459.4 3464.78   499.4 3477.98   527.4 3493.19
   535.4 3495.83   547.4 3503.14   583.4 3520.44   647.4 3556.22   687.4 3580.06
   723.5 3598.53   764.4 3623.67   783.5  3632.9   791.5 3638.65     819 3653.71
#Mann= 5 ,-1 , 0
       0      .1       0  331.68      .1       0   391.4    .045       0
   427.4      .1       0   432.7      .1       0
Bank Sta=391.4,427.4
XS Rating Curve= 0 ,0
Exp/Cntr=0.3,0.1

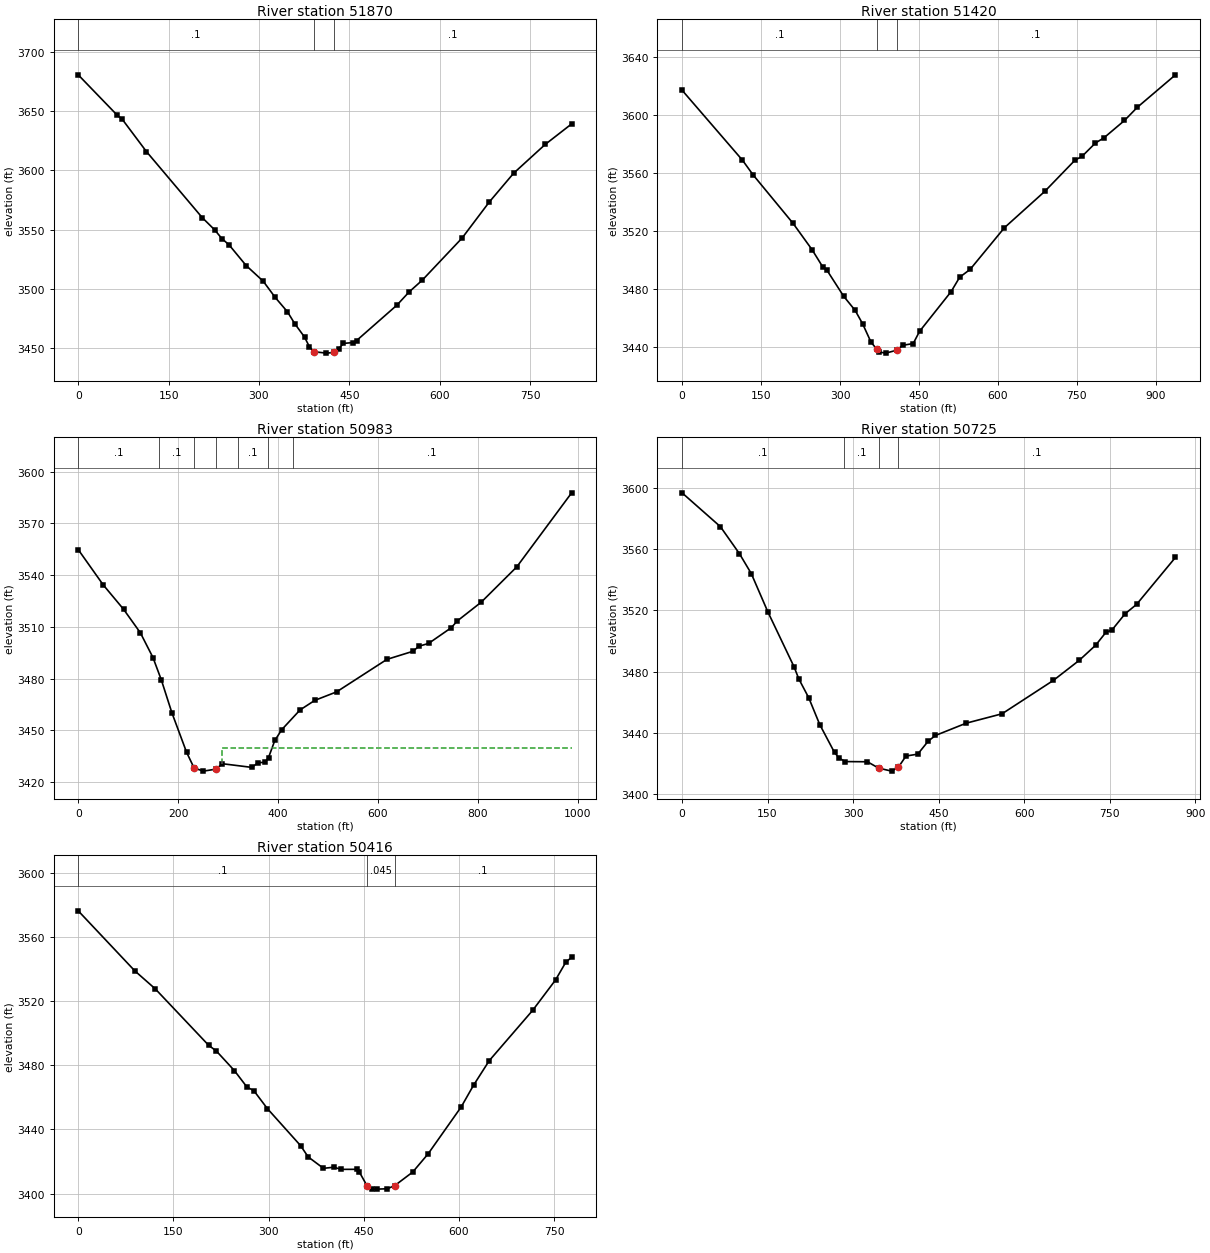
Type RM Length L Ch R = 1 ,51870   ,452.5,450.7,449.2
XS GIS Cut Line= 3
     2375815.098      613569.527     2375409.111         613516.
     2375003.124      613462.474
#Sta/Elev= 30
       0 3680.58    64.9 3646.41      73 3643.11   113.3 3615.75   205.8 3560.05
   226.3 3549.79   238.4 3542.37   250.5 3536.95   278.7 3519.59     307 3506.39
     327 3492.63   347.3 3480.52   359.4 3470.49   375.6 3459.23   383.6 3451.15
   391.2 3446.82   411.9 3445.63     424 3446.17   432.1  3449.1   440.1 3453.84
   456.3 3454.55   462.1 3456.27   528.9 3486.11   549.1 3497.22     571 3507.19
   637.2 3542.81   682.2 3573.16   722.7 3597.51     775 3621.77     819 3639.16
#Mann= 3 ,-1 , 0
       0      .1       0   391.2    .045       0     424      .1       0
Bank Sta=391.2,424
XS Rating Curve= 0 ,0
Exp/Cntr=0.3,0.1

Type RM Length L Ch R = 1 ,51420   ,473,437.1,418.4
XS GIS Cut Line= 3
     2375833.515      613080.8732375307.97131967613062.072842263
     2374997.626      613332.227
#Sta/Elev= 30
       0 3617.42   114.8 3569.05   134.9 3558.95   210.9 3525.43   246.9 3507.29
   266.9 3495.57   275.1 3493.15     307 3475.09   328.8 3465.33     343 3456.06
     359 3443.33   370.3 3438.39     375 3436.54     387 3435.81   407.6 3437.81
     419  3441.2   439.1 3442.43   451.1 3450.82   511.1 3478.29   527.3 3488.21
   547.2 3493.64   612.4 3522.45   688.9 3547.49   746.4 3569.09   759.8 3571.72
   785.3 3580.96   801.3 3584.48   840.4 3596.49   864.7 3605.57   937.3 3628.03
#Mann= 3 ,-1 , 0
       0      .1       0   370.3    .045       0   407.6      .1       0
Bank Sta=370.3,407.6
XS Rating Curve= 0 ,0
Exp/Cntr=0.3,0.1

Type RM Length L Ch R = 1 ,50983   ,280.5,258,252
XS GIS Cut Line= 3
2375447.47623849612412.6487749932375294.03626489612884.298467213
     2374958.099      613243.032
#Sta/Elev= 30
       0 3554.86      50 3534.41    90.7 3520.28   124.3 3506.66   149.6 3492.28
   166.4 3479.26   187.4 3460.32   216.9 3437.33   231.93428.257   250.5 3426.43
   275.8 3427.59   288.4 3430.73   347.3  3428.6   359.9 3431.25   373.7  3431.6
   380.9 3434.32   393.5 3444.24   407.6 3450.55     444 3461.91   473.5 3467.45
   517.1 3472.37   617.8 3491.21   669.4 3495.85   682.2 3498.86   701.1 3500.44
   746.6 3509.57   758.3 3513.41   806.4 3524.33   877.7 3544.84   987.5 3587.76
#Mann= 7 ,-1 , 0
       0      .1       0  161.88      .1       0  231.87    .045       0
   275.8      .1       0  319.56      .1       0  378.92      .1       0
  428.89      .1       0
#XS Ineff= 2 , 0
                          287.02          3439.7
Permanent Ineff=
       F       F
Bank Sta=231.9,275.8
XS Rating Curve= 0 ,0
Exp/Cntr=0.3,0.1

Type RM Length L Ch R = 1 ,50725   ,304.4,309.1,320.5
XS GIS Cut Line= 3
2375034.98096686612418.4770214432375157.58979532612832.447483431
2374907.07051072613186.528126705
#Sta/Elev= 30
       0 3596.79    67.2 3574.73   100.6  3557.1   121.4  3544.1   150.6 3519.01
   196.5 3483.17   204.8 3475.32   222.2 3463.02   241.5 3445.54   267.4  3427.3
   275.8 3423.52   286.6 3421.36   325.2 3421.24   344.7 3417.11   367.5 3415.13
   379.5 3417.71   392.8 3424.99   413.4 3426.21   431.7 3434.68   444.5 3438.41
   498.4 3446.43   561.3 3452.56   651.4 3474.38   696.7 3487.46   725.4 3497.29
   743.4  3505.7   754.1 3507.26     777  3517.8   797.3 3523.99   865.5 3554.66
#Mann= 4 ,-1 , 0
       0      .1       0  284.44      .1       0   344.7    .045       0
   379.5      .1       0
Bank Sta=344.7,379.5
XS Rating Curve= 0 ,0
Exp/Cntr=0.3,0.1

Type RM Length L Ch R = 1 ,50416   ,424.9,435.4,458.3
XS GIS Cut Line= 2
2374886.07191813612382.1879337242374812.85766862613156.144906433
#Sta/Elev= 30
       0 3576.23    89.1 3538.84   121.2 3527.67   205.6  3492.4   217.7 3488.85
     246 3476.69   265.9 3466.39   276.7 3464.16     298 3452.99   350.3 3429.92
   362.3 3422.88   386.4 3415.76   402.5 3416.45   414.5 3415.12   438.7 3415.14
   442.7 3413.59   455.2 3404.77   462.5 3402.87   470.8  3402.8   486.9 3403.03
   498.5 3404.94     527 3413.44   551.2 3424.75   603.4 3454.04   622.8 3467.52
   647.6 3482.88   715.9 3514.17     752 3533.14   768.1 3544.13   777.4 3547.33
#Mann= 3 ,-1 , 0
       0      .1       0   455.2    .045       0   498.5      .1       0
Bank Sta=455.2,498.5
XS Rating Curve= 0 ,0
Exp/Cntr=0.3,0.1