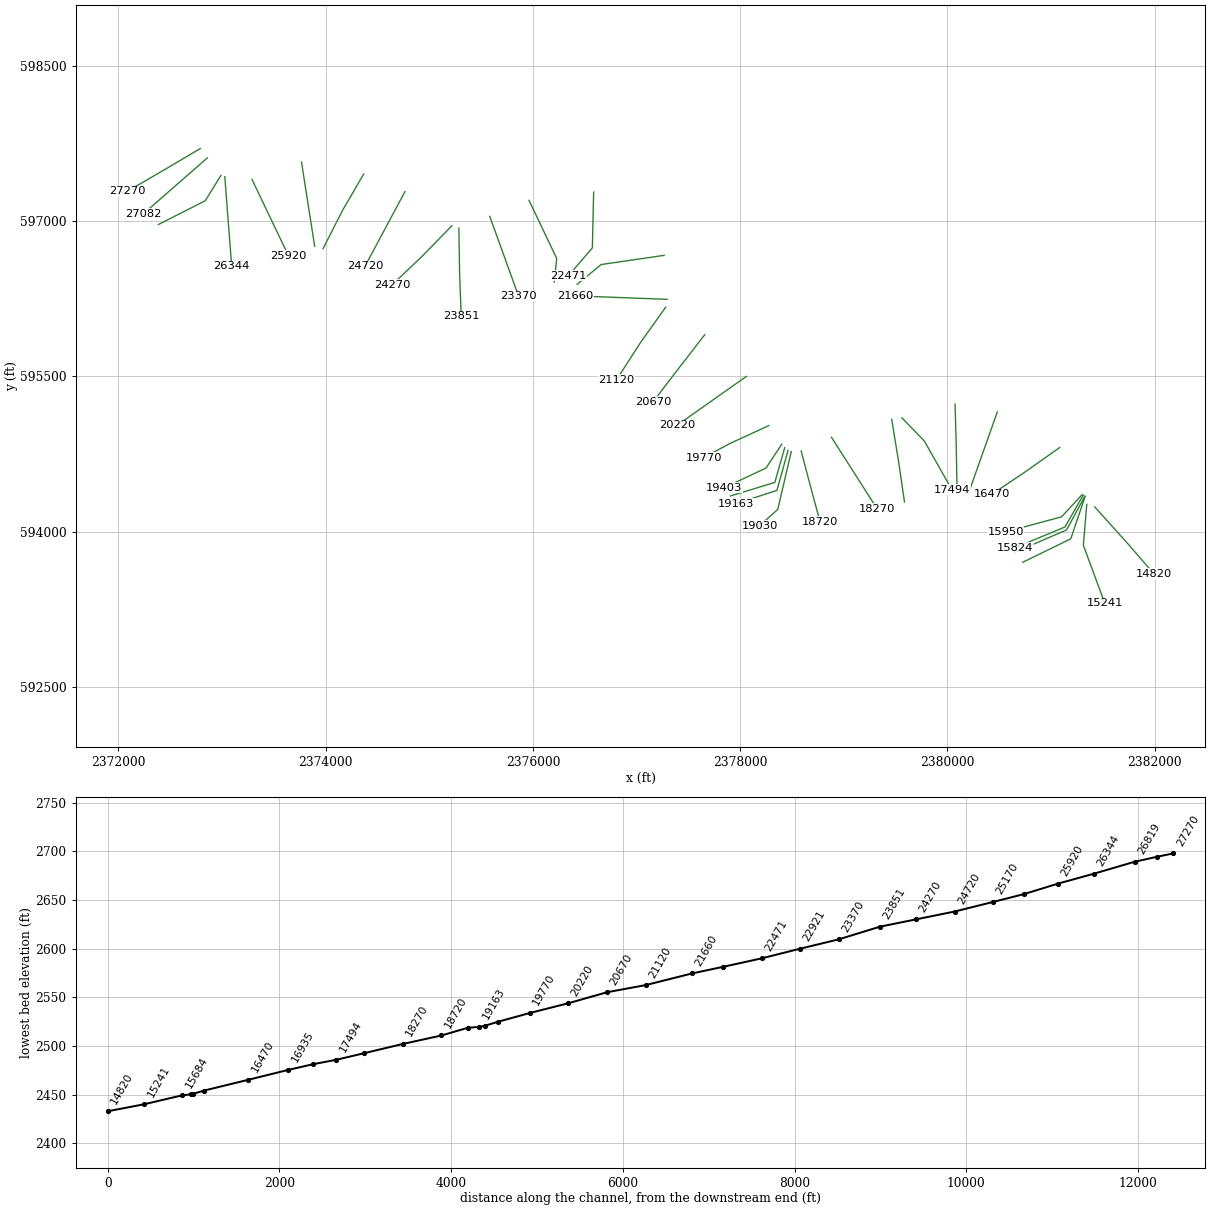
HEC-RAS study BIGRN.prj: BIGRN

--- BIGRN.g02 (geometry) --- (continued)

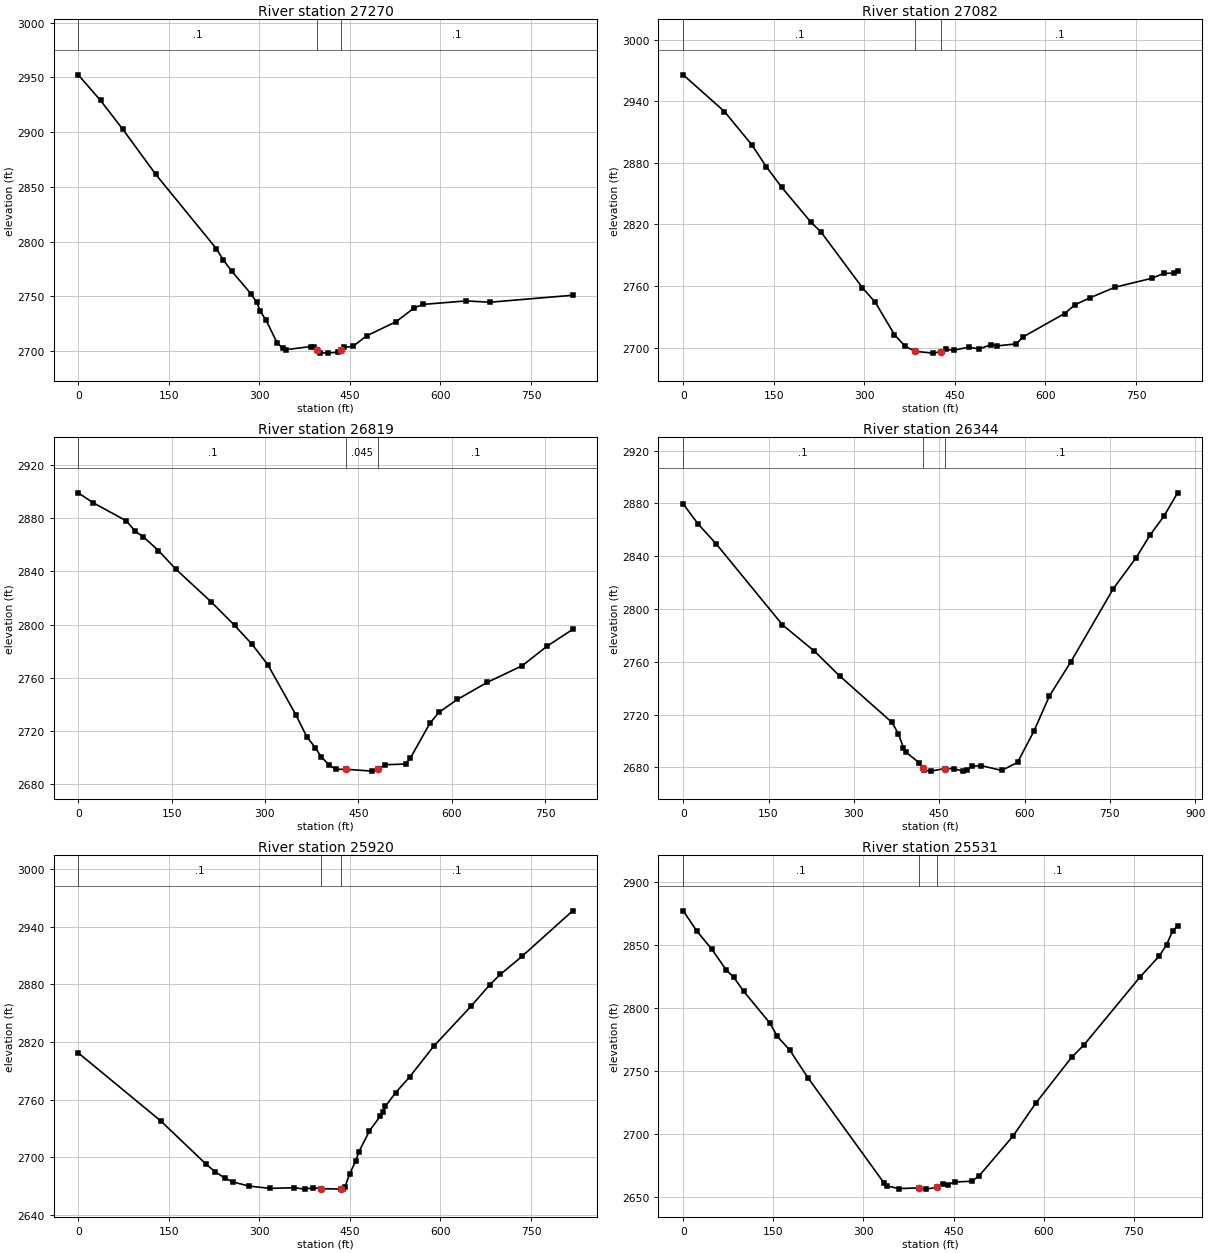
Type RM Length L Ch R = 1 ,27270   ,185.7,188.6,193.3
XS GIS Cut Line= 3
     2372790.488      597700.213     2372437.919      597491.896
     2372083.882      597286.115
#Sta/Elev= 30
       0 2952.37    36.9 2928.92    73.8 2902.56   128.4 2861.33   228.6 2793.54
   240.3 2783.21   254.2 2772.89   285.7 2752.44   295.7 2744.32   301.4 2736.36
     311 2728.18   329.6 2707.18   338.9 2702.28   343.5  2701.1   385.3 2704.01
     390 2703.55     395  2700.9   400.9  2698.4   413.2 2697.98   430.1  2698.9
   435.4 2701.08   440.9 2703.24   454.8 2704.11     478 2713.88   526.7 2726.77
   555.9 2739.11   570.5 2742.49   642.3 2745.69   682.1 2744.52     819 2750.89
#Mann= 3 ,-1 , 0
       0      .1       0     395    .045       0   435.4      .1       0
Bank Sta=395,435.4
XS Rating Curve= 0 ,0
Exp/Cntr=0.3,0.1

Type RM Length L Ch R = 1 ,27082   ,267.8,262.5,256.8
XS GIS Cut Line= 3
2372858.26447238597609.9774141212372549.99147238597340.427414121
2372241.71747239597070.876414121
#Sta/Elev= 30
       0  2965.8    68.4    2930   114.1 2897.24   137.9 2876.04   163.4 2856.04
   211.9 2821.95   227.8    2813   296.9 2758.28   318.2 2744.07     350 2712.57
   367.5 2701.29   384.5 2696.33   413.8 2694.58   427.6 2696.09   435.1 2698.19
   448.3 2697.48   472.6 2700.35   490.8 2698.67   509.1 2702.75   520.6 2701.67
   551.6 2703.58   563.1 2710.42   631.7 2733.16   648.8 2741.61   674.2 2748.66
   715.7 2758.86   776.4 2767.54   796.4 2772.37   812.3 2772.49     819  2774.9
#Mann= 3 ,-1 , 0
       0      .1       0   384.5    .045       0   427.6      .1       0
Bank Sta=384.5,427.6
XS Rating Curve= 0 ,0
Exp/Cntr=0.3,0.1

Type RM Length L Ch R = 1 ,26819   ,438.6,475,495
XS GIS Cut Line= 3
     2372989.307      597440.5842372838.61041663597196.578208317
2372386.08254906 596966.54496318
#Sta/Elev= 30
       0 2899.34    23.4 2891.98    77.2 2878.22    91.3 2870.43   104.8 2866.05
   128.9 2855.74   157.1 2841.59   213.6 2817.07   251.2 2799.35   279.4 2784.99
   304.6 2769.66   349.5 2732.01   367.4 2715.14   380.9 2707.14   389.8 2700.45
   403.3 2693.99   414.1 2690.76   430.7 2690.79   472.4 2689.42   481.3  2690.8
     493 2694.25   525.9 2694.75   533.4 2699.05   564.8 2725.41   579.5 2733.81
   609.2 2743.51   656.8 2756.31   713.4 2768.96   753.3 2783.71   794.4 2796.32
#Mann= 3 ,-1 , 0
       0      .1       0   430.7    .045       0   481.3      .1       0
Bank Sta=430.7,481.3
XS Rating Curve= 0 ,0
Exp/Cntr=0.3,0.1

Type RM Length L Ch R = 1 ,26344   ,420.3,423.8,432.4
XS GIS Cut Line= 2
2373026.40616947597428.8990126322373093.17292211596562.235038947
#Sta/Elev= 30
       0 2879.63    26.1 2864.49    58.2 2849.28   174.5 2788.03   230.7 2768.05
   274.8 2749.38   367.1 2714.03   378.4 2705.33   387.2 2694.87   391.2  2691.7
   415.2 2683.29     421  2679.4   423.4 2677.82   435.3 2677.18   459.4 2679.02
   475.2  2679.1   491.5 2677.15   499.5 2677.92   507.5 2680.77   523.4 2681.41
   559.7 2677.67   587.7 2683.71   616.8 2707.67   643.9 2734.16   681.4 2759.95
   756.2 2815.49   796.4 2838.97   820.4 2855.89   845.1  2870.4   869.2 2888.08
#Mann= 3 ,-1 , 0
       0      .1       0     421    .045       0   459.4      .1       0
Bank Sta=421,459.4
XS Rating Curve= 0 ,0
Exp/Cntr=0.3,0.1

Type RM Length L Ch R = 1 ,25920   ,393.7,389.2,384.6
XS GIS Cut Line= 3
     2373288.811      597401.922     2373465.444      597032.475
     2373642.076      596663.027
#Sta/Elev= 30
       0 2808.69   136.4 2737.97   211.7 2692.81     227 2684.75   242.8 2678.34
   255.7 2674.36   282.7 2669.97   318.1 2667.56   358.1 2668.27   375.4  2666.8
   389.1 2668.35     4022667.279   435.7 2666.84   438.7  2667.1   441.7 2668.86
   449.6 2682.86   459.7 2696.13   464.5 2705.28   482.2 2727.25   499.9 2742.65
   504.4 2747.14   508.8 2753.12   525.6 2767.18   548.7 2783.52   588.6 2815.54
   650.7 2857.38   681.9 2879.87   699.4 2890.56   734.9 2909.22     819 2956.69
#Mann= 3 ,-1 , 0
       0      .1       0     402    .045       0   435.7      .1       0
Bank Sta=402,435.7
XS Rating Curve= 0 ,0
Exp/Cntr=0.3,0.1

Type RM Length L Ch R = 1 ,25531   ,373.7,360.8,349.5
XS GIS Cut Line= 2
     2373766.727      597569.705     2373893.773      596756.587
#Sta/Elev= 30
       0 2877.02    23.1 2860.73    47.4 2846.71    71.7 2830.04    83.8 2824.47
   100.5 2813.32   144.5 2787.83   156.7 2777.38   177.6 2766.37   207.4 2744.71
   334.4    2661   339.2 2658.75   359.1 2656.64     392 2657.19   403.7 2656.22
   422.7 2657.64     432 2660.25   440.1 2659.76   452.2 2661.91   480.6 2662.45
   492.8 2666.89   548.7 2698.12   587.2 2724.64   646.7 2760.87   666.8 2770.45
   759.9 2824.22   792.3 2841.09   804.5 2850.04   814.8 2861.12     823 2865.08
#Mann= 3 ,-1 , 0
       0      .1       0     392    .045       0   422.7      .1       0
Bank Sta=392,422.7
XS Rating Curve= 0 ,0
Exp/Cntr=0.3,0.1

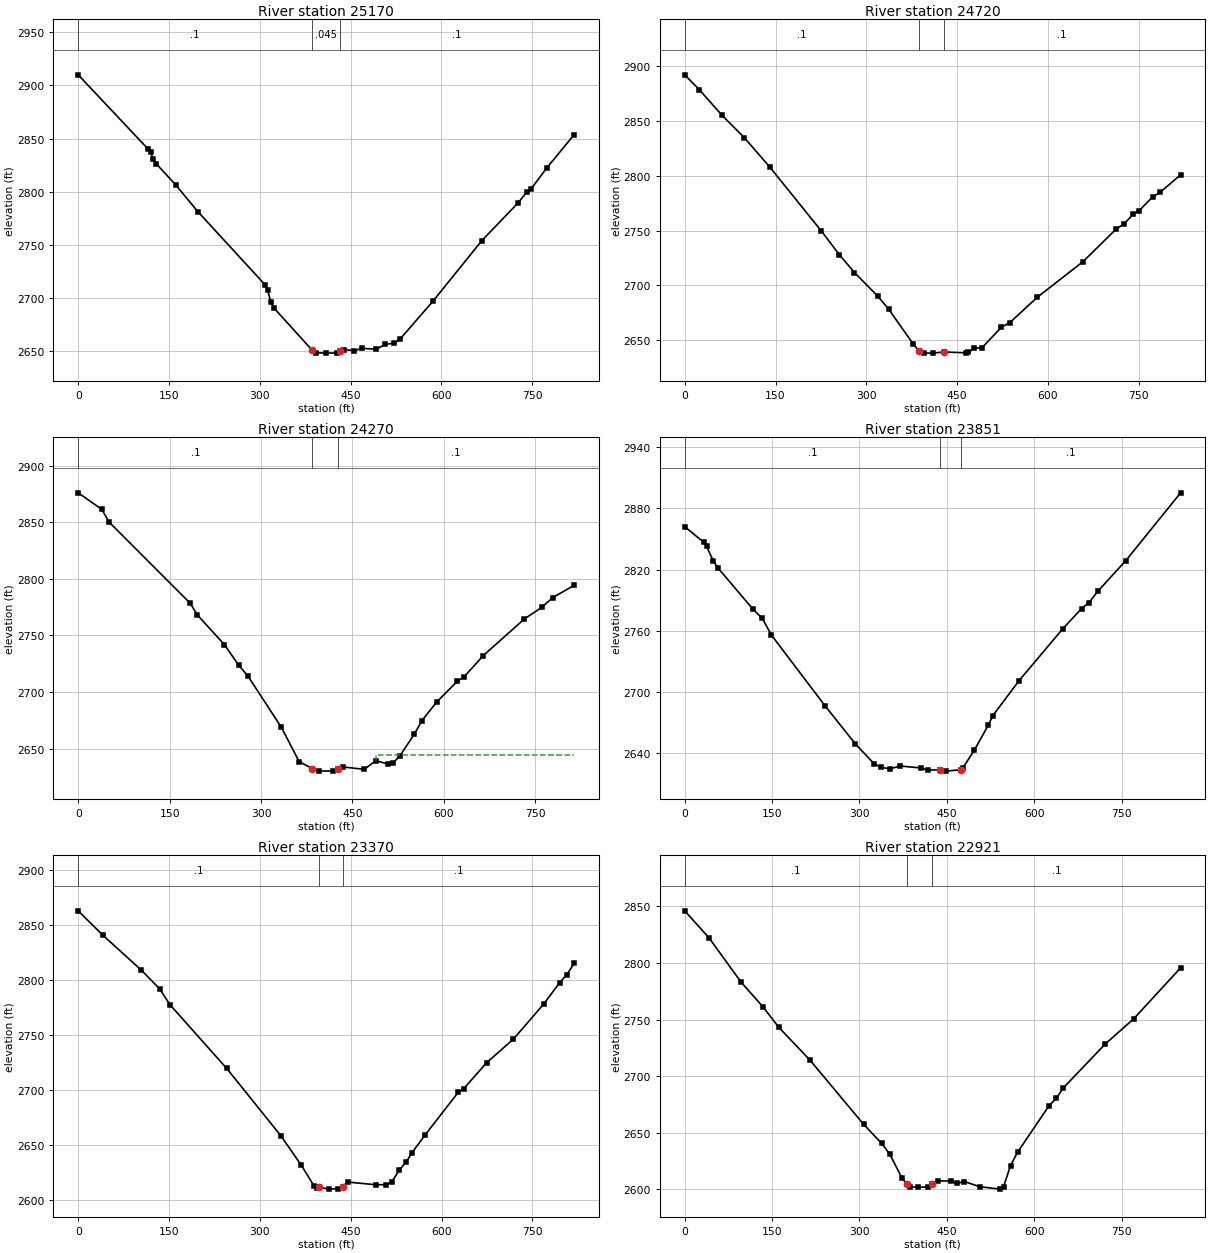
Type RM Length L Ch R = 1 ,25170   ,448.7,450,449.8
XS GIS Cut Line= 3
     2374367.259      597454.179      2374161.13      597100.146
      2373975.59      596734.904
#Sta/Elev= 30
       0    2910   114.9 2840.48   119.5  2837.3   124.1 2830.46   128.8  2826.4
   160.8  2806.6   198.2 2780.93   309.3 2712.06   312.9 2707.13   318.5 2695.96
   323.2 2690.69     386 2651.22   392.6  2648.6   409.4 2648.13   427.3 2648.35
   432.6 2649.89   439.2 2651.53   455.9 2650.46   469.4 2652.69   491.8 2651.75
   507.6 2656.28   522.5 2657.77   531.4 2661.17   586.1 2697.02   666.8 2754.02
   726.3 2789.27   741.7 2800.06   747.6 2802.26   774.5  2822.7   819.3 2853.72
#Mann= 3 ,-1 , 0
       0      .1       0     386    .045       0   432.6      .1       0
Bank Sta=386,432.6
XS Rating Curve= 0 ,0
Exp/Cntr=0.3,0.1

Type RM Length L Ch R = 1 ,24720   ,455.8,450,443.3
XS GIS Cut Line= 3
     2374765.091      597284.111     2374571.942      596923.024
     2374378.793      596561.938
#Sta/Elev= 30
       0 2891.93    24.1 2878.44    61.7 2855.03    98.3 2834.76   140.7 2807.74
   225.5 2749.72   255.4 2727.93   280.4 2711.73   318.8  2690.2   337.1 2678.15
   377.6  2646.4     387 2640.31     396 2638.31   409.5 2638.25   427.8  2639.3
   464.1 2638.56   468.6 2638.87   477.7 2642.59   491.3 2643.34   523.1 2661.89
   536.7 2665.93     582 2689.02     658 2721.71   711.9    2751   725.8 2756.28
   740.8 2764.74   750.4 2768.01   772.6 2780.57   785.2 2784.87     819  2800.8
#Mann= 3 ,-1 , 0
       0      .1       0     387    .045       0   427.8      .1       0
Bank Sta=387,427.8
XS Rating Curve= 0 ,0
Exp/Cntr=0.3,0.1

Type RM Length L Ch R = 1 ,24270   ,409.4,419.7,439.9
XS GIS Cut Line= 3
2375218.21085263596954.756221052     2374935.946        596664.6
     2374639.611      596382.845
#Sta/Elev= 30
       0    2876    38.9  2861.3    50.4 2850.29     184 2778.31   195.1 2768.37
     240 2741.84   263.1 2723.92   278.8  2713.9   333.3 2668.92   362.5  2638.6
   384.2 2632.44   395.1 2630.19   418.2 2630.41   426.7  2632.5   434.1 2633.89
   469.1 2631.78   488.6 2639.39   508.7 2636.43   517.2 2637.79   527.9  2643.8
   551.2 2662.58     564 2674.87   588.6 2691.49   621.7 2709.38   633.2  2713.5
   664.3 2732.09   732.2 2764.68   760.5 2774.82   778.8 2783.53   813.7 2794.28
#Mann= 3 ,-1 , 0
       0      .1       0   384.2    .045       0   426.7      .1       0
#XS Ineff= 2 , 0
                          488.94         2644.57
Permanent Ineff=
       F       F
Bank Sta=384.2,426.7
XS Rating Curve= 0 ,0
Exp/Cntr=0.3,0.1

Type RM Length L Ch R = 1 ,23851   ,477.2,480.3,486.2
XS GIS Cut Line= 3
2375285.54991228596931.8956912282375293.04191228596483.127691228
2375308.29991228596080.967691228
#Sta/Elev= 30
       0 2862.15      33 2846.69    37.6  2842.8      49 2828.75      57 2821.73
     117 2781.47     133 2772.45     149 2755.88     241 2686.62     293 2649.37
   325.1 2629.95   337.1 2626.35   353.1 2624.93   369.1 2627.73   405.1 2625.82
   417.1 2623.68   438.62623.973   449.1 2622.69   473.8 2624.04   477.1 2625.52
     497 2643.01   521.1  2667.6   529.1 2677.16   574.1 2711.39   649.2 2762.22
   681.2 2781.86   693.7 2787.56   709.4 2798.96   757.3 2828.95   851.3 2895.26
#Mann= 3 ,-1 , 0
       0      .1       0   438.6    .045       0   473.8      .1       0
Bank Sta=438.6,473.8
XS Rating Curve= 0 ,0
Exp/Cntr=0.3,0.1

Type RM Length L Ch R = 1 ,23370   ,447.9,449.4,451.8
XS GIS Cut Line= 3
     2375583.503      597045.485     2375722.744      596660.384
     2375861.985      596275.284
#Sta/Elev= 30
       0 2862.99      41 2840.63   104.5 2808.87   134.6 2791.87   151.4  2777.6
   245.1 2719.62   334.5 2658.35   368.6 2631.27   389.8 2612.23   394.1 2610.91
   397.7 2611.45   413.8 2609.65   429.4 2610.15   436.6 2612.03   445.1 2616.09
   491.9 2613.62   508.9 2613.72   517.4 2616.05   530.2  2626.9   541.9 2634.56
   551.2 2642.82   572.7 2658.86     628 2698.06   636.5 2701.03   674.8 2724.87
   718.5 2746.12   768.4  2777.9   794.9 2797.46   806.7 2804.77     819 2815.12
#Mann= 3 ,-1 , 0
       0      .1       0   397.7    .045       0   436.6      .1       0
Bank Sta=397.7,436.6
XS Rating Curve= 0 ,0
Exp/Cntr=0.3,0.1

Type RM Length L Ch R = 1 ,22921   ,460.8,449.5,440.4
XS GIS Cut Line= 3
     2375962.575      597200.3052376229.82341755596638.942084207
      2376205.71      596410.536
#Sta/Elev= 30
       0  2846.1    41.4 2822.47    97.2  2782.8   134.5 2761.18   161.1 2743.37
   214.3 2714.58   307.2 2657.38   338.3 2640.42   352.3  2630.8   372.6 2610.27
   381.9 2604.24     387 2602.25   400.4  2601.6     418 2602.16   425.4 2604.45
   435.7 2607.45   457.9 2607.14   466.7  2605.1     480 2606.81   506.6 2602.18
     542 2600.07   547.4 2602.16   559.4 2620.82   571.4 2632.69   625.8 2673.97
   637.9 2680.31   649.9 2689.45   722.3 2728.53   770.6 2750.51   851.4  2795.7
#Mann= 3 ,-1 , 0
       0      .1       0   381.9    .045       0   425.4      .1       0
Bank Sta=381.9,425.4
XS Rating Curve= 0 ,0
Exp/Cntr=0.3,0.1

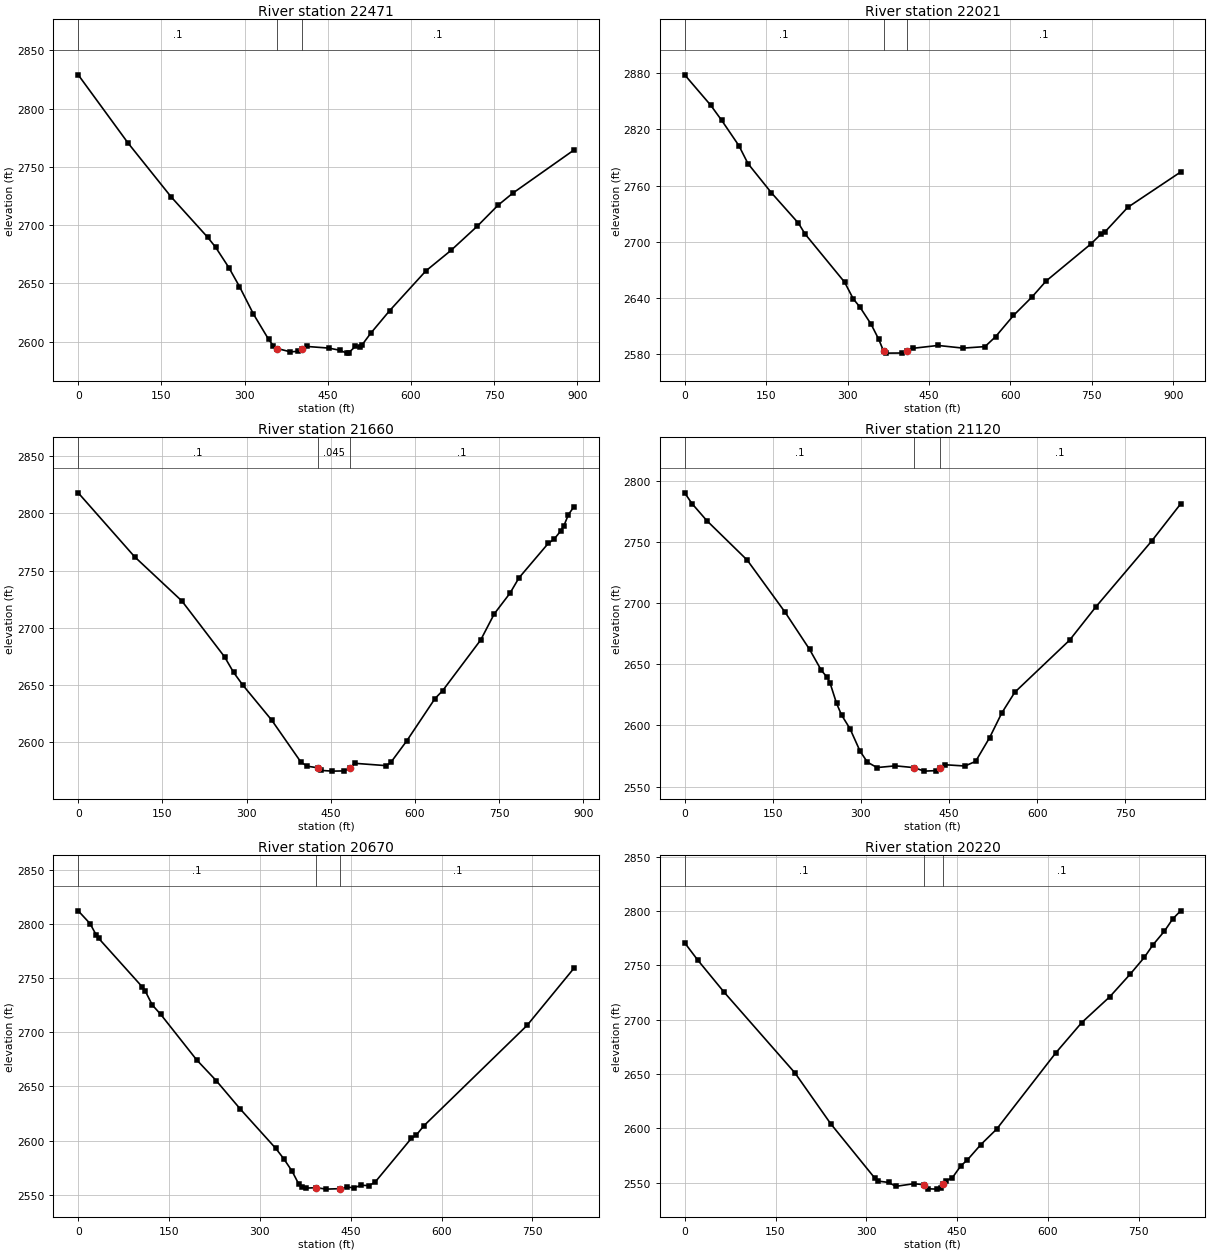
Type RM Length L Ch R = 1 ,22471   ,479.9,451,418.6
XS GIS Cut Line= 3
     2376586.362      597278.4632376574.02453684596740.192407015
2376341.54054386 596470.95117544
#Sta/Elev= 30
       0 2828.91      90 2770.29   167.6 2724.14   233.4  2689.5   247.6 2681.04
   271.6  2663.5   290.7 2647.27     316 2623.55   343.4 2601.81   351.7 2596.53
   359.1 2594.05   382.5 2591.21   395.7 2591.64   403.7 2593.81   411.7 2595.85
   451.7 2594.43   471.7 2592.59   483.7 2590.11   487.7 2590.55   499.7  2595.8
   507.7 2595.47   511.6 2597.09   527.2 2607.08   561.5 2626.57   626.7 2660.63
     672 2678.24   719.8 2699.18   756.8 2716.99   783.2 2727.28   894.1 2764.51
#Mann= 3 ,-1 , 0
       0      .1       0   359.1    .045       0   403.7      .1       0
Bank Sta=359.1,403.7
XS Rating Curve= 0 ,0
Exp/Cntr=0.3,0.1

Type RM Length L Ch R = 1 ,22021   ,362,360.6,355.7
XS GIS Cut Line= 3
2377266.12992632596668.7342140342376658.75068771596580.106603508
2376427.54400702596389.317557896
#Sta/Elev= 30
       0 2878.07    47.9 2845.69    68.1  2829.6    99.9 2802.54   116.6 2783.43
   159.8 2752.31   209.6  2719.9   221.7 2708.45   294.5  2657.1   310.6 2639.22
   322.8 2630.51   343.3 2612.31   357.4 2596.23   366.3 2583.67   371.3 2581.38
   399.6  2581.5   408.9 2583.68   419.8 2586.48   466.7 2589.56   512.8 2586.72
   553.2 2588.33   572.6 2598.83   605.7 2621.53   640.3 2641.55   665.8 2658.26
   747.7 2697.46   766.6 2708.05   774.6 2710.83   816.1 2736.75   913.6 2774.44
#Mann= 3 ,-1 , 0
       0      .1       0   366.3    .045       0   408.9      .1       0
Bank Sta=366.3,408.9
XS Rating Curve= 0 ,0
Exp/Cntr=0.3,0.1

Type RM Length L Ch R = 1 ,21660   ,510.8,539.5,560.9
XS GIS Cut Line= 2
2377295.27200702 596244.331228072376412.47538246596277.576484212
#Sta/Elev= 30
       0 2818.03   100.6 2762.04   184.7 2723.41   260.7 2674.57   276.7 2661.02
   292.7 2650.18   344.8 2619.12   396.8 2582.44     408 2578.92   426.3 2577.57
   432.8 2575.21   452.8 2574.61   472.9 2574.79   484.5 2577.37   492.9 2581.44
   548.9 2579.39   556.9 2582.26   585.5 2601.28   635.6 2638.13     649  2644.9
     717 2689.38   741.1 2712.17   769.1 2730.24   785.1 2743.65   837.1 2773.71
   847.8 2777.56   859.4 2784.65   865.1 2789.17   873.1 2798.93   883.4 2806.07
#Mann= 3 ,-1 , 0
       0      .1       0   426.3    .045       0   484.5      .1       0
Bank Sta=426.3,484.5
XS Rating Curve= 0 ,0
Exp/Cntr=0.3,0.1

Type RM Length L Ch R = 1 ,21120   ,450.3,450,448.2
XS GIS Cut Line= 3
 2377281.8944421596168.346852632     2377040.384      595829.405
2376808.24350877595469.716698246
#Sta/Elev= 30
       0 2790.38    12.3 2781.64    37.7 2767.61   106.5  2735.3   170.9  2692.7
   212.7 2662.21   232.6 2645.13   242.5 2639.44   247.4 2634.87   258.6 2618.05
     267 2608.62   281.5 2597.28   298.7 2578.84   311.2 2569.93   327.4 2565.55
   358.9 2566.96   390.5 2565.49   407.7 2562.63   427.9 2563.03     434 2564.94
     443 2567.86   477.1 2566.82   495.3  2570.6   519.2 2590.09   539.9 2610.26
     562 2627.18   655.3 2669.81   699.8 2696.93   795.3 2751.09   844.3  2781.3
#Mann= 3 ,-1 , 0
       0      .1       0   390.5    .045       0     434      .1       0
Bank Sta=390.5,434
XS Rating Curve= 0 ,0
Exp/Cntr=0.3,0.1

Type RM Length L Ch R = 1 ,20670   ,454.5,450,443.8
XS GIS Cut Line= 3
     2377658.466      595902.644     2377407.736      595578.867
      2377158.92       595253.63
#Sta/Elev= 30
       0 2811.96    19.6 2800.15      30  2789.4    33.8 2786.57   105.9 2741.73
     111 2737.67   122.2 2725.22   136.3 2716.44   195.5 2674.57   227.7 2655.48
   267.8 2629.05   326.2  2592.9   339.3 2583.44   353.2 2571.86   363.9 2560.28
     369  2557.6     376 2556.25   393.1 2556.66   409.5 2555.31     433 2555.76
   444.7 2557.26   454.8 2556.46   467.3 2558.88     480 2558.58   490.1 2561.64
     550 2602.03   558.6 2605.34   570.6  2613.6   741.2 2706.28     819 2759.25
#Mann= 3 ,-1 , 0
       0      .1       0   393.1    .045       0     433      .1       0
Bank Sta=393.1,433
XS Rating Curve= 0 ,0
Exp/Cntr=0.3,0.1

Type RM Length L Ch R = 1 ,20220   ,452.3,450,447.7
XS GIS Cut Line= 3
     2378059.651      595499.726     2377725.094      595263.587
     2377390.538      595027.447
#Sta/Elev= 30
       0  2770.7    21.3 2754.99    64.8 2725.47   182.3 2650.81     241 2604.28
   314.1 2554.03   319.8 2551.37   337.1 2550.13   348.5 2546.54   378.1 2548.96
   394.5 2548.18   402.6 2544.29   417.3    2544   423.2 2545.04   427.1 2548.34
   431.5 2551.72   441.8 2554.32   456.4 2565.69   466.3 2570.52   489.2 2585.07
   515.2 2599.22   613.1 2669.58   655.6 2697.21     702 2721.03   735.5  2741.7
     759 2757.23   773.3  2768.8   792.2 2781.41   806.1 2792.75     819 2800.13
#Mann= 3 ,-1 , 0
       0      .1       0   394.5    .045       0   427.1      .1       0
Bank Sta=394.5,427.1
XS Rating Curve= 0 ,0
Exp/Cntr=0.3,0.1

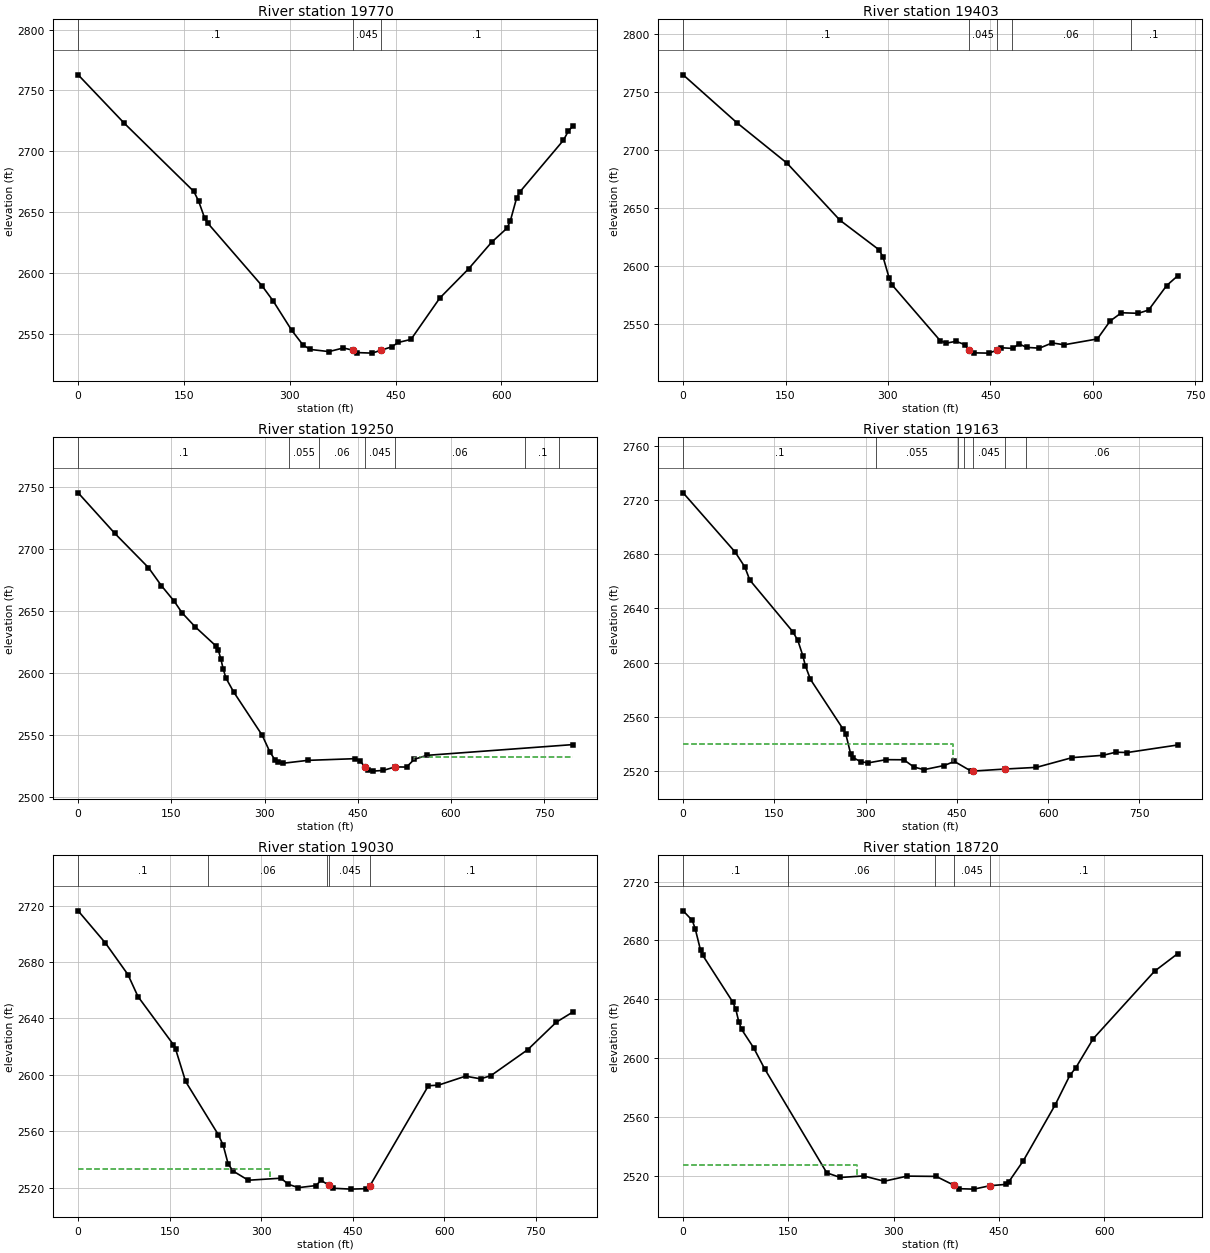
Type RM Length L Ch R = 1 ,19770   ,365.9,367.2,365
XS GIS Cut Line= 3
     2378277.691       595025.46     2377904.873      594853.918
2377648.61399895594716.668596843
#Sta/Elev= 30
       0  2762.8    64.9 2723.27     164 2666.89   170.6 2659.18   179.4 2644.88
   183.8 2640.78   260.5 2589.43   276.2 2577.05   302.7 2552.75   318.8 2540.59
   329.1 2536.99   355.5 2535.22   375.9  2538.2   388.9 2536.45   395.1 2534.41
   416.8 2533.96     429 2536.29   444.6 2539.16   453.6  2542.7   471.8 2545.26
   512.6 2579.22   553.5  2603.3   586.2 2625.22   607.9  2636.7   612.5 2642.47
   621.5 2661.47   626.1 2666.53   687.9 2709.02   694.9 2716.57   701.1  2720.6
#Mann= 3 ,-1 , 0
       0      .1       0   388.9    .045       0     429      .1       0
Bank Sta=388.9,429
XS Rating Curve= 0 ,0
Exp/Cntr=0.3,0.1

Type RM Length L Ch R = 1 ,19403   ,154.9,153.5,145.8
XS GIS Cut Line= 3
     2378402.185      594845.8662378250.12614106594615.585311579
2377844.08531832 594424.71127358
#Sta/Elev= 30
       0 2764.56    78.8  2723.3   152.2 2688.52   229.8 2639.38     287 2613.98
     293 2607.52   301.8 2589.68   306.2 2583.66   376.9 2535.55   385.8 2533.67
   399.8 2535.22   412.3 2532.42   418.6 2528.06   425.5 2525.29   447.6 2525.05
   459.4 2527.45   465.3 2529.72     483 2529.09   491.8 2533.03   503.2 2529.98
     522 2529.32   540.6 2533.83   558.1 2532.23   606.8 2537.26   625.5 2552.65
   642.1 2559.79   666.9 2559.32   681.9 2562.15   708.4 2583.23   724.6 2591.63
#Mann= 5 ,-1 , 0
       0      .1       0   418.6    .045       0   459.4      .1       0
  481.26     .06       0  655.61      .1       0
Bank Sta=418.6,459.4
XS Rating Curve= 0 ,0
Exp/Cntr=0.5,0.3

Type RM Length L Ch R = 1 ,19250   ,63.1,64.4,63.9
XS GIS Cut Line= 3
     2378430.235       594811.762378335.02845404594476.783293058
2377906.95923509594345.904600004
#Sta/Elev= 30
       0 2745.28    59.1 2712.52   113.2 2684.94     134 2670.39   154.8 2657.71
   167.2 2648.53     188  2637.4   221.3 2621.99   225.5 2618.45   229.6 2611.36
   233.4 2603.23   237.9 2595.82   250.4 2584.59   296.2 2549.78   308.6 2536.27
   316.9 2529.84   321.1 2527.88   329.4 2527.19   369.5 2529.55   444.7  2530.9
   453.1 2529.41   461.5 2524.23   465.7 2521.93     474 2520.87   490.8 2521.43
   510.2 2524.29   528.4 2524.14   540.9 2530.42   561.4  2533.6   795.9 2542.26
#Mann= 7 ,-1 , 0
       0      .1       0   338.9    .055       0  387.18     .06       0
   461.5    .045       0   510.2     .06       0  719.29      .1       0
  774.56     .06       0
#XS Ineff= 2 , 0
             446    2530     540            2532
Permanent Ineff=
       F       F
Bank Sta=461.5,510.2
XS Rating Curve= 0 ,0
Exp/Cntr=0.5,0.3

Type RM Length L Ch R = 1 ,19163   ,118.8,133,165.4
XS GIS Cut Line= 3
     2378462.254      594784.5012378355.66712686594400.375646555
2377961.94124136594270.798892114
#Sta/Elev= 30
       0 2725.55    85.4 2681.78   101.3 2670.79   109.6    2661   180.2 2622.85
   188.5 2616.39   196.8    2605   200.9 2597.67   209.2 2587.61   263.2  2550.6
   267.4 2547.05   275.6  2532.1   279.8  2529.6   292.3 2526.54   304.7 2525.84
   333.8 2528.17   362.8 2528.09   379.4  2522.7     396 2520.78   429.1 2523.85
   445.9 2526.86   473.4 2519.69   476.42519.719   529.12521.233   580.7 2522.47
   639.6 2529.69   690.2 2531.39   711.2 2533.68   730.1 2533.45   813.1 2539.03
#Mann= 7 ,-1 , 0
       0      .1       0  316.92    .055       0  452.59     .06       0
  460.99    .055       0   476.4    .045       0   529.1    .055       0
  563.03     .06       0
#XS Ineff= 2 , 0
          444.24 2539.89
Permanent Ineff=
       F       F
Bank Sta=476.4,529.1
XS Rating Curve= 0 ,0
Exp/Cntr=0.5,0.3

Type RM Length L Ch R = 1 ,19030   ,291.7,309.6,322.5
XS GIS Cut Line= 3
2378493.85308809594774.3113275992378363.05192341594215.562874147
2378186.75470146594057.748425462
#Sta/Elev= 30
       0  2716.3    44.6 2693.51    81.6 2671.07      98 2655.51     156 2621.44
   159.6 2618.34   176.1 2595.25   229.5 2557.62   237.7 2549.99   245.9 2536.57
   254.1 2531.63   278.8 2525.18   332.2 2526.62   344.5  2522.3   360.9 2519.91
   389.7  2521.4   397.9 2525.12   411.6 2521.48   418.4 2519.48   447.2 2518.87
   471.8  2519.2   477.8 2520.98   573.9  2592.2   590.4 2592.64   634.8    2599
   659.5 2597.11   676.3 2599.36   736.8 2617.82   783.6 2637.32   810.5 2644.47
#Mann= 5 ,-1 , 0
       0      .1       0   212.2     .06       0  407.82      .1       0
   411.6    .045       0   477.8      .1       0
#XS Ineff= 2 , 0
          315.05 2533.25
Permanent Ineff=
       F       F
Bank Sta=411.6,477.8
XS Rating Curve= 0 ,0
Exp/Cntr(USF)=0,0
Exp/Cntr=0.3,0.1

Type RM Length L Ch R = 1 ,18720   ,441.4,450,457.2
XS GIS Cut Line= 3
     2378589.061      594779.475     2378693.766      594383.566
2378770.96928835594098.513447816
#Sta/Elev= 30
       0 2700.16      13 2693.65    17.2 2687.95    24.8 2673.34      28 2669.85
    70.9 2638.01    75.1 2633.06    79.2 2624.86    83.4 2619.46   100.5 2606.97
   116.1 2592.75   204.7 2521.97     224 2518.82   257.2 2519.87   286.5 2516.27
   319.2 2519.75   360.6 2519.55   386.6 2513.38   393.7 2511.18   414.4  2510.9
     437 2513.21   459.8 2514.12   464.1 2515.92   484.8 2530.25   530.4 2568.44
   551.1 2588.33   559.4 2593.33   584.3 2613.16   671.7 2659.08   704.8 2671.07
#Mann= 5 ,-1 , 0
       0      .1       0  149.17     .06       0     359      .1       0
   386.6    .045       0     437      .1       0
#XS Ineff= 2 , 0
          247.09 2527.48
Permanent Ineff=
       F       F
Bank Sta=386.6,437
XS Rating Curve= 0 ,0
Exp/Cntr=0.3,0.1

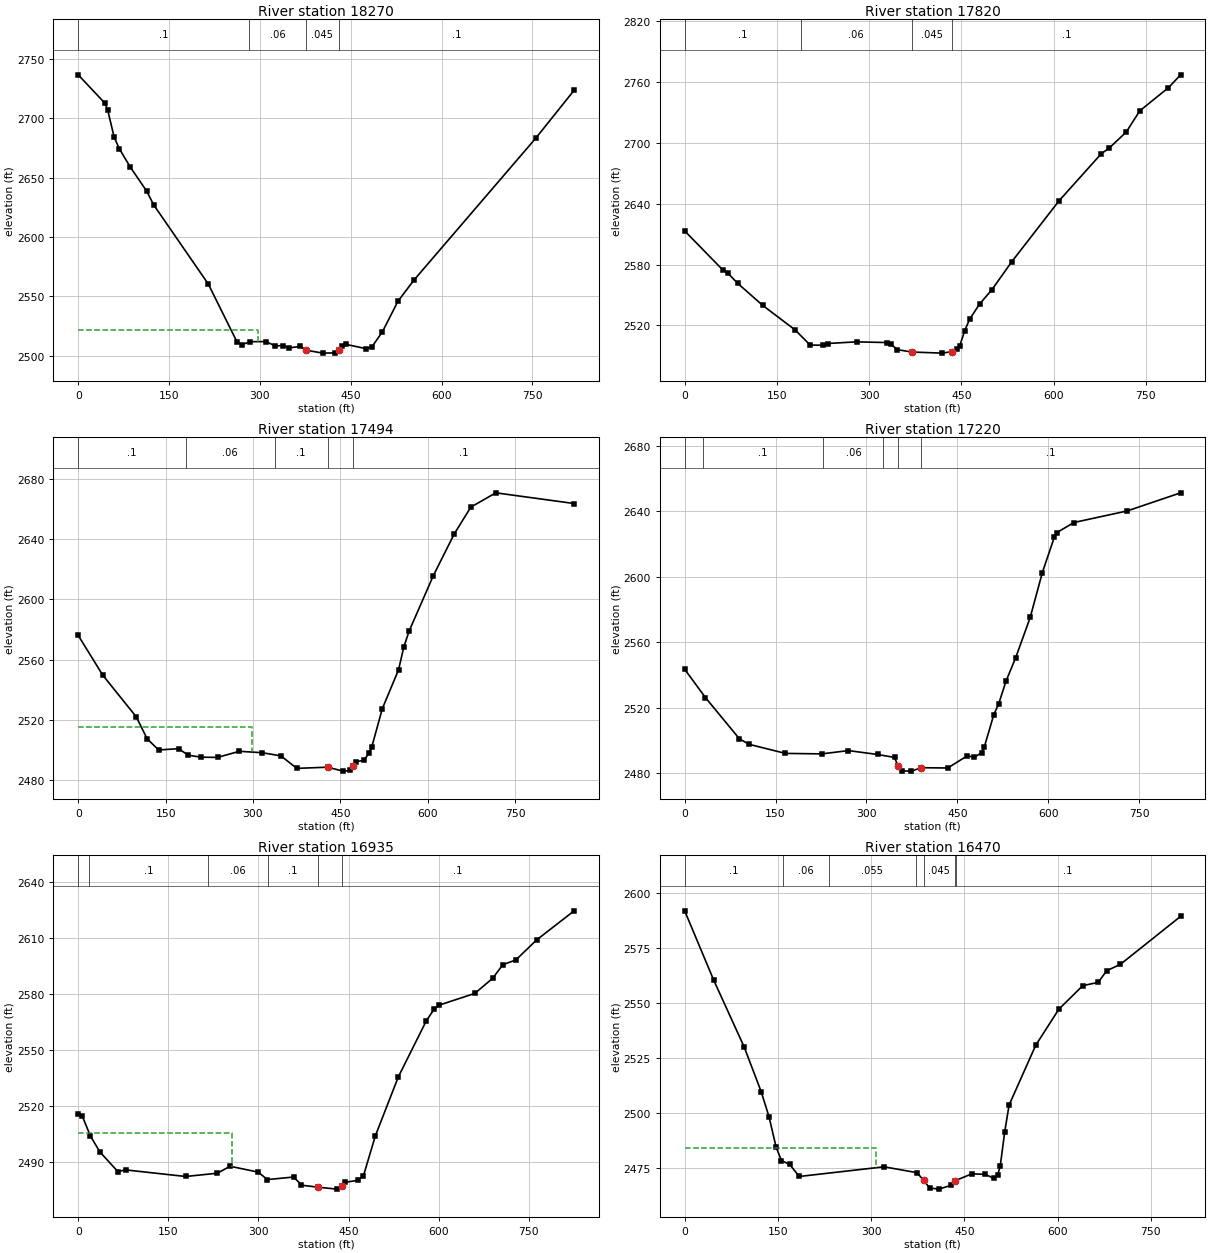
Type RM Length L Ch R = 1 ,18270   ,463.4,450,440.5
XS GIS Cut Line= 3
     2378881.995      594912.044     2379102.236      594566.814
     2379322.478      594221.584
#Sta/Elev= 30
       0 2736.73    44.1 2712.83    48.8 2706.83    59.3 2684.27    67.8 2674.56
    85.4 2659.42     113 2638.74   124.7 2627.09   214.9 2560.35   262.3 2511.53
   270.8 2509.43     284 2511.82   309.8  2511.9   325.8 2508.23   338.2 2508.59
   347.7 2506.51   366.7 2507.86   376.2 2504.68     404 2502.18   423.6 2502.38
   430.1  2504.9   435.9 2508.47   441.7 2509.61   475.8 2505.89   485.3 2507.65
   502.5  2520.3     528 2545.89   554.6 2563.83   755.8 2683.45     819 2723.76
#Mann= 4 ,-1 , 0
       0      .1       0  282.83     .06       0   376.2    .045       0
   430.1      .1       0
#XS Ineff= 2 , 0
          297.44 2521.38
Permanent Ineff=
       F       F
Bank Sta=376.2,430.1
XS Rating Curve= 0 ,0
Exp/Cntr=0.3,0.1

Type RM Length L Ch R = 1 ,17820   ,320.8,326.9,336.9
XS GIS Cut Line= 3
     2379463.248      595084.178     2379529.309      594679.431
 2379586.4841821594287.276233685
#Sta/Elev= 30
       0 2613.35    62.1 2574.72    70.2  2571.6    86.4 2561.49   126.9 2539.81
   179.6  2515.6     204 2500.69   224.2 2500.49   232.3 2502.22   279.4 2503.85
   329.6 2503.14   335.2 2501.66   345.8 2496.13   369.4  2493.8   418.5 2492.72
   434.9 2494.21     443 2496.32     447 2499.43   455.1 2514.48   463.2 2526.07
   479.4 2541.03   499.6 2555.38   531.9 2582.98   608.7 2643.04   677.4 2689.52
   689.6 2694.75   717.9 2710.81   739.9 2731.78   786.6  2754.7   806.4 2767.37
#Mann= 4 ,-1 , 0
       0      .1       0  188.36     .06       0   369.4    .045       0
   434.9      .1       0
Bank Sta=369.4,434.9
XS Rating Curve= 0 ,0
Exp/Cntr=0.3,0.1

Type RM Length L Ch R = 1 ,17494   ,279.4,273.1,259.9
XS GIS Cut Line= 3
2379562.79404483595098.4042475622379777.82389668594877.145873295
2380044.86769786594404.426939571
#Sta/Elev= 30
       0 2576.05    42.1 2549.68    99.7 2521.93   118.4  2507.3   138.2 2499.93
   172.2 2500.81     189 2496.47   211.3 2495.13   239.2 2495.02   276.8 2499.06
   315.7 2498.13   347.9 2496.04   375.4 2487.72   428.2 2488.51   454.7 2485.89
   467.3 2486.31   471.9 2489.11   476.5 2492.18   490.3 2493.01   499.5  2497.9
   504.1 2502.04   522.2 2527.48     550 2553.19   559.2 2568.63   568.4 2579.17
   609.7 2615.75   645.5 2643.39   674.1 2661.28     717 2670.78   851.5 2663.67
#Mann= 5 ,-1 , 0
       0      .1       0  184.28     .06       0  337.56      .1       0
   428.2    .045       0   471.9      .1       0
#XS Ineff= 2 , 0
          298.77 2515.52
Permanent Ineff=
       F       F
Bank Sta=428.2,471.9
XS Rating Curve= 0 ,0
Exp/Cntr=0.3,0.1

Type RM Length L Ch R = 1 ,17220   ,290.3,285.4,276.4
XS GIS Cut Line= 3
2380074.55433528595233.122791422     2380085.223      594864.502
     2380093.774       594414.61
#Sta/Elev= 30
       0 2543.48    34.2 2526.24    90.3 2501.06   106.3 2497.67   166.3 2492.13
   226.3 2491.83   270.3 2493.85   318.4 2491.47   346.4 2489.68   352.4 2484.23
   352.4 2484.22   358.4 2481.43   374.4 2481.31   390.4 2483.39   434.4 2483.23
   466.4 2490.64   478.4 2489.83   490.4 2492.58   494.4 2495.79   510.4 2515.85
   518.4  2522.4   530.4 2536.19   546.4 2550.51   570.4 2575.11   590.4 2602.47
   610.4  2624.3   614.4 2626.89   642.4 2633.04   730.5 2640.12   818.7 2651.17
#Mann= 6 ,-1 , 0
       0     .06       0    30.5      .1       0  228.87     .06       0
  328.06      .1       0   352.4    .045       0   390.4      .1       0
Bank Sta=352.4,390.4
XS Rating Curve= 0 ,0
Exp/Cntr=0.3,0.1

Type RM Length L Ch R = 1 ,16935   ,477.3,464.6,446.5
XS GIS Cut Line= 2
     2380482.483      595157.228     2380206.849       594379.05
#Sta/Elev= 30
       0 2515.96     6.7 2514.67    20.4 2503.91    36.1 2495.43    66.1 2484.89
    78.9 2485.81   178.9 2482.28   231.6 2484.03   252.8 2487.76   299.5 2484.63
     315 2480.63   358.9    2482   371.7 2477.62   398.5 2476.58   430.5 2475.51
   439.6 2477.13   443.8 2479.12     465 2480.21   474.8 2482.61   494.7 2504.11
   532.9 2535.64   579.6 2565.76   592.3 2571.84   600.8 2574.09   660.2 2580.36
   689.9 2588.45   706.9 2595.73   728.6  2598.3   763.1 2609.02   825.6 2624.61
#Mann= 6 ,-1 , 0
       0     .06       0   17.97      .1       0  216.45     .06       0
   315.7      .1       0   398.5    .045       0   439.6      .1       0
#XS Ineff= 2 , 0
          255.65 2505.84
Permanent Ineff=
       F       F
Bank Sta=398.5,439.6
XS Rating Curve= 0 ,0
Exp/Cntr=0.3,0.1

Type RM Length L Ch R = 1 ,16470   ,528.1,520.1,510.7
XS GIS Cut Line= 3
     2381084.708      594813.851      2380751.99      594578.829
2380428.26301841594360.727039854
#Sta/Elev= 30
       0  2591.9    46.7 2560.38    95.4  2530.2     123 2509.72   135.6 2498.34
     147 2484.54   155.6 2478.37   168.9 2476.59   184.3 2471.13   320.7 2475.53
   373.8 2472.85   384.4 2469.31   394.2  2465.9   408.9 2465.38   428.1 2467.09
   434.1  2469.1   461.9 2472.34   483.1 2472.11   497.5 2470.28   503.3  2471.7
   507.5 2475.72   514.8  2491.5   521.8 2503.62   564.7 2530.81   601.8 2547.16
   640.4 2557.91     665 2559.35   678.9 2564.68   700.8 2567.56   797.7 2589.39
#Mann= 7 ,-1 , 0
       0      .1       0  158.17     .06       0  231.42    .055       0
  371.64     .06       0   384.4    .045       0   434.1     .06       0
   435.8      .1       0
#XS Ineff= 2 , 0
          307.19 2483.94
Permanent Ineff=
       F       F
Bank Sta=384.4,434.1
XS Rating Curve= 0 ,0
Exp/Cntr=0.3,0.1

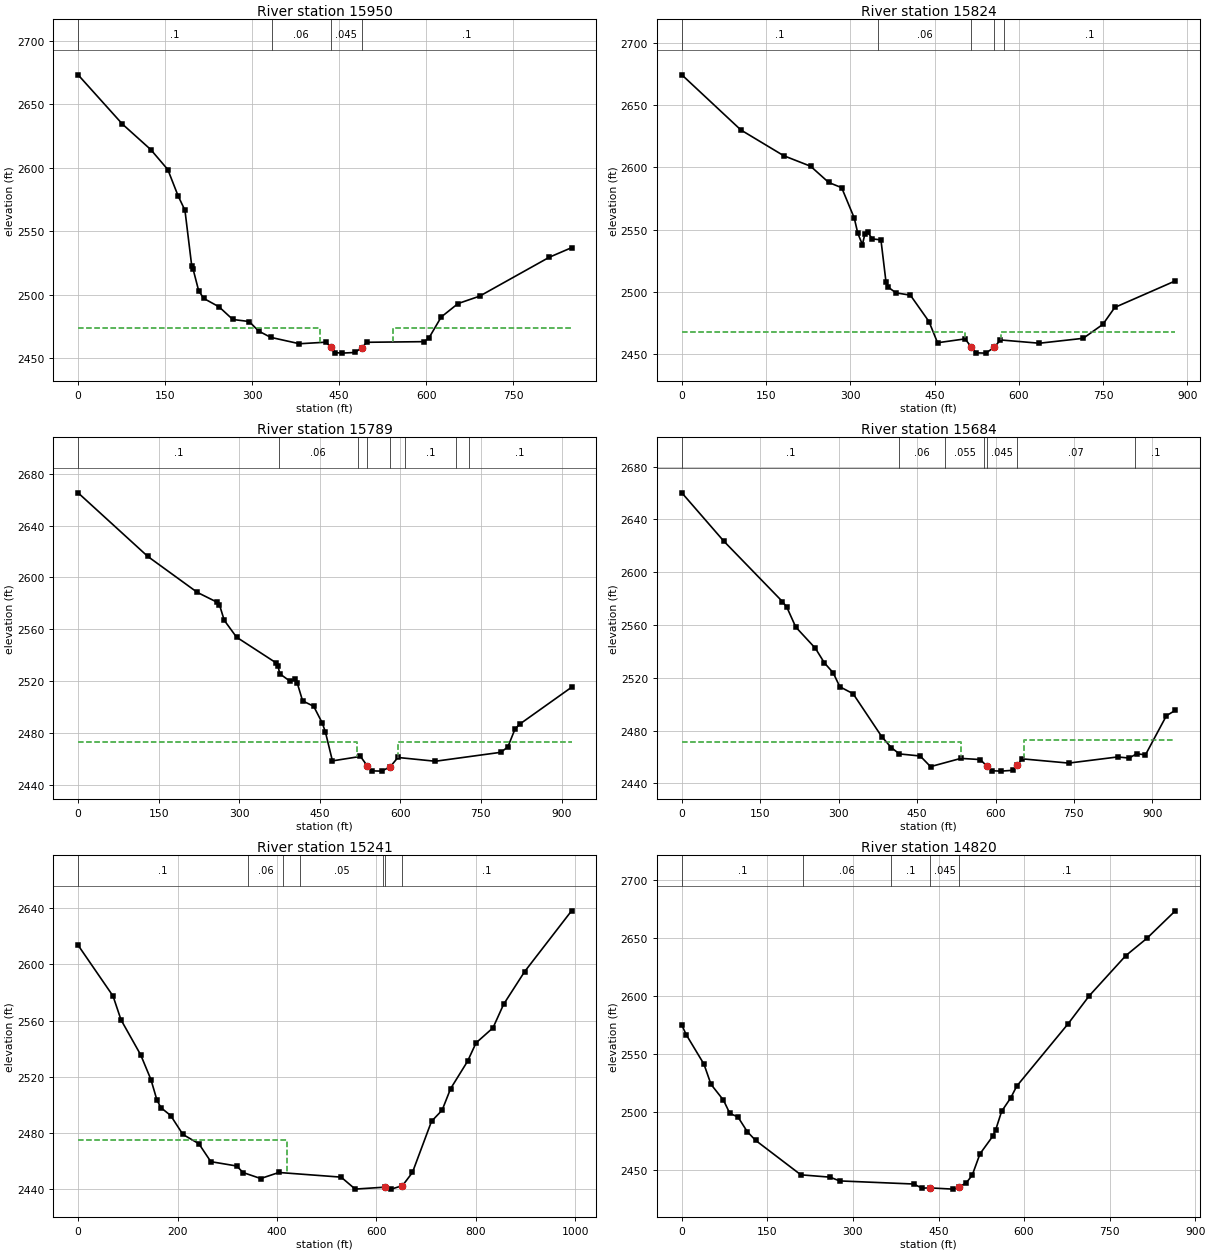
Type RM Length L Ch R = 1 ,15950   ,124.5,126.8,129.7
XS GIS Cut Line= 3
     2381299.769      594357.8682381102.16578306594144.086075859
2380561.71908663593999.136406103
#Sta/Elev= 30
       0 2673.19    76.4 2634.42   125.3 2614.34   154.7  2598.6   172.4 2577.95
   184.2 2566.62     196 2522.46   198.1 2520.57   207.8 2503.39   216.5 2497.28
   243.1 2490.58   266.7 2480.66   294.9 2479.07   311.2 2471.59   331.9 2466.62
   381.6 2461.57   427.2  2462.8   435.5 2459.05   443.7 2454.58   454.9 2454.19
   476.9  2454.7   489.3 2458.47   497.6 2462.72     597 2463.22   605.3 2466.48
     626 2482.62     655 2493.19   692.2 2499.02   812.3 2529.64   850.7 2537.16
#Mann= 4 ,-1 , 0
       0      .1       0  333.58     .06       0   435.5    .045       0
   489.3      .1       0
#XS Ineff= 2 , 0
          417.86 2474.16  543.12         2474.16
Permanent Ineff=
       F       F
Bank Sta=435.5,489.3
XS Rating Curve= 0 ,0
Exp/Cntr=0.5,0.3

Type RM Length L Ch R = 1 ,15824   ,21.4,21.9,22
XS GIS Cut Line= 3
2381311.55758236594353.6184860762381135.07620847594046.263284352
2380651.23963285593844.995200643
#Sta/Elev= 30
       0 2674.27   105.1 2629.99   181.3 2609.33   229.2 2600.87   261.4 2587.85
   284.5 2583.65   306.9 2559.29   313.2 2547.08   321.4 2537.92     326 2546.74
   330.6 2548.11     339 2542.53   354.4 2541.73   363.4 2507.92   367.8 2503.67
   380.8 2499.23   406.8 2497.33   439.9 2476.16   455.2 2459.13   504.1 2462.24
   515.1 2455.79   523.7 2451.03   541.1  2450.8   556.1 2455.47   567.1 2461.39
   636.4 2458.75   714.4 2462.69   749.4 2473.88   770.7 2487.51   878.4  2508.8
#Mann= 5 ,-1 , 0
       0      .1       0  349.49     .06       0   515.1    .045       0
   556.1     .05       0  573.49      .1       0
#XS Ineff= 2 , 0
          504.11 2468.01  568.47         2467.56
Permanent Ineff=
       F       F
Bank Sta=515.1,556.1
XS Rating Curve= 0 ,0
Exp/Cntr(USF)=0,0
Exp/Cntr=0.5,0.3

Type RM Length L Ch R = 1 ,15789   ,103,104.6,105
XS GIS Cut Line= 3
2381328.82872299 594345.953598582381149.90561478594017.304052929
2380649.86124006593801.880879189
#Sta/Elev= 30
       0  2665.3   129.8 2616.18   222.1 2588.41   258.5 2580.91   263.1 2578.98
   272.1 2566.89     295 2553.87   367.8 2534.26   372.4 2531.25   375.4 2525.64
   395.1 2519.71   403.8 2521.25   408.1 2518.34     418 2504.68   438.6 2500.52
   454.5 2487.66   460.4  2480.7   473.5 2458.36   525.7 2461.79   538.52454.464
   547.5 2450.65   564.9 2450.45   580.92453.683   595.4 2460.99   665.1 2458.08
     787 2464.98   800.1 2469.13   813.2 2482.73   821.9 2486.64   918.7 2515.19
#Mann= 8 ,-1 , 0
       0      .1       0  373.59     .06       0  520.22     .05       0
   537.5    .045       0   579.9     .05       0  609.53      .1       0
  703.55     .07       0  727.32      .1       0
#XS Ineff= 2 , 0
          520.11 2472.73  595.98         2473.19
Permanent Ineff=
       F       F
Bank Sta=538.5,580.9
XS Rating Curve= 0 ,0
Exp/Cntr=0.5,0.3

Type RM Length L Ch R = 1 ,15684   ,415,443.2,478.2
XS GIS Cut Line= 3
2381328.38812344594337.1138606182381191.29619754593931.958258186
2380727.38691258593705.511773444
#Sta/Elev= 30
       0 2660.18      80 2623.69   192.4 2577.79   200.8 2573.55   217.9 2558.49
   255.5 2542.38   272.6 2531.39   289.5 2523.82   302.2 2513.25   327.5 2508.03
   382.4 2475.47   400.6 2467.18   416.2 2462.38   455.9 2460.82   475.7 2452.76
   533.6 2458.99   570.8 2458.12   584.1  2452.9   593.4 2449.63   610.8 2449.35
   633.1 2449.99   641.3 2453.65   650.9 2458.66     740 2455.44   833.4 2460.08
   855.6 2459.27   870.1  2462.5   886.8 2461.69   926.9 2491.34   943.9 2495.39
#Mann= 7 ,-1 , 0
       0      .1       0  416.16     .06       0  502.81    .055       0
  578.45     .05       0   584.1    .045       0   641.3     .07       0
  867.58      .1       0
#XS Ineff= 2 , 0
          533.64 2471.74  654.71         2472.99
Permanent Ineff=
       F       F
Bank Sta=584.1,641.3
XS Rating Curve= 0 ,0
Exp/Cntr(USF)=0,0
Exp/Cntr=0.3,0.1

Type RM Length L Ch R = 1 ,15241   ,413.6,420.1,427.3
XS GIS Cut Line= 3
2381345.72089123594264.9165508782381312.74063493593869.910427649
2381519.46446316593310.683161404
#Sta/Elev= 30
       0 2613.54    70.3  2577.4    86.3 2560.52     126 2535.55   146.5 2518.06
   158.6 2503.49   166.6 2498.08   186.2 2492.49   210.8 2479.05   242.9 2472.46
     267  2459.7   319.1 2456.61   331.8 2451.97   367.3 2447.71   403.9 2452.01
   529.1  2448.7   557.4  2440.2   618.2 2441.61   629.9 2440.18   652.5 2442.66
   672.5    2452   710.9 2488.37   732.2 2496.27   749.3 2511.59   783.3 2530.98
   800.5 2544.11   834.6 2554.83   855.9 2571.52   898.2 2594.76   992.6 2637.97
#Mann= 7 ,-1 , 0
       0      .1       0   342.2     .06       0   411.6    .055       0
  446.16     .05       0  613.29      .1       0   618.2    .045       0
   652.5      .1       0
#XS Ineff= 2 , 0
          420.94 2475.28
Permanent Ineff=
       F       F
Bank Sta=618.2,652.5
XS Rating Curve= 0 ,0
Exp/Cntr=0.3,0.1

Type RM Length L Ch R = 1 ,14820   ,452.8,450,446.8
XS GIS Cut Line= 3
2381421.94111228 594240.87414035     2381728.393      593900.391
      2381995.25      593592.931
#Sta/Elev= 30
       0 2574.86     7.6 2566.71    38.8 2541.12    51.1 2523.69      73    2510
    84.1 2498.57    98.3 2495.52   114.8 2482.71   129.4 2475.21   208.7 2445.44
   259.7 2443.44   276.7 2440.18   406.3  2437.5   421.2 2433.96   435.3 2434.13
     475 2433.08   486.1 2434.99   498.3 2438.35     509 2444.99   522.7 2463.57
   544.8 2478.62   550.1 2484.09   560.7 2500.37   576.6 2511.96   587.2 2522.15
   677.2 2576.03   714.3 2600.25   778.4 2634.99   815.3 2649.91   865.2 2673.72
#Mann= 5 ,-1 , 0
       0      .1       0  212.48     .06       0  366.87      .1       0
   435.3    .045       0   486.1      .1       0
Bank Sta=435.3,486.1
XS Rating Curve= 0 ,0
Exp/Cntr=0.3,0.1