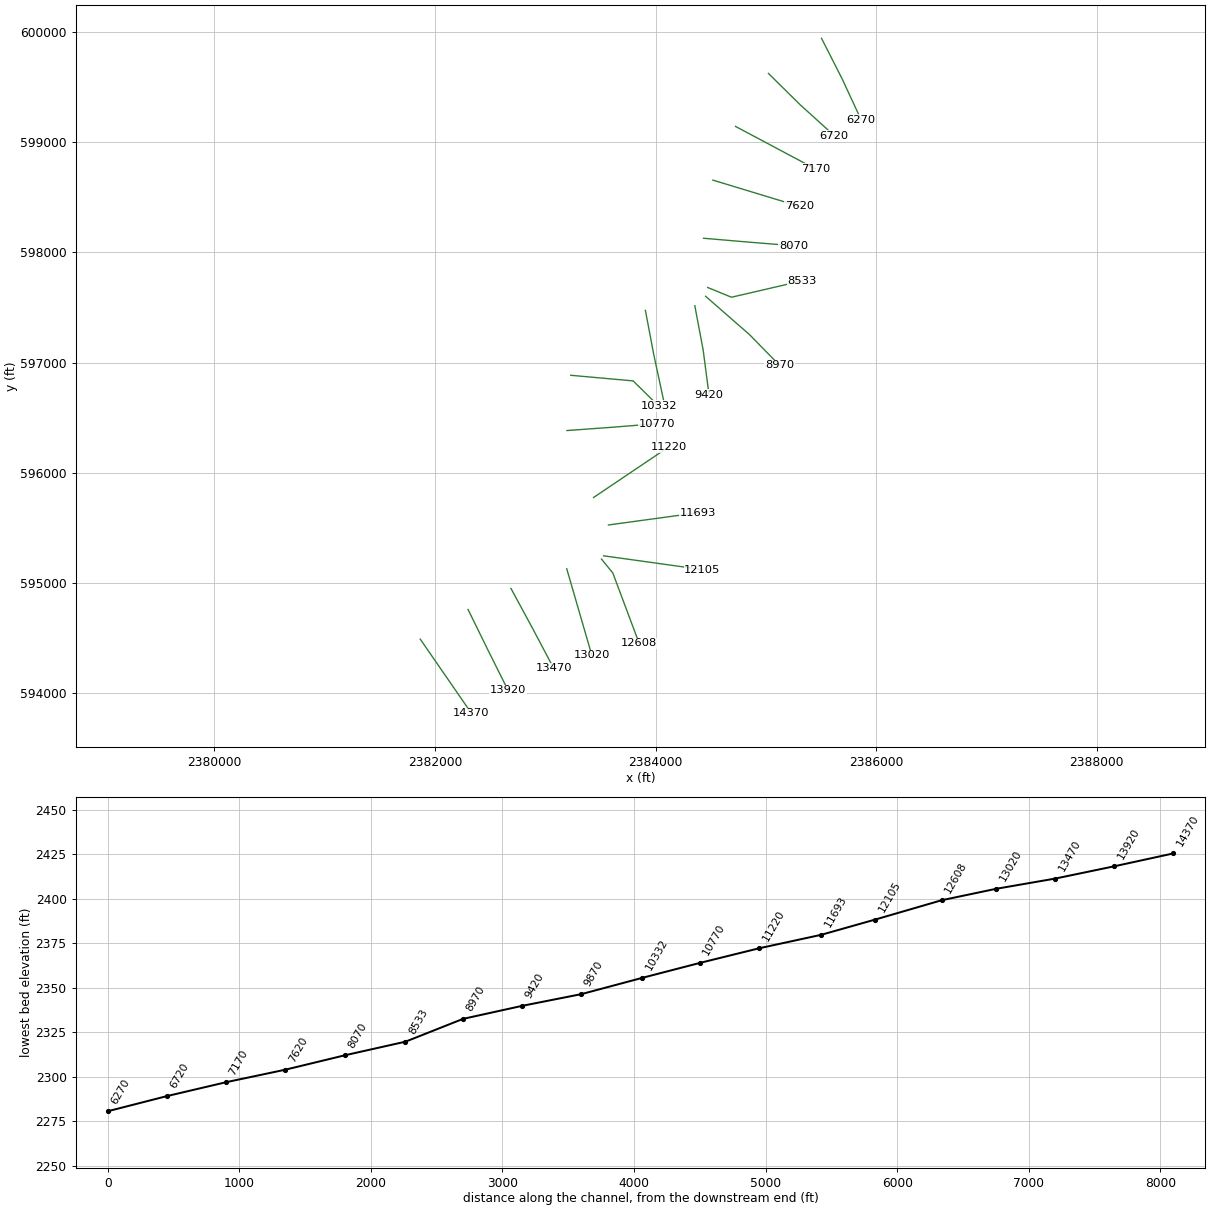
HEC-RAS study BIGRN.prj: BIGRN

--- BIGRN.g02 (geometry) --- (continued)

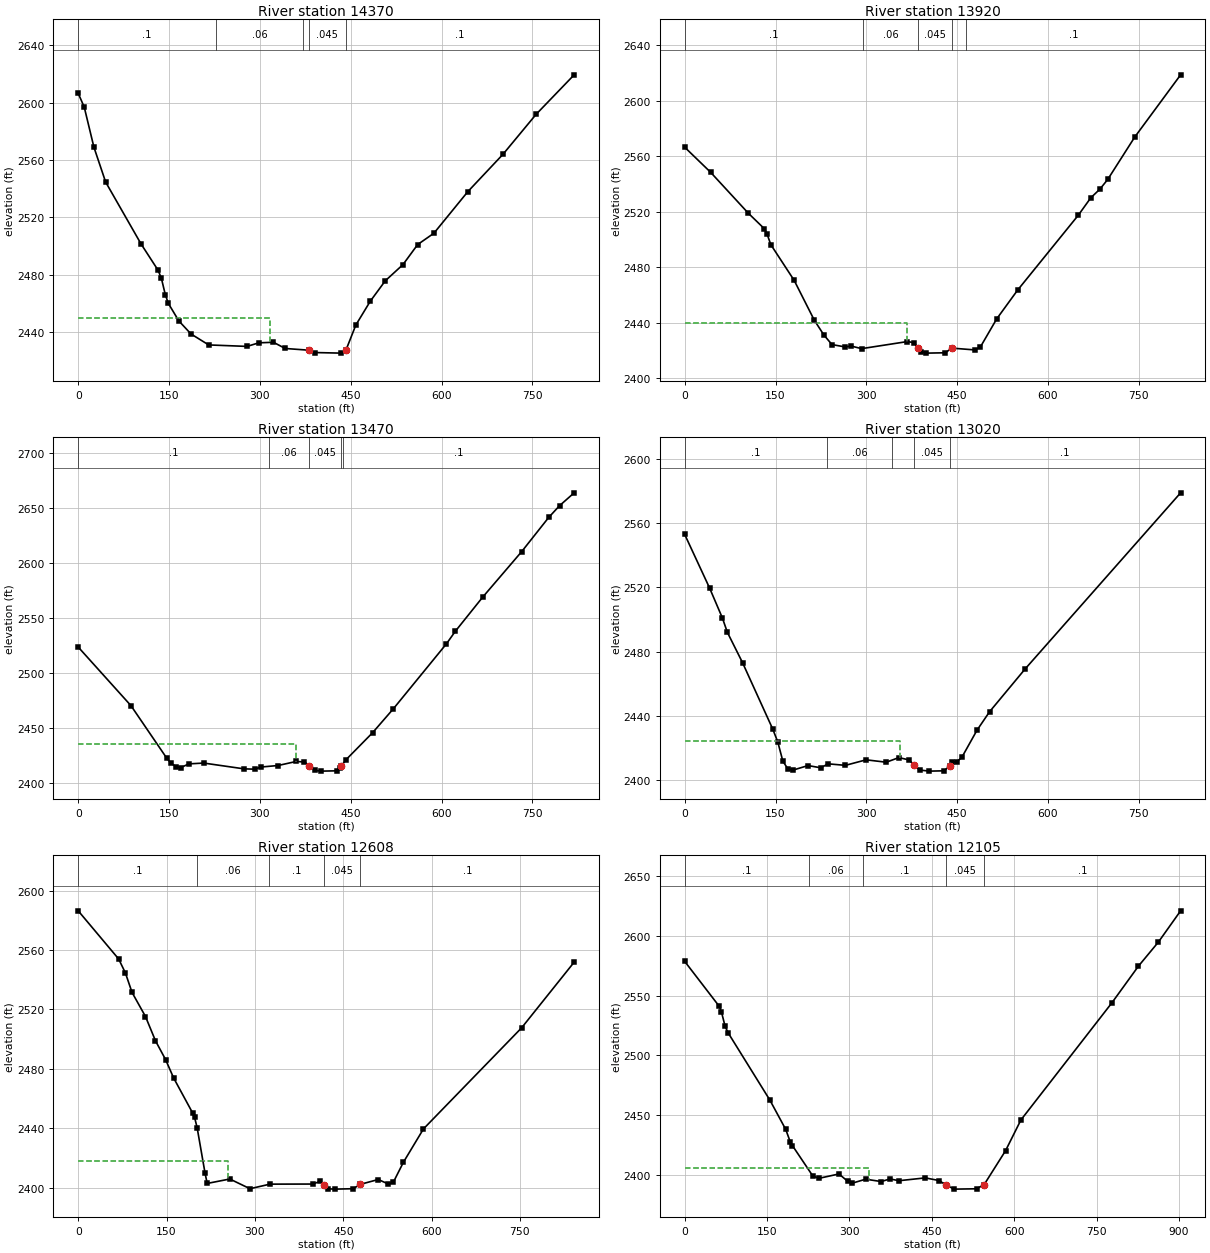
Type RM Length L Ch R = 1 ,14370   ,453.7,450,445.4
XS GIS Cut Line= 3
     2381865.066      594492.241     2382097.706      594155.241
     2382330.347      593818.242
#Sta/Elev= 30
       0 2606.62      10 2596.93    25.9 2569.09    45.3 2544.72   103.7 2501.59
   131.6 2483.39   137.3 2477.67   143.8 2466.21   148.8 2460.09   166.1 2447.89
   186.2 2438.75   215.5 2431.09   278.7 2430.06   298.4 2432.57   322.4 2432.93
   341.9 2428.61   380.8 2427.42   390.5 2425.78   434.2 2425.37   442.1 2427.41
   458.5 2444.99   482.4 2461.63   507.1 2475.83   536.3 2487.13   560.6 2501.13
   587.4 2509.02   643.4 2538.03   701.6 2564.15   756.3 2592.03     819 2619.53
#Mann= 5 ,-1 , 0
       0      .1       0  227.88     .06       0  371.29      .1       0
   380.8    .045       0   442.1      .1       0
#XS Ineff= 2 , 0
          316.22 2449.72
Permanent Ineff=
       F       F
Bank Sta=380.8,442.1
XS Rating Curve= 0 ,0
Exp/Cntr=0.3,0.1

Type RM Length L Ch R = 1 ,13920   ,448.8,450,450.5
XS GIS Cut Line= 3
     2382298.776      594761.249     2382479.024      594393.554
     2382661.807      594027.098
#Sta/Elev= 30
       0 2566.46    42.7 2548.45   105.1 2518.91   131.8 2507.64   136.2 2503.74
   142.2 2496.31   180.8 2470.54     214  2441.9   229.8 2431.24   243.2 2424.29
   265.5 2422.55   274.4 2423.28   292.2 2421.36   367.9 2426.47   378.4 2425.68
   385.7 2421.82   390.2 2419.14   399.1 2418.13   430.4 2418.38   441.1 2421.74
   479.5 2420.43   488.5 2422.68   515.3  2442.8   549.8 2463.51   649.9  2517.4
   670.7 2530.04   685.7 2536.24   698.6 2543.22   743.3  2573.8     819 2618.59
#Mann= 5 ,-1 , 0
       0      .1       0  294.06     .06       0   385.7    .045       0
   441.1     .06       0  465.28      .1       0
#XS Ineff= 2 , 0
          366.54 2439.89
Permanent Ineff=
       F       F
Bank Sta=385.7,441.1
XS Rating Curve= 0 ,0
Exp/Cntr=0.3,0.1

Type RM Length L Ch R = 1 ,13470   ,455.9,450,444.7
XS GIS Cut Line= 3
     2382688.062      594951.486     2382883.001      594591.367
     2383074.316      594229.277
#Sta/Elev= 30
       0 2523.94    87.1 2470.71   146.2 2422.99   152.9 2418.64   161.8 2415.08
     169 2414.28   182.6 2417.79   207.3 2418.54   273.9 2413.27   291.3 2412.99
   302.2 2414.95     330 2416.31     360 2419.99   373.6 2419.52   381.6 2416.32
   391.8 2411.84   400.8 2411.21   427.4 2411.49   432.7 2413.67   434.6 2415.66
   441.7 2421.27     486 2446.03   520.3 2467.77     608 2526.83     623 2538.44
   667.9 2569.25   732.3 2610.64   777.1  2641.8   794.9  2652.4     819 2664.08
#Mann= 5 ,-1 , 0
       0      .1       0  314.94     .06       0   381.6    .045       0
   434.6     .06       0  437.27      .1       0
#XS Ineff= 2 , 0
          359.23 2436.18
Permanent Ineff=
       F       F
Bank Sta=381.6,434.6
XS Rating Curve= 0 ,0
Exp/Cntr=0.3,0.1

Type RM Length L Ch R = 1 ,13020   ,411.3,412,416.2
XS GIS Cut Line= 3
     2383193.634        595130.6     2383307.652      594737.293
     2383421.669      594343.986
#Sta/Elev= 30
       0 2553.12    41.3 2519.51    62.2 2501.03    70.5 2492.02    95.5 2473.14
   145.5 2431.62   153.8 2423.59   162.1 2411.69   170.4 2406.84   178.8 2406.09
   203.8 2408.92   224.6 2407.53   237.1    2410   265.4 2409.05   299.6  2412.5
   332.9 2411.01   353.7 2413.89   370.4 2412.45   379.2  2409.2   388.1 2406.12
   404.2 2405.45   428.7 2405.65   437.8 2408.89   441.2 2411.01   449.5 2411.31
   457.8 2414.11   482.8 2431.01   503.6 2442.54   561.9 2469.04     819 2579.03
#Mann= 5 ,-1 , 0
       0      .1       0  234.69     .06       0  342.31      .1       0
   379.2    .045       0   437.8      .1       0
#XS Ineff= 2 , 0
          355.58 2424.04
Permanent Ineff=
       F       F
Bank Sta=379.2,437.8
XS Rating Curve= 0 ,0
Exp/Cntr=0.3,0.1

Type RM Length L Ch R = 1 ,12608   ,477,503.6,547.2
XS GIS Cut Line= 3
     2383508.979      595217.7742383611.41522612595092.231883046
     2383849.556      594455.371
#Sta/Elev= 30
       0 2586.36    68.7 2553.92    80.1 2544.56    91.4 2531.43   114.2 2515.23
   131.2 2498.87   148.3 2486.27     162 2473.88   194.4 2450.21   197.6 2447.27
   201.9 2440.41   215.4 2409.66     219 2402.88   257.4 2405.86   291.6 2399.33
   325.7 2402.41   398.3 2402.47   411.2 2404.35   417.4 2401.81     424 2399.23
   436.8 2399.05   466.7 2399.33   479.2 2402.29   509.4 2405.53   526.5 2402.49
     535 2403.68   552.1 2417.12   586.2  2439.6   752.8 2507.61     842 2551.82
#Mann= 5 ,-1 , 0
       0      .1       0  201.96     .06       0  324.26      .1       0
   417.4    .045       0   479.2      .1       0
#XS Ineff= 2 , 0
          254.62 2418.31
Permanent Ineff=
       F       F
Bank Sta=417.4,479.2
XS Rating Curve= 0 ,0
Exp/Cntr=0.3,0.1

Type RM Length L Ch R = 1 ,12105   ,403.4,411.6,422.7
XS GIS Cut Line= 2
2383528.50631747595247.736177262     2384422.641      595123.222
#Sta/Elev= 30
       0 2578.72      63 2541.06    66.9 2536.47    73.6  2524.4      79 2519.02
   155.2  2462.6     184 2438.11   192.1 2427.84   196.1 2424.66   233.2 2399.25
   244.6 2397.28   280.9 2400.92   297.2 2394.61   305.2 2393.22   329.4 2396.54
   357.7 2394.57   373.8 2396.75     390 2395.27     438 2397.63   463.6 2395.37
   474.8 2391.79   490.9 2388.23   531.3 2388.52   545.1 2391.97   584.1 2420.36
   612.1 2446.11   777.7 2544.05   826.1 2574.77   862.5 2594.96   902.8 2620.98
#Mann= 5 ,-1 , 0
       0      .1       0   225.9     .06       0  325.25      .1       0
   474.8    .045       0   545.1      .1       0
#XS Ineff= 2 , 0
          336.35 2405.63
Permanent Ineff=
       F       F
Bank Sta=474.8,545.1
XS Rating Curve= 0 ,0
Exp/Cntr=0.3,0.1

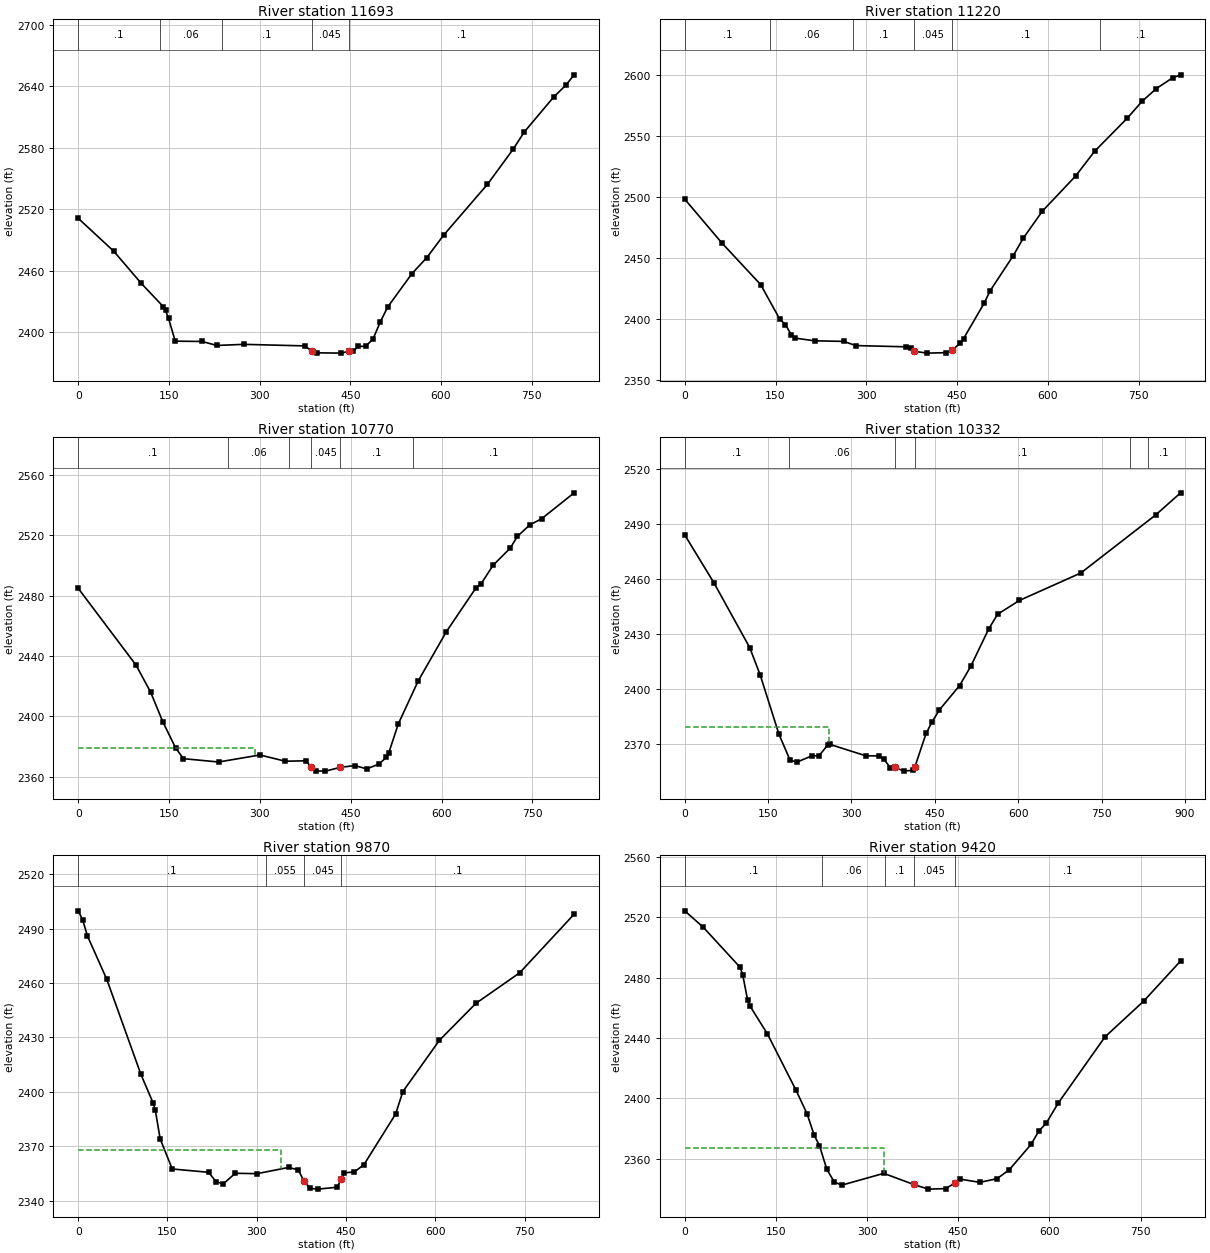
Type RM Length L Ch R = 1 ,11693   ,460.5,472.8,488.3
XS GIS Cut Line= 2
     2383571.704      595527.606     2384384.408      595638.751
#Sta/Elev= 30
       0 2511.12    58.9 2478.95     104 2447.86   140.6 2425.03   144.4 2421.35
   149.4 2413.52   160.5 2391.29   204.9 2391.01   229.2 2387.11   273.6 2388.19
   374.5 2386.69   386.6 2381.56   394.7 2379.92   435.1 2379.63   447.2 2381.44
   455.2 2381.69   463.3 2386.19   475.4 2386.34   487.5 2393.25   499.6 2409.98
   511.8 2424.51   552.1 2457.26   576.4 2472.65   604.6 2494.82   676.9 2544.28
   719.5 2578.57   737.8 2595.32   786.3 2629.31   806.5 2640.94   820.3 2651.05
#Mann= 5 ,-1 , 0
       0      .1       0  134.57     .06       0  238.43      .1       0
   386.6    .045       0   447.2      .1       0
Bank Sta=386.6,447.2
XS Rating Curve= 0 ,0
Exp/Cntr=0.3,0.1

Type RM Length L Ch R = 1 ,11220   ,463.7,450,436.3
XS GIS Cut Line= 3
     2383436.742       595776.79     2383776.384      596005.555
     2384116.027       596234.32
#Sta/Elev= 30
       0 2498.18      61 2462.51   125.5 2428.15   156.7 2400.18   166.4 2395.31
     176 2387.22   181.6  2384.4   214.6 2382.13   262.8 2381.66   282.5 2378.24
   366.1 2377.22   373.8 2375.89   378.6 2373.55   400.6 2372.05   431.6 2372.43
   441.3 2374.45   454.9 2380.08   460.6 2383.98   494.3 2412.72   504.4 2423.06
   542.6 2451.89   559.1 2466.14   590.8 2488.39   645.6 2517.07   676.8 2537.26
   730.6 2564.31   755.1 2578.15   778.9  2588.7   805.7 2597.52     819 2599.97
#Mann= 6 ,-1 , 0
       0      .1       0  141.46     .06       0  277.64      .1       0
   378.6    .045       0   441.3      .1       0   686.2      .1       0
Bank Sta=378.6,441.3
XS Rating Curve= 0 ,0
Exp/Cntr=0.3,0.1

Type RM Length L Ch R = 1 ,10770   ,442.2,438.3,434.5
XS GIS Cut Line= 3
     2383195.485      596384.321     2383603.897      596414.122
     2384012.117      596446.605
#Sta/Elev= 30
       0 2484.77    95.5 2433.95   119.6 2416.06   139.6 2396.57   160.8 2379.22
   173.8 2372.07   231.9 2369.87   300.1 2374.52   341.9 2370.38   376.3 2370.66
   384.3 2366.66   392.3 2363.92   408.3 2363.83   432.4  2366.3   456.5 2367.47
   476.6 2365.34   496.6  2368.5   508.7 2372.89   512.7 2375.72   528.7 2395.17
   561.5 2423.54   607.9 2456.04   657.1 2485.22   665.2 2487.68   685.2 2500.05
   713.3 2511.28   725.3 2519.11   745.4 2526.61   765.5 2530.86     819 2547.94
#Mann= 6 ,-1 , 0
       0      .1       0  246.61     .06       0   348.7      .1       0
   384.3    .045       0   432.4      .1       0  553.11      .1       0
#XS Ineff= 2 , 0
          292.61 2379.21
Permanent Ineff=
       F       F
Bank Sta=384.3,432.4
XS Rating Curve= 0 ,0
Exp/Cntr=0.3,0.1

Type RM Length L Ch R = 1 ,10332   ,488.3,461.7,434.3
XS GIS Cut Line= 3
      2383230.27      596885.8432383795.74004289596834.868033138
     2384026.392      596607.013
#Sta/Elev= 30
       0 2484.21    52.7    2458   116.9  2422.8   135.8 2407.86   169.4 2375.68
   189.2 2361.62   201.3 2360.26   229.4 2363.85   241.5 2363.73   257.5 2369.76
   261.5 2369.98   325.8 2363.78   349.9 2363.74   357.9 2362.07     370 2357.26
     378 2357.53   394.1 2355.43   410.1  2355.9   414.1 2357.81   434.2 2375.97
   445.2 2382.43   458.3 2388.87   494.5 2402.07   514.6 2412.59   546.7 2432.83
   562.7 2440.89   601.9 2448.43   712.6 2463.43   847.1 2495.04     892  2507.1
#Mann= 6 ,-1 , 0
       0      .1       0  187.01     .06       0     378    .045       0
   414.1      .1       0  800.47      .1       0  833.02      .1       0
#XS Ineff= 2 , 0
          260.31 2379.45
Permanent Ineff=
       F       F
Bank Sta=378,414.1
XS Rating Curve= 0 ,0
Exp/Cntr=0.3,0.1

Type RM Length L Ch R = 1 ,9870    ,449.6,450,447.2
XS GIS Cut Line= 3
      2383906.94      597474.174     2383982.558      597074.386
 2384072.1921267596657.580395711
#Sta/Elev= 30
       0 2499.88     7.4 2494.97    15.6 2485.96    48.1 2461.99   105.3 2409.67
   125.5 2394.09   129.5 2389.92   137.7 2373.99     158 2357.42   219.1  2355.6
   231.3 2350.51   243.5 2349.14   263.9 2355.06   300.5 2354.84   353.4 2358.27
   369.7 2356.96   379.2 2350.84   389.5 2346.75   402.3 2346.31     435 2347.35
   441.82351.847   447.3 2355.32   463.9 2355.78     480 2359.79   533.2 2387.73
   545.5 2400.17   606.8 2428.42   668.2 2448.83   741.9 2465.74   833.2 2498.03
#Mann= 4 ,-1 , 0
       0      .1       0  315.51    .055       0   379.2    .045       0
  441.82      .1       0
#XS Ineff= 2 , 0
          340.86 2367.66
Permanent Ineff=
       F       F
Bank Sta=379.2,441.8
XS Rating Curve= 0 ,0
Exp/Cntr=0.3,0.1

Type RM Length L Ch R = 1 ,9420    ,432.3,450,477.3
XS GIS Cut Line= 3
2384354.92090643597516.741939571     2384430.263      597116.608
     2384483.426       596711.41
#Sta/Elev= 30
       0 2524.38    30.4 2513.57    91.4  2486.8    95.5 2481.84   103.6 2465.04
   107.6 2461.11   136.2 2442.66   183.1 2405.39   201.3 2389.71   213.1 2375.45
   221.7 2368.61   233.9 2352.77   246.1 2344.51   258.3 2342.35   327.5 2350.18
   376.4 2342.86   400.8 2339.72   429.1 2340.06   445.2 2343.87   453.3 2346.32
   485.5 2344.22   513.8 2346.63     534 2352.59   570.3 2369.64   582.4 2378.23
   594.5  2383.3   614.6  2396.9   691.3 2440.69   755.1 2464.48   815.8 2491.11
#Mann= 5 ,-1 , 0
       0      .1       0  226.11     .06       0  329.57      .1       0
   376.4    .045       0   445.2      .1       0
#XS Ineff= 2 , 0
          328.54 2366.91
Permanent Ineff=
       F       F
Bank Sta=376.4,445.2
XS Rating Curve= 0 ,0
Exp/Cntr=0.3,0.1

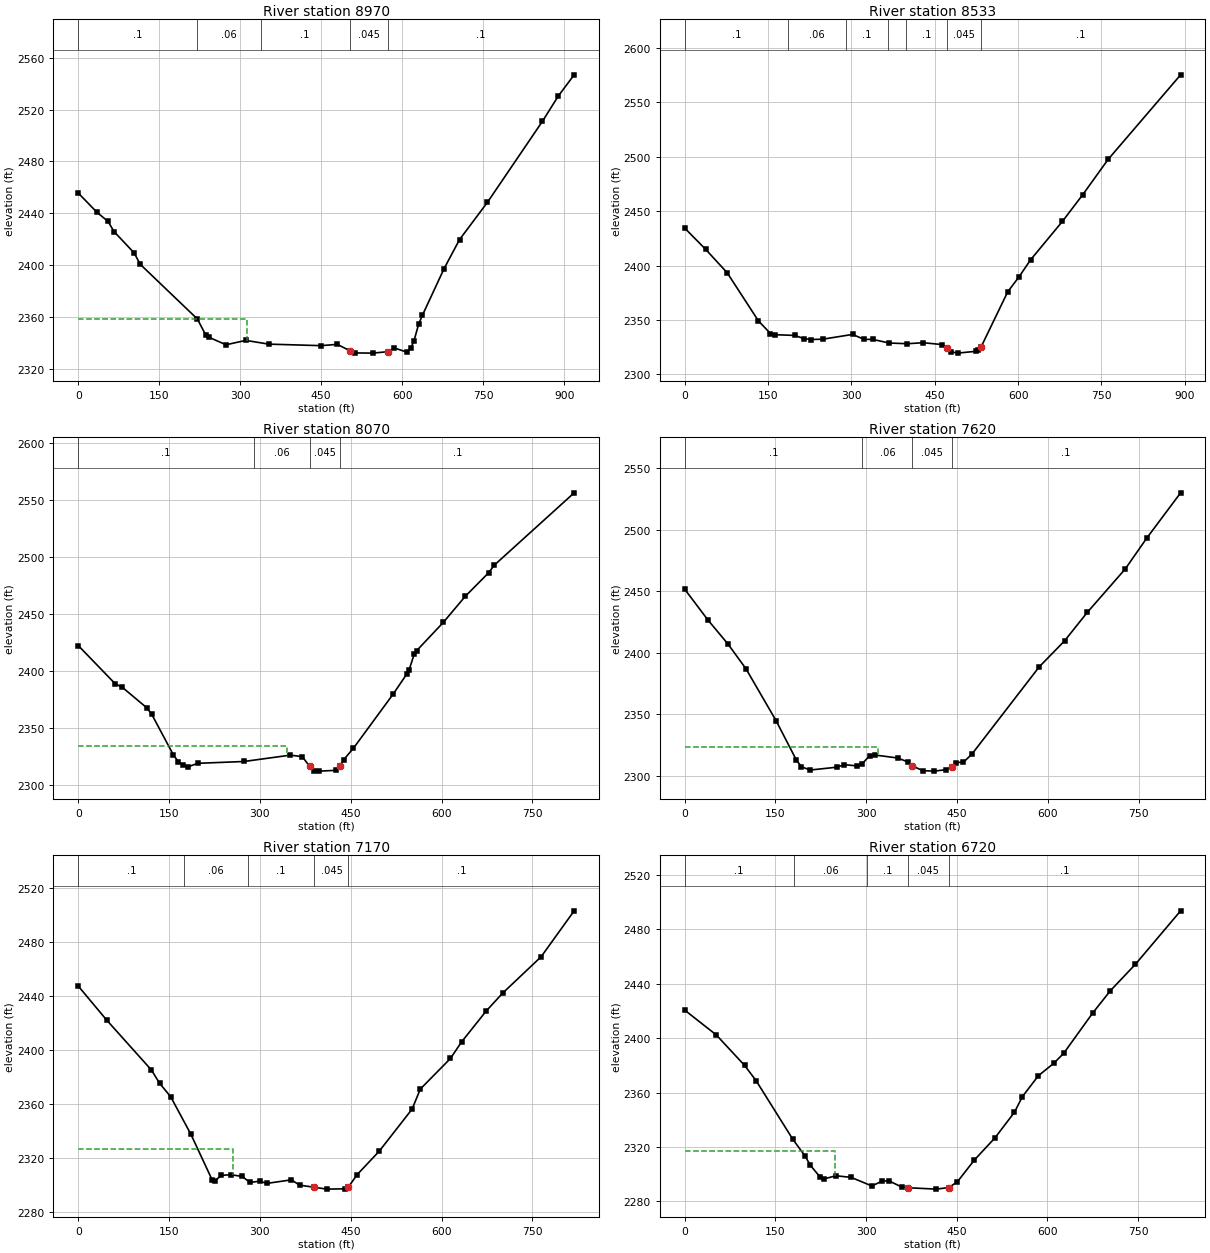
Type RM Length L Ch R = 1 ,8970    ,414,437.3,479.5
XS GIS Cut Line= 3
  2384452.657423597602.697148149     2384850.049      597255.408
     2385123.172      596976.171
#Sta/Elev= 30
       0  2455.7    34.6 2440.91    55.2 2433.79    66.5 2425.93   103.7 2409.52
   114.7 2400.86   220.6  2358.7   236.5 2346.08   241.8 2344.65   273.7 2338.81
   310.3  2342.2   352.9 2339.32   449.2 2338.15   479.9 2339.12   503.1 2334.22
   512.7 2332.55   545.6 2332.39   573.9 2333.53   585.2 2336.42   608.8 2333.11
   616.3 2336.67     622  2342.1   630.4 2354.73   637.4 2361.55   677.5 2397.44
   706.1 2419.81   757.6 2448.41   859.6 2510.88   889.1 2530.44   918.4 2546.73
#Mann= 5 ,-1 , 0
       0      .1       0  220.55     .06       0   337.6      .1       0
   503.1    .045       0   573.9      .1       0
#XS Ineff= 2 , 0
          312.11 2358.55
Permanent Ineff=
       F       F
Bank Sta=503.1,573.9
XS Rating Curve= 0 ,0
Exp/Cntr=0.3,0.1

Type RM Length L Ch R = 1 ,8533    ,470.6,462.7,455
XS GIS Cut Line= 3
     2384471.913      597682.3512384687.03605653597593.965461987
2385329.79978558597742.934582844
#Sta/Elev= 30
       0 2434.34    37.7 2414.86    76.6 2393.26   132.8 2349.08   154.4 2337.59
   163.1 2336.49   197.7 2335.82     215 2332.88   227.9 2332.07   248.7 2332.39
   302.1 2336.74   322.6 2332.26     339 2332.12   367.8 2328.87   400.6 2328.21
   429.4 2329.14   462.2 2327.47   471.5 2324.52   478.6 2320.95     491 2319.58
   523.8 2321.25   527.9 2322.09   533.1 2324.96   581.3 2375.86   601.8 2389.71
   622.3 2405.16   679.8 2440.54   716.5 2465.14     762 2497.43   892.4    2575
#Mann= 7 ,-1 , 0
       0      .1       0  185.76     .06       0  290.63      .1       0
  365.81    .055       0  397.94      .1       0   471.5    .045       0
   533.1      .1       0
Bank Sta=471.5,533.1
XS Rating Curve= 0 ,0
Exp/Cntr=0.3,0.1

Type RM Length L Ch R = 1 ,8070    ,456.4,450,443.7
XS GIS Cut Line= 3
      2384433.98      598129.096     2384841.984      598094.131
     2385250.145      598060.976
#Sta/Elev= 30
       0 2422.09      61 2388.55    73.1  2385.3   113.2 2367.46   121.4 2361.76
   157.3 2325.99   165.4 2320.16   173.4 2317.28   181.4 2315.68   197.5 2318.76
   273.8 2320.35   350.3 2325.93   370.1 2324.59   382.2    2316   390.2 2312.42
   398.2  2311.9   426.3 2312.61     433 2316.57   438.4 2321.95   454.4  2331.9
   520.4 2379.69   542.7 2397.14   546.6 2400.95   554.7 2414.25   558.8 2417.48
   602.9 2442.35     639 2465.11   677.6 2485.81   687.2  2492.6     819 2556.01
#Mann= 4 ,-1 , 0
       0      .1       0  290.68     .06       0   382.2    .045       0
     433      .1       0
#XS Ineff= 2 , 0
          344.56 2333.57
Permanent Ineff=
       F       F
Bank Sta=382.2,433
XS Rating Curve= 0 ,0
Exp/Cntr=0.3,0.1

Type RM Length L Ch R = 1 ,7620    ,455.4,450,443.3
XS GIS Cut Line= 3
     2384518.199      598656.628      2384909.84      598537.824
      2385302.29      598418.514
#Sta/Elev= 30
       0 2451.83    38.2 2426.89    71.6 2407.17   101.3 2387.06   151.1  2344.8
   184.6 2312.81   192.9 2307.43   207.1 2304.73   251.4 2307.05   263.9  2309.1
   284.8  2308.1   293.2 2309.79   305.7  2316.4   314.1 2316.96   351.7 2314.56
   368.4  2311.4   376.2  2308.1   393.5 2304.21   412.2 2303.85   431.1 2304.96
   441.2 2307.49   447.8 2310.86   460.6 2311.13   474.4 2317.56   585.8 2388.66
   627.6 2409.75   665.2 2432.95   727.9 2468.24   763.1 2493.11   819.4 2530.17
#Mann= 4 ,-1 , 0
       0      .1       0  293.79     .06       0   376.2    .045       0
   441.2      .1       0
#XS Ineff= 2 , 0
          319.59 2323.66
Permanent Ineff=
       F       F
Bank Sta=376.2,441.2
XS Rating Curve= 0 ,0
Exp/Cntr=0.3,0.1

Type RM Length L Ch R = 1 ,7170    ,461.2,450,442.6
XS GIS Cut Line= 3
     2384724.056      599143.897     2385085.468      598951.357
      2385446.88      598758.818
#Sta/Elev= 30
       0 2447.51    47.1 2422.18   120.9  2385.2   134.5 2375.29   152.6 2365.43
   186.1 2337.49   221.5 2303.34   225.1 2302.65   236.3 2307.06   252.3  2307.5
   270.4 2306.27     284 2301.76   299.9 2302.77   311.2 2301.05     352  2303.7
   365.6 2299.79   390.1 2298.18   410.5 2296.82   440.4 2297.05   446.3 2298.47
   460.8 2307.66   497.1 2324.96   551.4 2356.21     565 2371.09   614.7 2393.75
     633 2405.98   673.8 2428.99     701 2442.26   764.5 2469.24     819 2503.29
#Mann= 5 ,-1 , 0
       0      .1       0  175.35     .06       0  280.29      .1       0
   390.1    .045       0   446.3      .1       0
#XS Ineff= 2 , 0
          255.65 2326.95
Permanent Ineff=
       F       F
Bank Sta=390.1,446.3
XS Rating Curve= 0 ,0
Exp/Cntr=0.3,0.1

Type RM Length L Ch R = 1 ,6720    ,461.5,450,438.7
XS GIS Cut Line= 3
     2385022.578      599624.489     2385313.677      599336.858
     2385618.462       599061.09
#Sta/Elev= 30
       0 2420.57    52.2 2402.37      99 2379.98   118.3 2368.62   178.7 2325.74
   199.2 2313.28   207.7 2306.65   224.2 2297.73   230.4  2296.5   250.2 2298.85
   275.4 2297.64   309.6 2291.35   326.5 2294.87     338 2295.08   360.1  2290.3
     369 2290.05   416.1 2289.01   436.9 2290.16     451 2294.37   479.3 2310.48
   513.2 2326.67   545.5 2345.53   558.6    2357   585.1 2372.39   610.3 2381.42
   626.8 2388.77     675 2418.51   704.3 2434.92   745.6 2454.29   820.3 2493.54
#Mann= 5 ,-1 , 0
       0      .1       0  180.27     .06       0  302.18      .1       0
     369    .045       0   436.9      .1       0
#XS Ineff= 2 , 0
          248.46 2316.91
Permanent Ineff=
       F       F
Bank Sta=369,436.9
XS Rating Curve= 0 ,0
Exp/Cntr=0.3,0.1

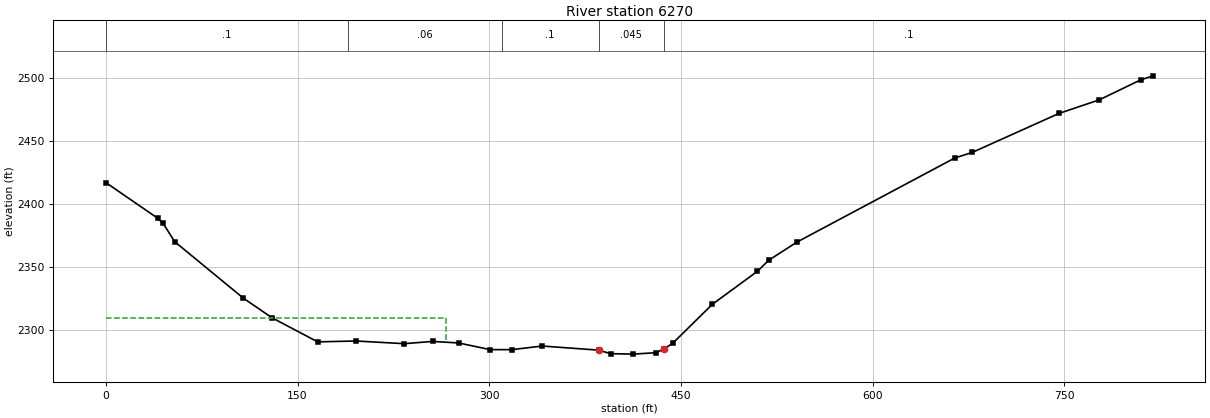
Type RM Length L Ch R = 1 ,6270    ,450.2,450,450.7
XS GIS Cut Line= 3
     2385503.851      599942.959     2385689.397      599577.557
     2385861.727      599206.144
#Sta/Elev= 30
       0    2417    40.5 2388.68    44.9 2384.42    53.9 2369.96   107.7 2324.96
   130.1 2309.38   165.8 2290.25   195.6 2290.95   233.4 2288.82   255.8 2290.61
   276.1 2289.38   300.6 2284.09   317.6 2284.05   341.4 2286.94   385.5 2283.68
   394.9 2280.88   412.5  2280.5   430.4 2281.63   436.9  2284.7   443.6 2289.21
   474.5 2320.11   509.8  2346.4   518.6 2355.15   540.6 2369.57   664.1 2436.48
   677.9 2440.98   745.6 2471.93   777.3 2482.81   809.6 2498.66   819.3 2501.89
#Mann= 5 ,-1 , 0
       0      .1       0  189.46     .06       0  309.64      .1       0
   385.5    .045       0   436.9      .1       0
#XS Ineff= 2 , 0
             266 2309.55
Permanent Ineff=
       F       F
Bank Sta=385.5,436.9
XS Rating Curve= 0 ,0
Exp/Cntr=0.3,0.1