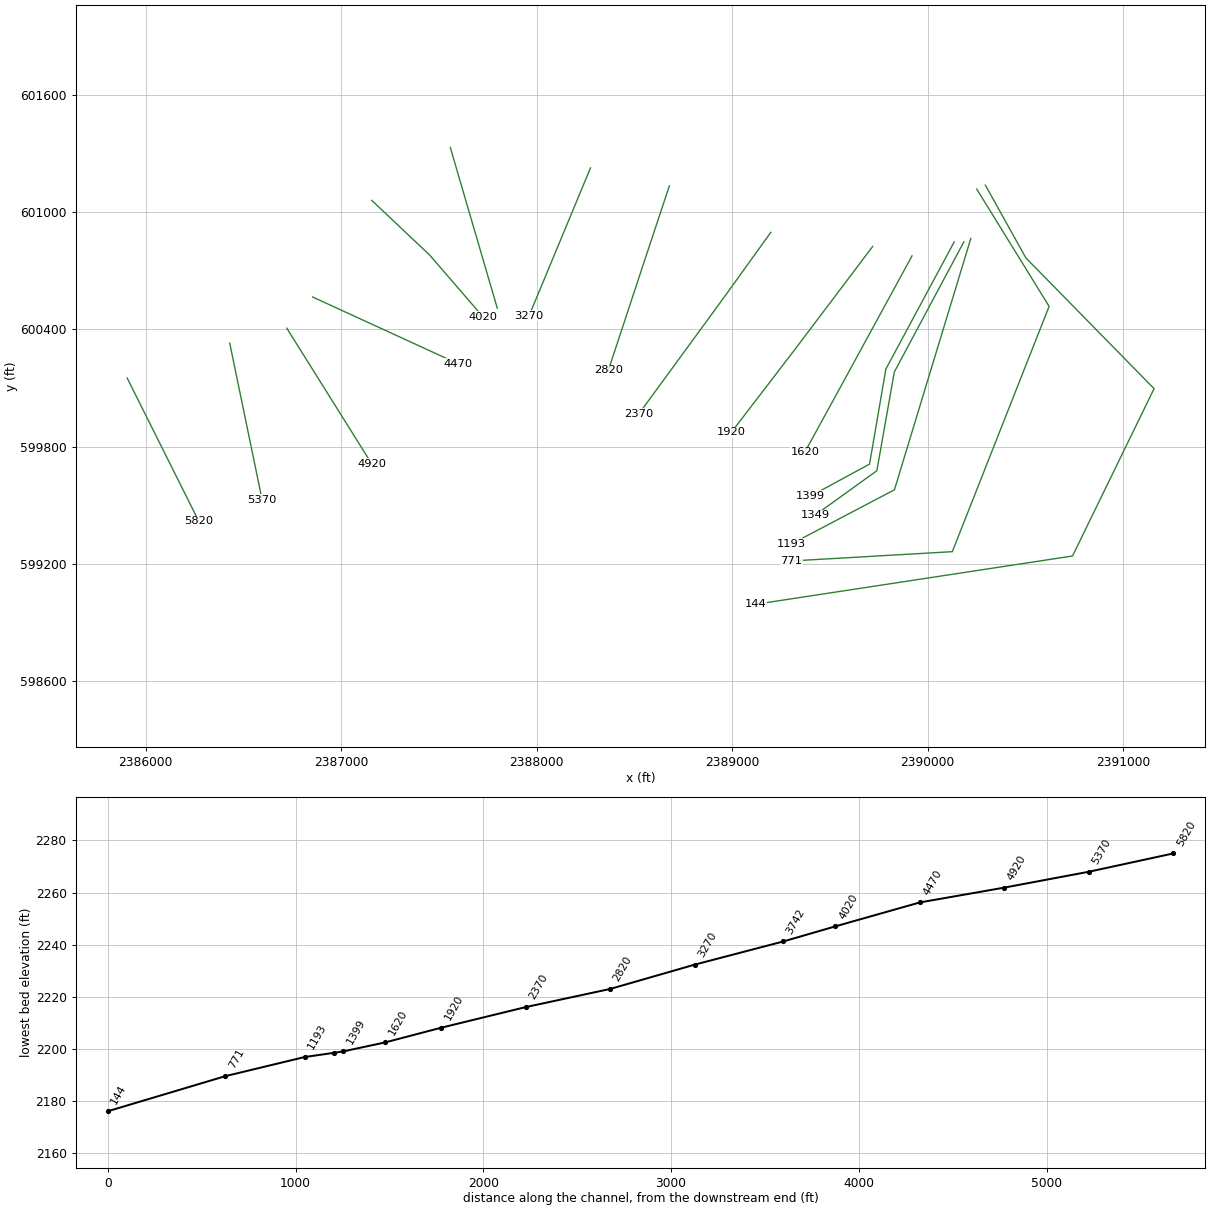
HEC-RAS study BIGRN.prj: BIGRN

--- BIGRN.g02 (geometry) --- (continued)

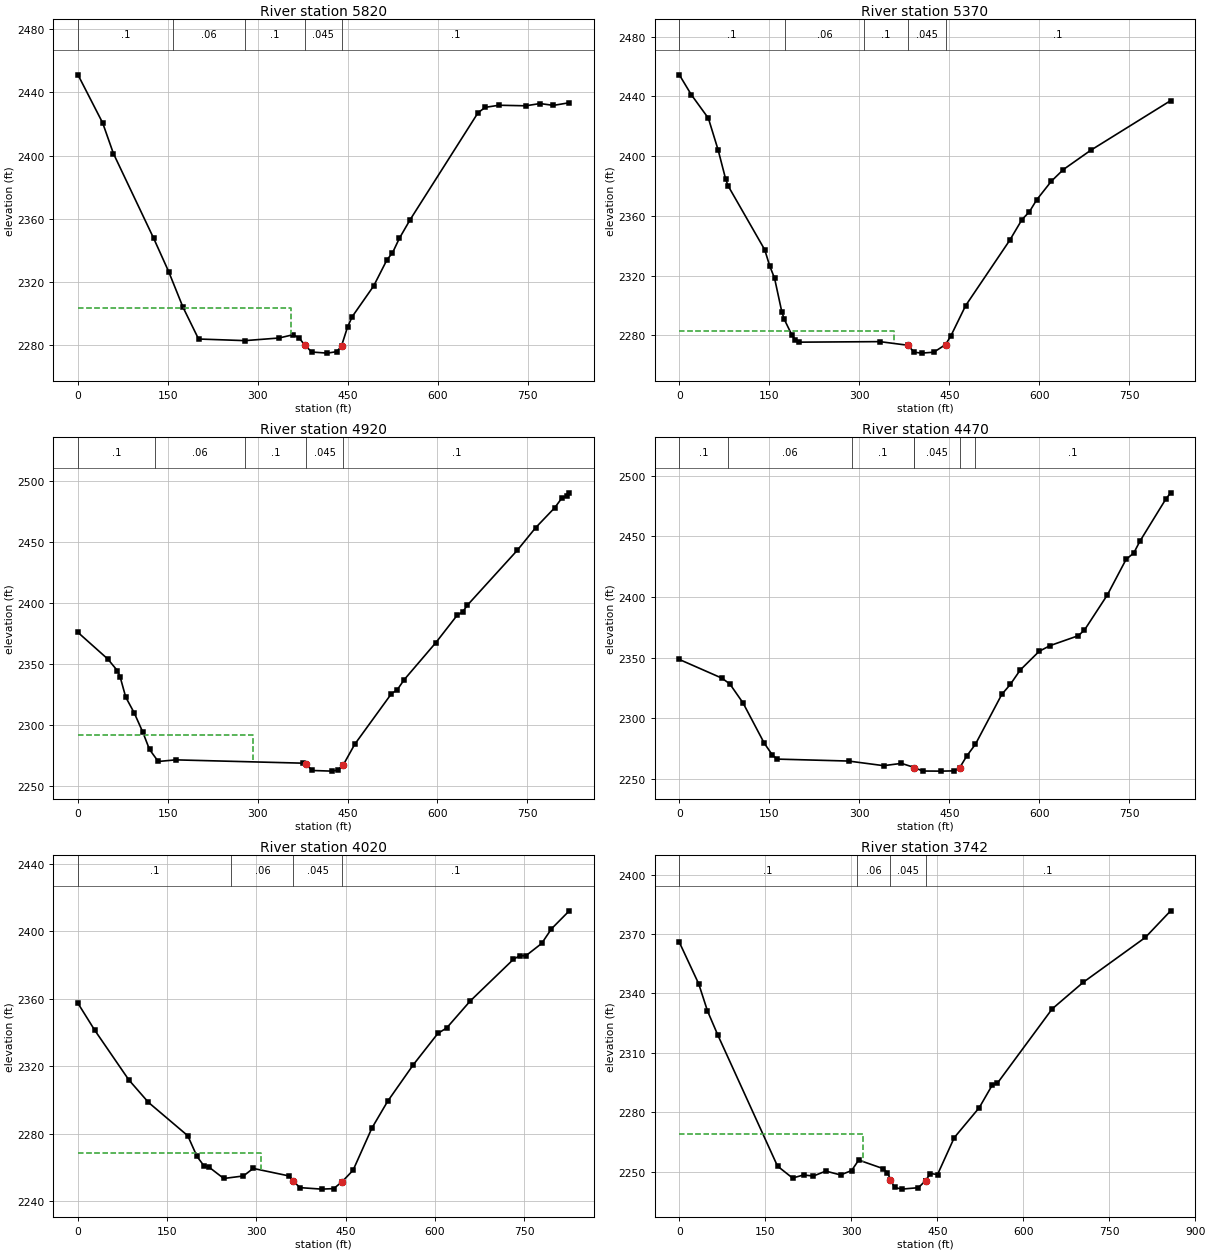
Type RM Length L Ch R = 1 ,5820    ,457.7,450,441.6
XS GIS Cut Line= 3
     2385904.833      600151.775     2386087.993      599785.519
     2386271.152      599419.264
#Sta/Elev= 30
       0 2451.16    41.2 2420.68    59.1 2401.34   126.2 2347.68   151.2  2326.6
     175 2304.12     201 2283.97   278.3 2282.94   335.2  2284.6   358.8  2286.7
   368.8 2284.61   377.7 2280.23   389.7 2275.73   415.7 2275.03   431.4 2275.97
   439.3 2279.58   449.3 2291.46   457.2 2298.14   492.9 2317.53   515.3 2334.25
   524.2 2338.41   535.7 2347.64   553.6 2359.41   666.9 2427.17   678.9 2430.58
   701.8 2431.91   746.5 2431.56   770.2 2432.98   792.6 2431.82     819  2433.5
#Mann= 5 ,-1 , 0
       0      .1       0  158.38     .06       0  278.03      .1       0
   377.7    .045       0   439.3      .1       0
#XS Ineff= 2 , 0
          354.66  2303.8
Permanent Ineff=
       F       F
Bank Sta=377.7,439.3
XS Rating Curve= 0 ,0
Exp/Cntr=0.3,0.1

Type RM Length L Ch R = 1 ,5370    ,438.9,450,461.1
XS GIS Cut Line= 3
     2386429.673      600330.303     2386512.544      599929.277
     2386595.415       599528.25
#Sta/Elev= 30
       0 2454.49    19.8 2441.25    48.4  2425.4    64.8 2403.95      77 2384.94
    81.1 2380.22   142.4 2337.23   150.5 2326.58   158.7 2318.23   170.9 2295.51
     175 2290.58   187.3 2280.38   193.5 2276.87   199.5 2275.35   334.3  2275.7
   380.8 2273.28   391.5 2268.62   403.8    2268   424.2 2268.62   443.8 2273.73
   452.8 2279.68   477.3 2299.86   550.8 2343.64   571.2  2357.5   583.5  2362.7
   595.7 2370.73   620.2 2383.23   640.2 2391.03   685.6 2403.88     819  2437.2
#Mann= 5 ,-1 , 0
       0      .1       0  175.87     .06       0   308.1      .1       0
   380.8    .045       0   443.8      .1       0
#XS Ineff= 2 , 0
          357.93 2283.16
Permanent Ineff=
       F       F
Bank Sta=380.8,443.8
XS Rating Curve= 0 ,0
Exp/Cntr=0.3,0.1

Type RM Length L Ch R = 1 ,4920    ,435.6,450,475.8
XS GIS Cut Line= 3
     2386721.705      600406.475     2386939.741      600058.228
     2387156.879      599711.323
#Sta/Elev= 30
       0 2375.74    49.8 2353.91    65.6 2344.49    70.3 2339.38    79.7 2322.65
    93.9 2309.69   108.1 2294.01   119.4 2279.68     134 2269.82     163 2271.16
   374.8 2268.45   380.6 2267.44   391.2 2262.43   424.1 2261.91   433.7 2262.79
   443.1 2267.26   461.9 2283.89   523.3 2325.52   532.8  2328.6   544.7 2337.07
   597.5 2367.45   633.1 2389.95   641.9 2392.47   650.2 2398.22   733.2 2443.11
     764 2461.75   795.7 2478.05   807.3 2485.77     816 2487.82   820.1 2490.35
#Mann= 5 ,-1 , 0
       0      .1       0  128.26     .06       0  278.85      .1       0
   380.6    .045       0   443.1      .1       0
#XS Ineff= 2 , 0
           292.5 2291.28
Permanent Ineff=
       F       F
Bank Sta=380.6,443.1
XS Rating Curve= 0 ,0
Exp/Cntr=0.3,0.1

Type RM Length L Ch R = 1 ,4470    ,463.2,450,432.9
XS GIS Cut Line= 3
     2386854.244        600565.9     2387226.417      600395.085
      2387598.59       600224.27
#Sta/Elev= 30
       0 2348.43      71 2332.99    84.2  2328.2   106.2 2312.51   141.5 2279.33
   154.6 2269.91   162.5 2266.16   282.2 2264.54   340.5 2260.73   370.3 2262.62
   391.8 2259.21   405.5 2256.31   436.3 2256.22   458.2 2256.44   467.5 2259.16
   479.3 2268.85   493.5 2278.33   537.5 2319.55   551.7 2327.79   568.3 2339.73
   599.9 2355.18     618 2359.86   665.1 2368.05   675.4 2372.75   713.5 2401.71
   744.7 2431.02   757.6 2436.39   767.7    2446   811.1 2480.98     819 2486.03
#Mann= 7 ,-1 , 0
       0      .1       0   81.54     .06       0  287.61      .1       0
  390.65      .1       0   391.8    .045       0   467.5      .1       0
  493.69      .1       0
Bank Sta=391.8,467.5
XS Rating Curve= 0 ,0
Exp/Cntr=0.3,0.1

Type RM Length L Ch R = 1 ,4020    ,297.7,278.5,265.7
XS GIS Cut Line= 3
     2387156.572      601060.325     2387453.147      600780.129
     2387726.245      600463.705
#Sta/Elev= 30
       0 2357.34      28 2341.47    85.5 2311.88   118.5 2298.53   184.6 2278.73
   200.1 2266.45   211.9 2260.81   220.4 2260.07   245.1 2253.36   278.1 2254.85
   294.6 2259.34   355.2 2254.84   361.9 2251.82   373.2 2247.93   409.6 2247.04
   429.9 2247.35     444 2251.41   462.5 2258.26   494.2 2283.31   520.6 2299.17
   563.5 2320.76   605.1 2339.49   619.9 2342.74   659.6 2358.78   731.9 2383.39
   742.5 2385.59   753.3 2385.66   779.5 2392.87   796.1 2401.59     826 2412.26
#Mann= 4 ,-1 , 0
       0      .1       0  258.02     .06       0   361.9    .045       0
     444      .1       0
#XS Ineff= 2 , 0
          308.01 2268.77
Permanent Ineff=
       F       F
Bank Sta=361.9,444
XS Rating Curve= 0 ,0
Exp/Cntr=0.3,0.1

Type RM Length L Ch R = 1 ,3742    ,494.8,471.5,450.9
XS GIS Cut Line= 2
     2387558.217      601331.293     2387798.661      600508.483
#Sta/Elev= 30
       0 2365.86    33.8 2344.87    49.1  2331.2    67.1 2319.03   171.3 2252.84
   197.5 2246.83   216.8 2248.37   233.8 2247.82   255.5 2250.33   281.3 2248.38
   300.5  2250.6     313 2255.89   355.5 2251.58     363 2249.56   368.4 2246.01
   375.5 2242.09     388 2241.22   417.1 2241.95   429.6 2245.49   429.6  2245.5
     438  2249.1   450.5 2248.59   479.7 2267.23   523.2 2282.32   546.3 2293.93
   554.7 2294.62   650.5 2332.22   704.7 2345.65     813 2368.28   857.2 2381.74
#Mann= 4 ,-1 , 0
       0      .1       0  309.99     .06       0   368.4    .045       0
   429.6      .1       0
#XS Ineff= 2 , 0
          320.33 2269.15
Permanent Ineff=
       F       F
Bank Sta=368.4,429.6
XS Rating Curve= 0 ,0
Exp/Cntr=0.3,0.1

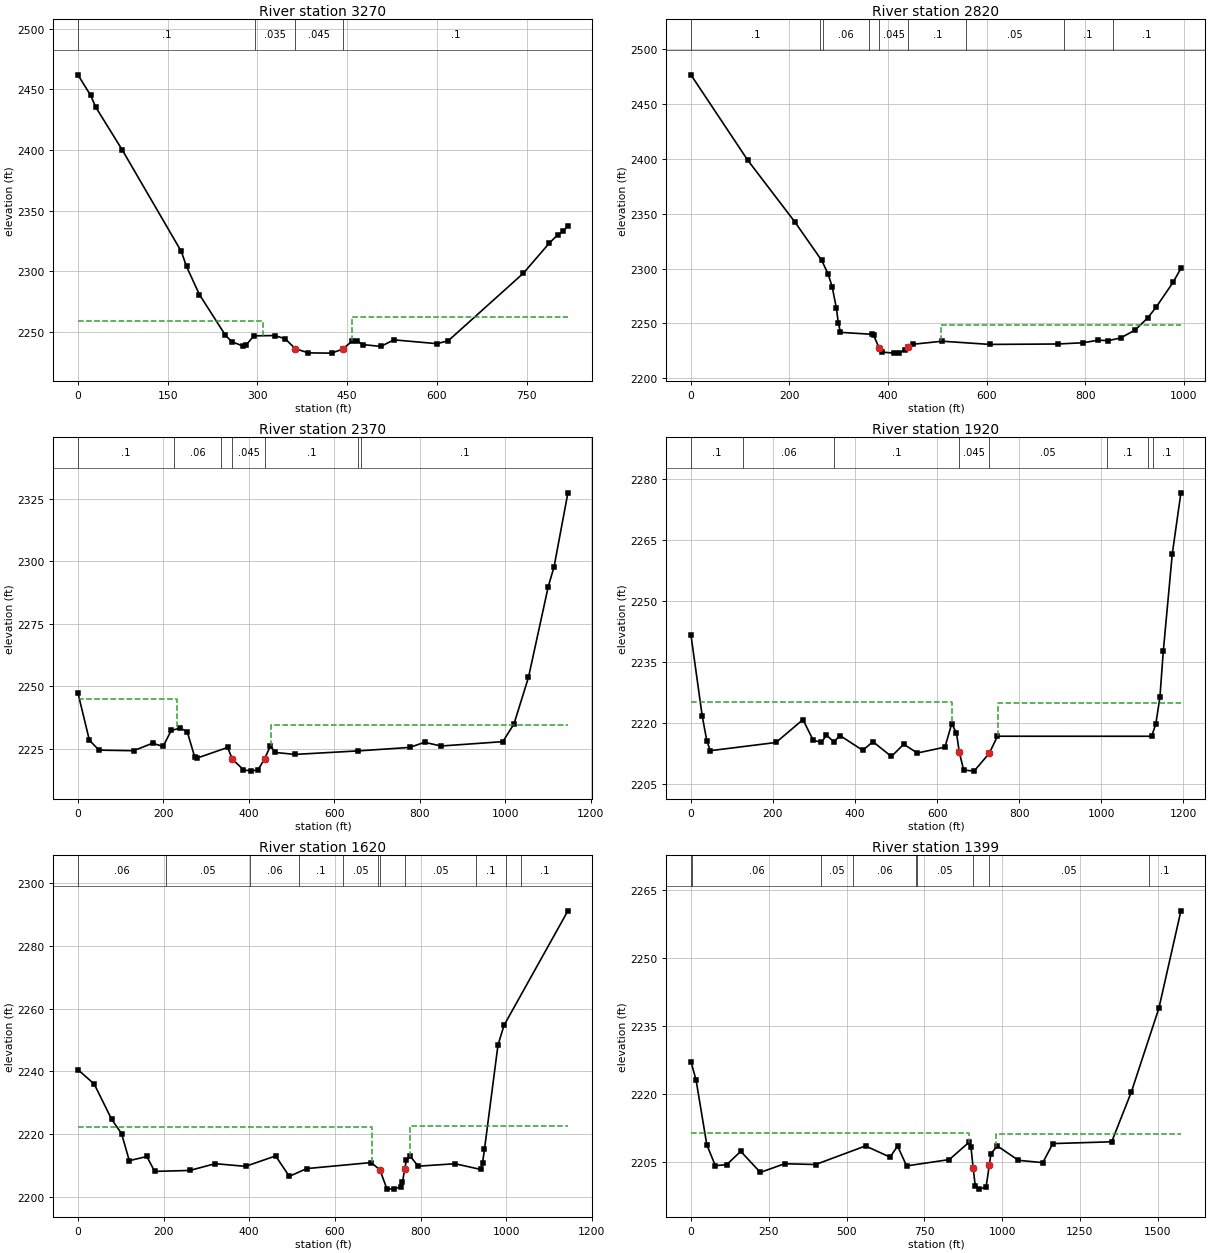
Type RM Length L Ch R = 1 ,3270    ,443.9,450,451.6
XS GIS Cut Line= 3
     2388275.454      601226.455     2388118.332      600848.298
     2387961.209      600470.141
#Sta/Elev= 30
       0 2461.97    21.2 2445.08    29.8 2435.32    73.7 2400.32   172.8 2316.22
   181.5 2303.82   203.1 2280.64   246.4  2247.2   257.2 2241.78   275.6 2238.19
   281.1 2239.03   294.1 2246.57   328.7 2246.83   346.1 2244.28   363.4 2236.01
     385 2232.53     424 2232.33   442.5 2235.64   458.7 2242.34   467.3 2242.13
     476 2239.39   506.3 2237.84     528 2243.28     600 2240.14   618.9 2242.49
   744.6 2298.29   787.9 2323.07     802 2330.05   811.1 2332.73     819 2337.59
#Mann= 4 ,-1 , 0
       0      .1       0  295.68    .035       0   363.4    .045       0
   442.5      .1       0
#XS Ineff= 2 , 0
          310.18 2259.18  458.87         2261.78
Permanent Ineff=
       F       F
Bank Sta=363.4,442.5
XS Rating Curve= 0 ,0
Exp/Cntr=0.3,0.1

Type RM Length L Ch R = 1 ,2820    ,462.9,450,440.9
XS GIS Cut Line= 3
     2388679.011      601134.804      2388550.15      600746.567
2388366.81645662600190.802301286
#Sta/Elev= 30
       0 2476.32   115.1 2398.72   210.6 2342.58   265.4 2307.39   278.1 2295.34
   286.5 2283.63   294.9 2264.52   299.1 2250.61   303.4 2241.92   366.6 2240.15
   370.8 2239.12   381.8 2227.88   387.6 2223.95   412.9    2223   421.4 2223.24
     434 2225.67   440.9 2228.48   450.8 2231.08   509.7 2233.84   606.7 2230.93
   744.1 2231.31   796.2 2232.44   825.7 2234.75   846.8  2234.4     872  2236.8
   901.5 2244.08   926.8 2254.99   943.8  2264.7   978.4 2287.45   994.3  2300.1
#Mann= 9 ,-1 , 0
       0      .1       0  262.26    .055       0  267.21     .06       0
  361.15      .1       0   381.8    .045       0   440.9      .1       0
  558.89     .05       0  756.62      .1       0  855.48      .1       0
#XS Ineff= 2 , 0
                          507.37         2248.15
Permanent Ineff=
       F       F
Bank Sta=381.8,440.9
XS Rating Curve= 0 ,0
Exp/Cntr=0.3,0.1

Type RM Length L Ch R = 1 ,2370    ,452.8,450,450.7
XS GIS Cut Line= 3
     2389197.781      600896.693     2388958.785      600564.171
2388523.58854459599969.043575073
#Sta/Elev= 30
       0 2247.33    26.8 2228.41    49.3 2224.43   130.3  2224.2   174.6 2227.19
   199.3 2225.91   218.4  2232.3   238.7 2233.22   255.7 2231.87   273.1 2221.85
   278.1 2221.21   350.3 2225.49   361.7 2220.77   387.5 2216.55   406.2 2216.03
   421.9 2216.63   436.7 2220.87   450.5 2226.11     462  2223.5   507.8 2222.72
   656.6 2224.13   776.8 2225.52   811.2 2227.56     850 2226.08   994.4 2227.82
  1020.6 2234.92  1054.5 2253.54  1100.8 2289.86  1114.3 2297.72  1146.8 2327.38
#Mann= 7 ,-1 , 0
       0      .1       0  224.84     .06       0  334.17      .1       0
   361.7    .045       0   436.7      .1       0   656.6     .05       0
  663.24      .1       0
#XS Ineff= 2 , 0
          232.85 2244.76  450.82         2234.55
Permanent Ineff=
       F       F
Bank Sta=361.7,436.7
XS Rating Curve= 0 ,0
Exp/Cntr=0.3,0.1

Type RM Length L Ch R = 1 ,1920    ,296.9,300,308.3
XS GIS Cut Line= 3
2389719.28830274600824.797298689     2389313.314      600287.306
2388996.59854983599874.241862878
#Sta/Elev= 30
       0 2241.72    27.5 2221.71    38.9 2215.51    47.5 2213.16   207.4 2215.18
     273 2220.81   298.1 2215.72   318.2  2215.2   330.2 2217.02   348.3 2215.32
   363.3 2216.88   418.7 2213.25   443.5 2215.37   488.6 2211.73   518.6 2214.75
   551.7 2212.58     619 2214.03   635.7 2219.84   647.2 2217.43   654.1 2212.74
   664.6  2208.4     690 2208.12   727.1 2212.52     747 2216.72  1122.7 2216.71
  1132.8 2219.68  1142.9 2226.29  1151.1 2237.63  1173.1 2261.69  1194.1  2276.7
#Mann= 8 ,-1 , 0
       0      .1       0  127.22     .06       0  348.61      .1       0
   654.1    .045       0   727.1     .05       0 1014.12      .1       0
 1113.56     .05       0 1125.25      .1       0
#XS Ineff= 2 , 0
           636.2 2225.23  749.18         2224.79
Permanent Ineff=
       F       F
Bank Sta=654.1,727.1
XS Rating Curve= 0 ,0
Exp/Cntr=0.3,0.1

Type RM Length L Ch R = 1 ,1620    ,216.5,221.4,232.6
XS GIS Cut Line= 3
2389920.42331974600776.244454517     2389568.624      600131.224
     2389371.949      599772.045
#Sta/Elev= 30
       0 2240.52      38 2235.95    78.7 2224.71   101.8 2220.17     120 2211.52
     161 2212.85   179.2  2208.1   261.2  2208.4   320.5 2210.56   391.4 2209.71
   461.7 2213.03   493.6 2206.53   534.6    2209     685 2210.92   705.2 2208.57
   721.4 2202.57   738.6 2202.45   753.3 2203.26   757.9 2204.68   762.9 2208.71
     767 2211.68   776.1 2212.94   794.4 2209.76   880.7 2210.54   940.3 2208.73
   944.9 2210.85   949.4 2215.16   980.9 2248.36     995 2254.64  1144.2 2291.14
#Mann= 11 ,-1 , 0
       0     .06       0  204.58     .05       0  401.88     .06       0
  515.51      .1       0  619.15     .05       0  700.92      .1       0
   705.2    .045       0   762.9     .05       0  930.19      .1       0
  998.73      .1       0 1033.89      .1       0
#XS Ineff= 2 , 0
          685.56 2222.26  774.41         2222.63
Permanent Ineff=
       F       F
Bank Sta=705.2,762.9
XS Rating Curve= 0 ,0
Exp/Cntr=0.5,0.3

Type RM Length L Ch R = 1 ,1399    ,47.8,50.5,47.8
XS GIS Cut Line= 4
2390136.34321897600847.9318184242389786.67373139600197.263334119
2389703.17308544599711.0157816622389401.94379498 599547.59651664
#Sta/Elev= 30
       0 2227.19    16.7 2223.05    51.1 2208.82    78.4 2204.23   114.7 2204.42
   160.1 2207.38   223.1 2202.73   300.9 2204.64   400.8 2204.47   561.1 2208.57
   639.9  2206.1   664.2 2208.54   693.1 2204.16   830.4 2205.56   893.1 2209.34
     900 2208.35   906.9 2203.77   913.9 2199.66   924.2 2199.04   948.5 2199.48
   958.9  2204.3   964.3 2206.86   984.6 2208.57  1052.4  2205.4  1130.7 2204.88
  1163.2 2209.09  1352.2 2209.48  1415.4 2220.47  1503.9 2238.95  1574.7 2260.44
#Mann= 9 ,-1 , 0
       0     .05       0    4.17     .06       0  418.37     .05       0
  521.23     .06       0  722.77      .1       0  728.06     .05       0
   906.9    .045       0   958.9     .05       0 1470.69      .1       0
#XS Ineff= 2 , 0
          892.14 2211.37  981.35         2211.22
Permanent Ineff=
       F       F
Bank Sta=906.9,958.9
XS Rating Curve= 0 ,0
Exp/Cntr=0.5,0.3

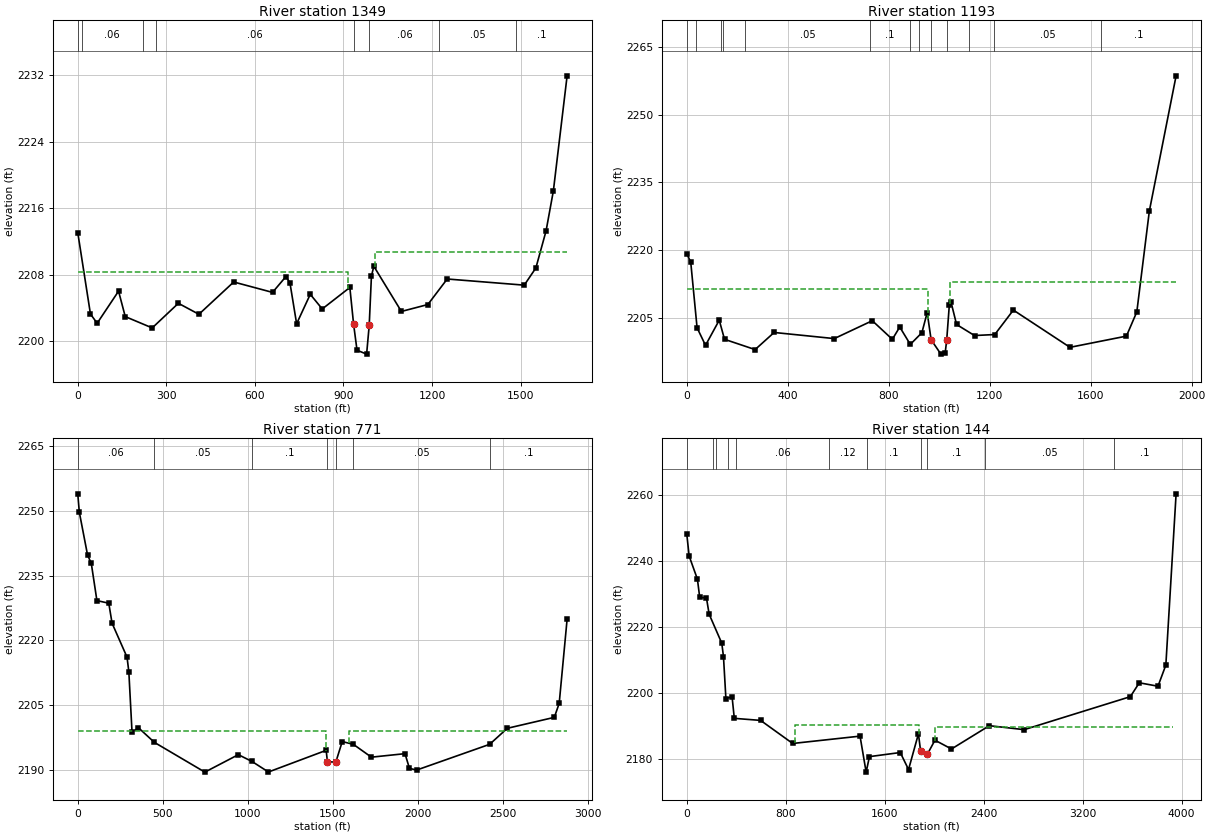
Type RM Length L Ch R = 1 ,1349    ,158.1,155.1,152.4
XS GIS Cut Line= 4
 2390186.0613382600848.8229404952389829.92291997600182.315553148
2389740.56658018599677.1272998172389424.88658828599449.808503945
#Sta/Elev= 30
       0 2213.08      43 2203.29    65.7 2202.18   138.2 2206.04   160.9 2202.98
   252.2 2201.62   340.8 2204.58   410.4 2203.26   528.3 2207.14   659.8 2205.89
   705.1 2207.79   718.8 2207.04   741.4 2202.12   787.6 2205.66   828.2  2203.9
   921.7 2206.48   934.42202.068     946 2198.94   978.5 2198.47   987.3 2201.92
   994.8 2207.84  1002.9 2209.03  1096.3  2203.6  1185.9 2204.43  1251.5  2207.5
  1512.5 2206.76  1551.9 2208.83  1586.4 2213.28  1611.1 2218.08  1657.7 2231.92
#Mann= 8 ,-1 , 0
       0     .05       0   13.19     .06       0  219.84     .05       0
  265.77     .06       0   934.4    .045       0   987.3     .06       0
  1225.3     .05       0 1484.73      .1       0
#XS Ineff= 2 , 0
          916.45 2208.36  1005.3         2210.73
Permanent Ineff=
       F       F
Bank Sta=934.4,987.3
XS Rating Curve= 0 ,0
Exp/Cntr=0.5,0.3

Type RM Length L Ch R = 1 ,1193    ,424.1,421.9,420.3
XS GIS Cut Line= 3
2390221.46433493600866.0067910752389830.55377226599579.603367448
 2389305.0367618599303.323619275
#Sta/Elev= 30
       0  2219.2    15.8 2217.29    40.9 2202.72    74.3 2198.82   128.7 2204.41
   149.6 2200.16   270.8 2197.88   346.1 2201.68   584.4 2200.32   734.9 2204.29
   814.3 2200.16   843.6 2202.89   885.4 2199.03   931.3 2201.62   952.3  2206.1
   967.9 2200.06  1006.6 2196.87  1023.3 2197.01  1029.62199.978    1040  2207.8
  1046.7 2208.43  1068.7 2203.45  1139.7    2201    1220 2201.22  1293.6 2206.65
  1517.9 2198.38  1741.4 2200.87  1782.6 2206.25  1832.3 2228.67  1938.2 2258.67
#Mann= 13 ,-1 , 0
       0     .05       0   35.22     .06       0  133.72     .05       0
   141.9     .06       0  232.23     .05       0  724.75      .1       0
  883.89     .05       0  921.76      .1       0  967.94    .045       0
 1029.62     .05       0 1118.77     .06       0 1217.27     .05       0
 1640.16      .1       0
#XS Ineff= 2 , 0
          956.12 2211.43 1043.12          2212.9
Permanent Ineff=
       F       F
Bank Sta=967.9,1029.6
XS Rating Curve= 0 ,0
Exp/Cntr(USF)=0,0
Exp/Cntr=0.3,0.1

Type RM Length L Ch R = 1 ,771     ,629.5,627,624.6
XS GIS Cut Line= 4
2390251.38323153601118.6795906982390621.91549975600518.231061286
2390126.70502118599263.0068495622389303.51418574599215.483604756
#Sta/Elev= 30
       0 2253.92     9.2 2249.66    57.5 2239.79    79.7 2237.81   112.7 2229.22
   182.5 2228.62   201.9 2223.99     290 2216.13   300.6 2212.73   319.4 2198.75
     357 2199.81     451 2196.42   747.9 2189.54   944.9 2193.58  1025.5    2192
    1122 2189.57  1461.7 2194.58  1469.12191.954  1518.42191.847  1556.3 2196.61
    1622 2195.96  1727.9    2193  1925.5 2193.81  1951.9  2190.4  1994.9 2190.03
  2423.5 2195.97  2527.7 2199.68  2804.2 2202.21  2832.9 2205.45  2879.5 2224.92
#Mann= 7 ,-1 , 0
       0     .06       0     451     .05       0  1025.5      .1       0
  1469.1    .045       0  1518.4      .1       0    1622     .05       0
  2423.5      .1       0
#XS Ineff= 2 , 0
       0    1459    2199    1599       0    2199
Permanent Ineff=
       F       F
Bank Sta=1469.1,1518.4
XS Rating Curve= 0 ,0
Exp/Cntr=0.3,0.1

Type RM Length L Ch R = 1 ,144     ,,,
XS GIS Cut Line= 5
2390295.83811185601138.2670309672390502.87123724600766.306384887
2391158.89784304600097.1182800432390741.82780964599240.907408688
2389120.80459456598993.891817396
#Sta/Elev= 30
       0 2248.18    19.3 2241.44    86.3 2234.43   104.6 2228.97   159.5  2228.7
   181.1 2223.83   283.1 2215.07   296.8 2211.02   316.4 2198.32   366.4 2198.85
   384.3 2192.33   596.9 2191.71   856.2 2184.73  1400.5 2186.95  1449.8 2176.06
  1476.5 2180.75  1725.7 2181.99  1792.5 2176.84  1872.5 2187.66  1889.82182.446
    19452181.509    2006 2185.72  2139.5 2183.06  2445.4 2190.11    2727 2188.91
  3584.8 2198.89  3657.6 2203.09  3808.4 2202.05    3872 2208.45  3954.9 2260.26
#Mann= 11 ,-1 , 0
       0     .06       0  212.17     .05       0  235.87     .06       0
  335.48     .05       0  398.95     .06       0 1150.73     .12       0
 1456.91      .1       0  1889.8    .045       0    1945      .1       0
 2412.18     .05       0 3455.73      .1       0
#XS Ineff= 2 ,-1
  873.86 1873.862190.258 2003.51 3932.472189.731
Permanent Ineff=
       F       F
Bank Sta=1889.8,1945
XS Rating Curve= 0 ,0
Exp/Cntr=0.3,0.1
LCMann Table=0